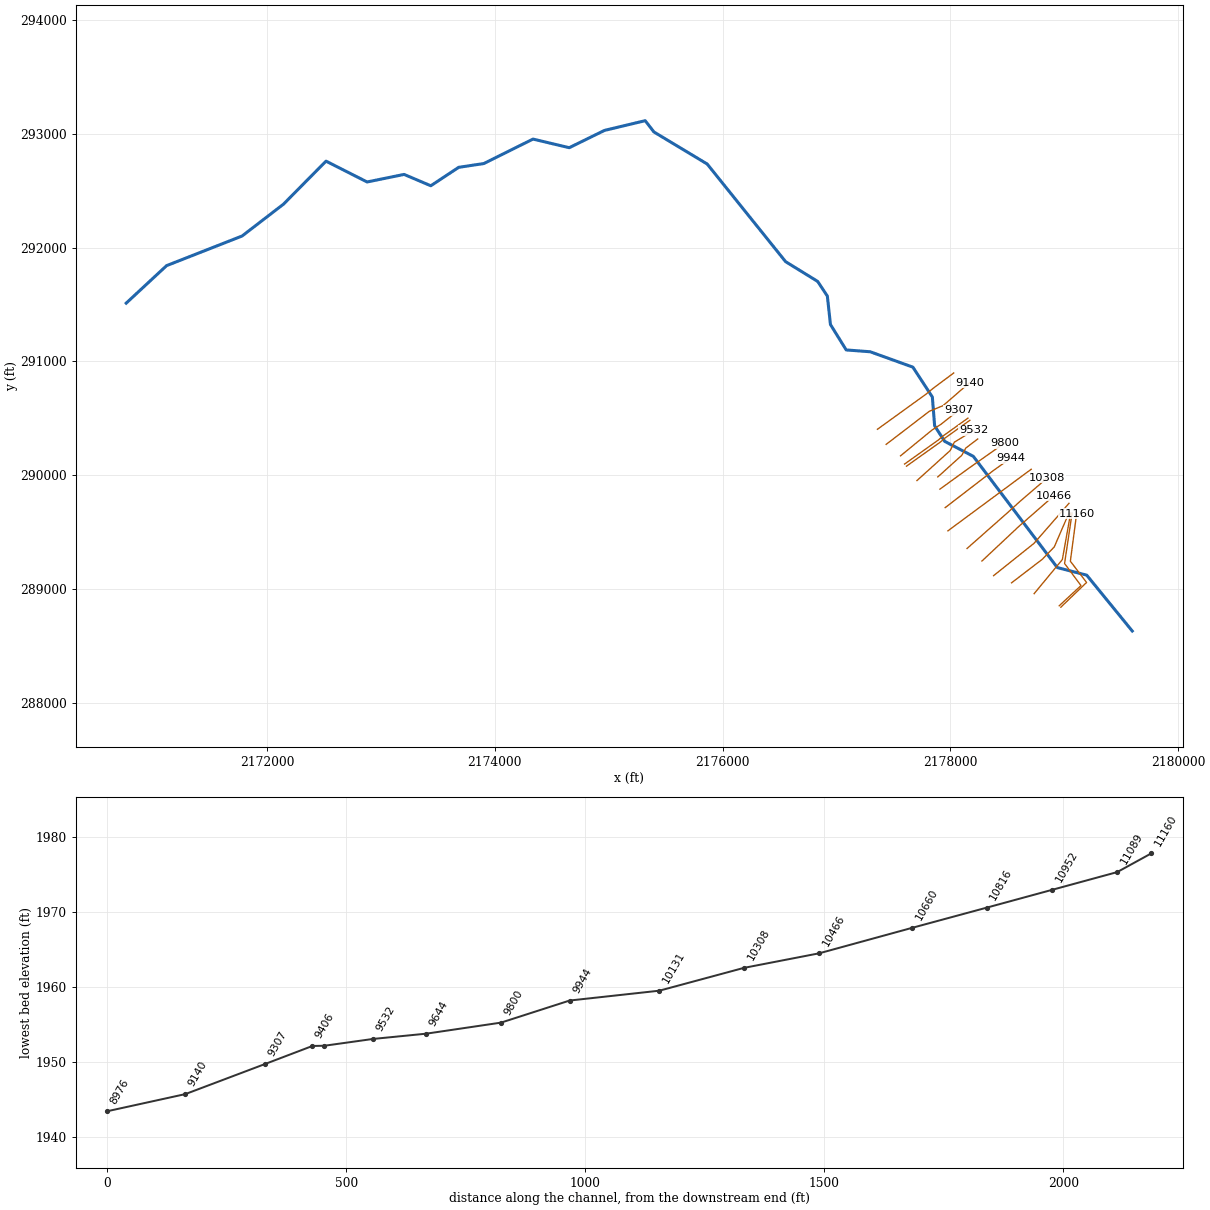
--- WADESCK1.prj (project) ---

Proj Title=WADESCK1
Current Plan=p01
Default Exp/Contr=0.3,0.1
English Units
Geom File=g01
Flow File=f01
Flow File=f02
Plan File=p01
Plan File=p02
Background Map Layer=Google Hybrid
Y Axis Title=Elevation
X Axis Title(PF)=Main Channel Distance
X Axis Title(XS)=Station
BEGIN DESCRIPTION:
Stream Name- Wades Creek 1
Greenbrier County, WV
WV Disaster Studies / PMR
WVDHSEM-2017-2, Flood Risk Project
HEC-RAS Version: 5.0.7
Upstream Extents: Approximately 50 feet upstream of Interstate 64
Downstream Extents: Confluence with Howard Creek
General Notes:
For the Hydrology the HEC-HMS version 4.2.1 was used. Rain fall grid was downloaded from the NOAA website and specified hyetogroph was used to calulate the 2016 flows in HEC-HMS. For the Multiprofile run the rainfall depth was taken from the NOAA website and hyetogrpahs were inputted into the HEC-HMS model.
Crossing profiles for 100 year plus were accounted for except for one area on the downstream most structure.
END DESCRIPTION:
DSS Export Rating Curves= 0
DSS Export Rating Curve Sorted= 0
DSS Export Volume Flow Curves= 0
DXF Filename=H:\CTP\WV\f05_Greenbrier_RiskMAP\f05_HH_Modeling\f02_Hydraulics\Final_Models\Zone_AE\Users\Greenbrier_AE\WadesCk_AE\Backup\copy_yesterday\WadesCk_AE.
DXF OffsetX= 0
DXF OffsetY= 0
DXF ScaleX= 1
DXF ScaleY= 10

--- WADESCK1.p01 (plan) ---

Plan Title=Floodplain
Program Version=5.07
Short Identifier=Floodplain
Geom File=g01
Flow File=f01
Subcritical Flow
K Sum by GR= 0
Std Step Tol= 0.01
Critical Tol= 0.01
Num of Std Step Trials= 20
Max Error Tol= 0.3
Flow Tol Ratio= 0.001
Split Flow NTrial= 30
Split Flow Tol= 0.02
Split Flow Ratio= 0.02
Log Output Level= 0
Friction Slope Method= 1
Unsteady Friction Slope Method= 2
Unsteady Bridges Friction Slope Method= 1
Parabolic Critical Depth
Global Vel Dist= 1 , 1 , 1
Global Log Level= 0
CheckData=True
Encroach Param=-1 ,0,0, 0
Computation Interval=1MIN
Output Interval=15MIN
Instantaneous Interval=15MIN
Mapping Interval=15MIN
Computation Time Step Use Courant=        0
Computation Time Step Use Time Series=    0
Computation Time Step Count To Double=0
Computation Time Step Max Doubling=0
Computation Time Step Max Halving=0
Computation Time Step Residence Courant=0
Run HTab= 1
Run UNet= 1
Run Sediment= 0
Run PostProcess= 1
Run WQNet= 0
Run RASMapper= 0
UNET Theta= 1
UNET Theta Warmup= 1
UNET ZTol= 0.02
UNET ZSATol= 0.05
UNET MxIter= 20
UNET Max Iter WO Improvement= 0
UNET MaxInSteps= 0
UNET DtIC= 0
UNET DtMin= 0
UNET MaxCRTS= 20
UNET WFStab= 2
UNET SFStab= 1
UNET WFX= 1
UNET SFX= 1
UNET 1D Methodology=Finite Difference
UNET DSS MLevel= 4
UNET Pardiso=0
UNET DZMax Abort= 100
UNET Use Existing IB Tables=-1
UNET Froude Reduction=False
UNET Froude Limit= 1
UNET Froude Power= 10
UNET D1 Cores= 0
UNET D2 Coriolis=0
UNET D2 Cores= 0
UNET D2 Theta= 1
UNET D2 Theta Warmup= 1
UNET D2 Z Tol= 0.01
UNET D2 Volume Tol= 0.01
UNET D2 Max Iterations= 20
UNET D2 Equation= 0
UNET D2 RampUpFraction=0.1
UNET D2 TimeSlices= 1
UNET D2 BCVolumeCheck=0
UNET D1D2 MaxIter= 0
UNET D1D2 ZTol=0.01
UNET D1D2 QTol=0.1
UNET D1D2 MinQTol=1
DSS File=dss
Write IC File= 0
Write IC File at Fixed DateTime=0
Write IC File at Sim End=0
Echo Input=False
Echo Parameters=False
Echo Output=False
Write Detailed= 0
HDF Write Warmup=0
HDF Write Time Slices=0
HDF Flush=0
HDF Face Node Velocities=0
HDF Compression= 1
HDF Chunk Size= 1
HDF Spatial Parts= 1
HDF Use Max Rows=0
HDF Fixed Rows= 1
Calibration Method= 0
Calibration Iterations= 20
Calibration Max Change=0.05
Calibration Tolerance=0.2
Calibration Maximum=1.5
Calibration Minimum=0.5
Calibration Optimization Method= 1
WQ AD Non Conservative
WQ ULTIMATE=-1
WQ Max Comp Step=1HOUR
WQ Output Interval=15MIN
WQ Output Selected Increments= 0
WQ Output face flow=0
WQ Output face velocity=0
WQ Output face area=0
WQ Output face dispersion=0
WQ Output cell volume=0
WQ Output cell surface area=0
WQ Output cell continuity=0
WQ Output cumulative cell continuity=0
WQ Output face conc=0
WQ Output face dconc_dx=0
WQ Output face courant=0
WQ Output face peclet=0
WQ Output face adv mass=0
WQ Output face disp mass=0
WQ Output cell mass=0
WQ Output cell source sink temp=0
WQ Output nsm pathways=0
WQ Output nsm derived pathways=0
WQ Output MaxMinRange=-1
WQ Daily Max Min Mean=-1
WQ Daily Range=0
WQ Daily Time=0
WQ Create Restart=0
WQ Fixed Restart=0
WQ System Summary=0
WQ Write To DSS=0
WQ Use Fixed Temperature=0
Sorting and Armoring Iterations= 10
XS Update Threshold= 0.02
Bed Roughness Predictor= 0
Hydraulics Update Threshold= 0.02
Energy Slope Method= 1
Volume Change Method= 1
Sediment Retention Method= 0
XS Weighting Method= 0
Number of US Weighted Cross Sections= 1
Number of DS Weighted Cross Sections= 1
Upstream XS Weight=0
Main XS Weight=1
Downstream XS Weight=0
Number of DS XS's Weighted with US Boundary= 1
Upstream Boundary Weight= 1
Weight of XSs Associated with US Boundary= 0
Number of US XS's Weighted with DS Boundary= 1
Downstream Boundary Weight= 0.5
Weight of XSs Associated with DS Boundary= 0.5
Percentile Method= 0
Sediment Output Level= 4
Mass or Volume Output= 0
Output Increment Type= 1
Profile and TS Output Increment= 1
XS Output Flag= 0
XS Output Increment= 10
Write Gradation File= 0
Read Gradation Hotstart= 0
Write HDF5 File= 1
Write Binary Output= 1
Write DSS Sediment File= 0
SV Curve= 0
Specific Gage Flag= 0

--- WADESCK1.p02 (plan) ---

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Plan Title=Floodway
Short Identifier=Floodway
Geom File=g01
Flow File=f02
Encroach Param=-1 ,0,0, 2
Encroach River=WADESCK1
Encroach Reach=Main
Encroach Node=11160
       1  389.32  445.29
Encroach Node=11089
       1  382.52  438.49
Encroach Node=10952
       1   290.7   329.2
Encroach Node=10816
       1  370.59  424.02
Encroach Node=10660
       1     439     518
Encroach Node=10466
       1     387   527.7
Encroach Node=10308
       1  363.17     552
Encroach Node=10131
       1     340   601.5
Encroach Node=9944
       1     230   496.5
Encroach Node=9800
       1     200   440.9
Encroach Node=9644
       1     200     360
Encroach Node=9532
       1     390     475
Encroach Node=9428
       1     375     450
Encroach Node=9406
       1     375   469.8
Encroach Node=9307
       1     345     509
Encroach Node=9140
       1     420  586.11
Encroach Node=8976
       1     450     570
Encroach Node=8847
       1     470  573.74
Encroach Node=8815
       1     470     595
Encroach Node=8619
       1     480   610.5
Encroach Node=8476
       1     500   591.3
Encroach Node=8281
       1   394.8     428
Encroach Node=8082
       1  338.42   372.4
Encroach Node=7994
       1     322     362
Encroach Node=7814
       1     320  394.72
Encroach Node=7580
       1     220     437
Encroach Node=7487
       1     280   445.5
Encroach Node=7452
       1     280  450.42
Encroach Node=7364
       1     210   416.3
Encroach Node=7247
       1     210   387.5
Encroach Node=7173
       1     220  359.79
Encroach Node=7080
       1     250     339
Encroach Node=6966
       1     380     470
Encroach Node=6841
       1   275.1  431.79
Encroach Node=6768
       1     260     430
Encroach Node=6680
       1     265     410
Encroach Node=6634
       1     230     346
Encroach Node=6567
       1   255.5   320.5
Encroach Node=6520
       1   261.4   363.2
Encroach Node=6363
       1   211.1   285.7
Encroach Node=6276
       1      82  145.04
Encroach Node=6173
       1     150  206.66
Encroach Node=6002
       1     175     242
Encroach Node=5896
       1     228     357
Encroach Node=5761
       1  350.72   457.9
Encroach Node=5626
       1  283.25     420
Encroach Node=5538
       1     265     380
Encroach Node=5509
       1     300     384
Encroach Node=5434
       1     300   372.3
Encroach Node=5322
       1   251.4   446.5
Encroach Node=5129
       1     415     466
Encroach Node=4926
       1     336     430
Encroach Node=4805
       1     270     345
Encroach Node=4764
       1   263.5   306.4
Encroach Node=4658
       1  249.85  294.25
Encroach Node=4577
       1   282.4   314.5
Encroach Node=4526
       1   309.3     370
Encroach Node=4438
       1     354     405
Encroach Node=4320
       1     388     450
Encroach Node=4292
       1   401.2  445.99
Encroach Node=4225
       1     394     440
Encroach Node=4164
       1     370     446
Encroach Node=3974
       1     380     440
Encroach Node=3826
       1     375     540
Encroach Node=3685
       1     370     550
Encroach Node=3563
       1     400     600
Encroach Node=3503
       1     430     730
Encroach Node=3481
       1     420     740
Encroach Node=3431
       1     398     750
Encroach Node=3372
       1   396.8     760
Encroach Node=3269
       1     355     750
Encroach Node=3199
       1     425     815
Encroach Node=3097
       1     520     870
Encroach Node=3029
       1     603     880
Encroach Node=2911
       1   670.1     900
Encroach Node=2786
       1     670     925
Encroach Node=2720
       1     513     775
Encroach Node=2651
       1     480     750
Encroach Node=2573
       1     525     875
Encroach Node=2510
       1     550     860
Encroach Node=2486
       1     550     860
Encroach Node=2436
       1     550     758
Encroach Node=2254
       1  691.22   841.2
Encroach Node=2086
       1     759     844
Encroach Node=1851
       1     723   802.3
Encroach Node=1690
       1     640     718
Encroach Node=1540
       1     690     798
Encroach Node=1340
       1  649.73   735.9
Encroach Node=1239
       1  661.91   748.9
Encroach Node=1076
       1     750  860.65
Encroach Node=903
       1  749.81   866.9
Encroach Node=628
       1     760   916.8
Encroach Node=336
       1     670   889.5
Encroach Node=208
       1     590   827.2
Encroach Node=155
       1     600     831
Encroach Node=135
       1     600   833.6
Encroach Node=101
       1     620   861.6
Encroach Node=38
       1     855    1136
Encroach Node=25
       1    1103    1270
Sediment Output Level= 3

--- WADESCK1.f01 (steady flow) ---

Flow Title=HMS flow from Howard Creek Study
Program Version=5.07
Number of Profiles= 6
Profile Names=f1p,f10p,f4p,f2p,f02p,f1pplus
River Rch & RM=WadesCk_AE,Main            ,11160
  1797.2   921.8  1237.9  1509.1    2550    2104
River Rch & RM=WadesCk_AE,Main            ,7173
  3065.2  1572.2  2110.8  2573.6  4348.2  3588.6
River Rch & RM=WadesCk_AE,Main            ,2720
  3523.9  1800.7  2424.7    2959  5010.4  4131.2
River Rch & RM=WADESCK1,Main            ,11160
  1797.2   921.8  1237.9  1509.1    2550    2104
River Rch & RM=WADESCK1,Main            ,7173
  3065.2  1572.2  2110.8  2573.6  4348.2  3588.6
River Rch & RM=WADESCK1,Main            ,2720
  3523.9  1800.7  2424.7    2959  5010.4  4131.2
Boundary for River Rch & Prof#=WADESCK1,Main            , 1
Up Type= 0
Dn Type= 3
Dn Slope=0.00605
Boundary for River Rch & Prof#=WADESCK1,Main            , 2
Up Type= 0
Dn Type= 3
Dn Slope=0.00605
Boundary for River Rch & Prof#=WADESCK1,Main            , 3
Up Type= 0
Dn Type= 3
Dn Slope=0.00605
Boundary for River Rch & Prof#=WADESCK1,Main            , 4
Up Type= 0
Dn Type= 3
Dn Slope=0.00605
Boundary for River Rch & Prof#=WADESCK1,Main            , 5
Up Type= 0
Dn Type= 3
Dn Slope=0.00605
Boundary for River Rch & Prof#=WADESCK1,Main            , 6
Up Type= 0
Dn Type= 3
Dn Slope=0.00605
DSS Import GetInterval= 0
DSS Import GetPeak= 0
DSS Import FillOption= 0

--- WADESCK1.f02 (steady flow) ---

Flow Title=Floodway
Program Version=5.07
Number of Profiles= 2
Profile Names=f1p,Floodway
River Rch & RM=WADESCK1,Main            ,11160
  1797.2  1797.2
River Rch & RM=WADESCK1,Main            ,7173
  3065.2  3065.2
River Rch & RM=WADESCK1,Main            ,2720
  3523.9  3523.9
Boundary for River Rch & Prof#=WADESCK1,Main            , 1
Up Type= 0
Dn Type= 3
Dn Slope=0.00605
Boundary for River Rch & Prof#=WADESCK1,Main            , 2
Up Type= 0
Dn Type= 3
Dn Slope=0.00605
DSS Import GetInterval= 0
DSS Import GetPeak= 0
DSS Import FillOption= 0

--- WADESCK1.g01 (geometry) ---

Geom Title=1m DEM Lidar Data
Program Version=5.07

River Reach=WADESCK1        ,Main
Reach XY= 30
     2179597.067       288631.45     2179197.099      289122.363
     2178938.766       289189.03     2178201.526      290166.113
     2177949.703      290298.144     2177861.682      290434.603
      2177841.63      290687.728     2177670.537      290949.967
     2177295.797      291085.123     2177085.365      291101.039
     2176947.003      291324.238     2176919.755      291574.446
     2176834.859      291702.832     2176552.828       291877.05
     2175864.547      292734.603     2175397.099      293016.113
     2175320.276      293115.332     2174962.464      293029.655
     2174653.349      292877.832      2174335.38      292953.613
     2173902.828      292738.509     2173682.776      292705.436
     2173437.868      292543.431     2173203.298      292643.135
     2172878.609       292576.79     2172517.839      292759.746
     2172143.974      292381.478     2171780.953       292102.05
     2171117.932      291841.634     2170763.505       291512.38

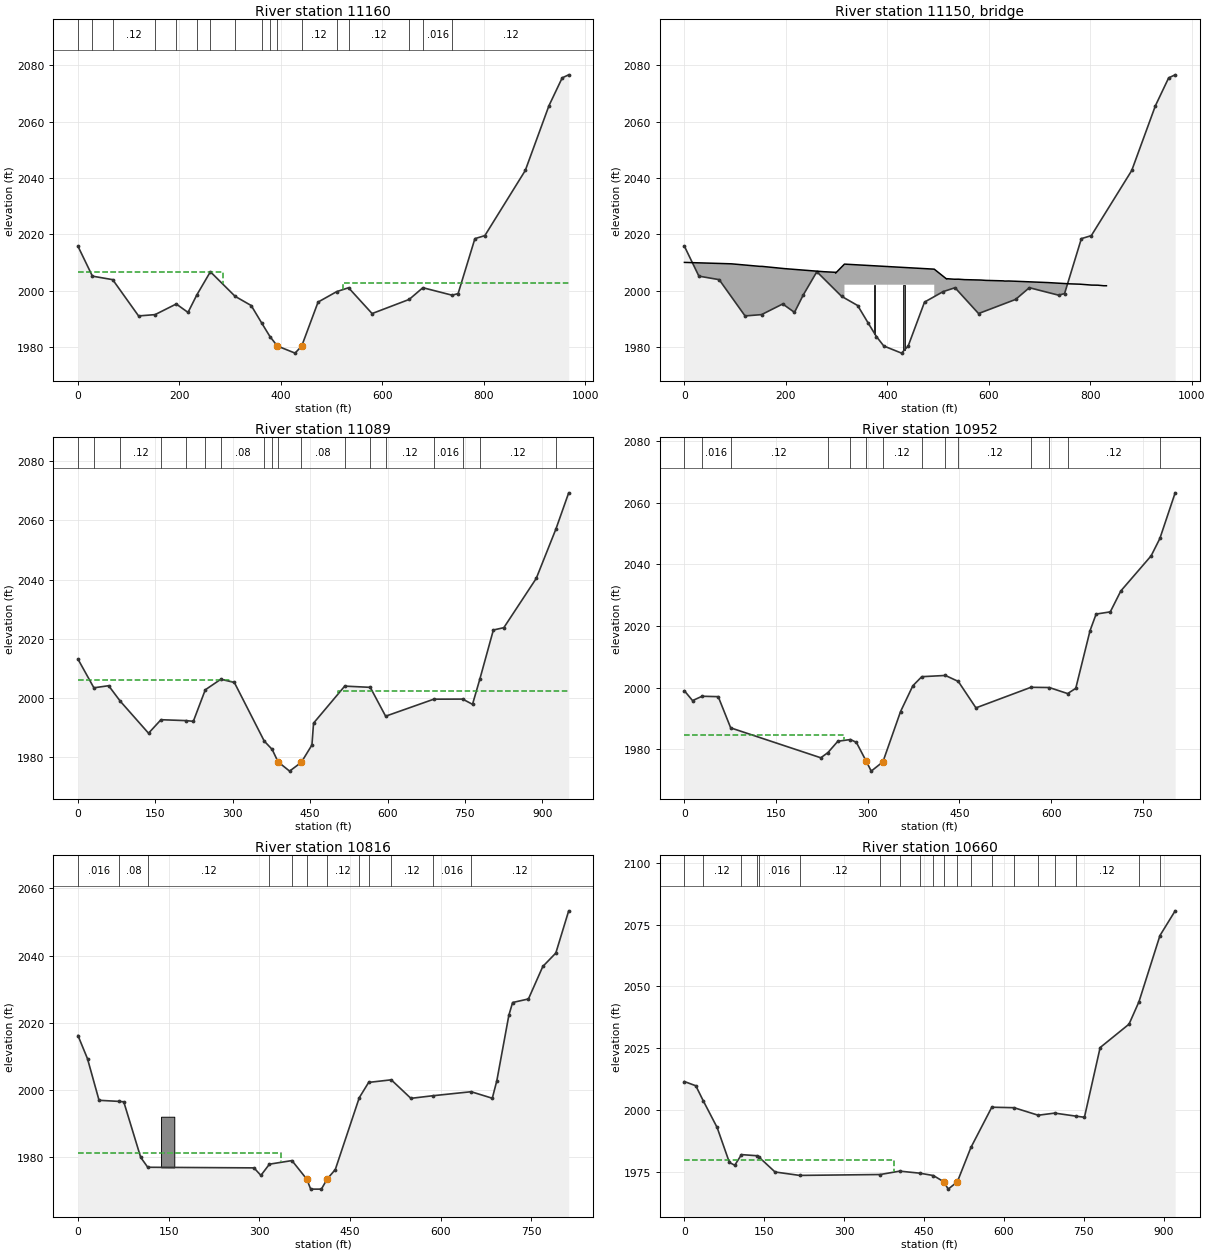
Type RM Length L Ch R = 1 ,11160   ,78.6,71.3,70.1
BEGIN DESCRIPTION:
Not Burnt
END DESCRIPTION:
XS GIS Cut Line= 4
     2178970.055      288841.232     2179195.684      289058.213
     2179053.519       289244.91     2179108.343      289661.097
#Sta/Elev= 30
       0 2015.74    28.5 2005.12    68.5 2003.87   119.5 1990.99     152 1991.45
   193.8 1995.23     217 1992.24   234.3 1998.43   261.1 2006.68   309.8 1997.96
   341.6 1994.68   362.6 1988.37   378.6 1983.65   393.1 1980.31   428.1 1977.78
   441.2 1980.33   473.4 1995.91   510.1 1999.62   533.5    2001   579.9 1991.83
     653 1996.85     680 2001.01   737.8 1998.35   749.5 1998.93   782.6 2018.44
   802.2 2019.51   881.9 2042.64   928.6 2065.65   954.7 2075.54   967.5 2076.61
#Mann= 17 ,-1 , 0
       0     .12       0    28.5    .016       0    68.5     .12       0
     152    .016       0   193.8     .06       0   234.3     .08       0
   261.1    .016       0   309.8     .12       0   362.6    .016       0
   378.6     .12       0   393.1     .04       0   441.2     .12       0
   510.1    .016       0   533.5     .12       0     653     .08       0
     680    .016       0   737.8     .12       0
#XS Ineff= 2 , 0
             285 2006.62     522         2002.51
Permanent Ineff=
       F       F
Bank Sta=393.1,441.2
XS Rating Curve= 0 ,0
Exp/Cntr=0.5,0.3

Type RM Length L Ch R = 3 ,11150   ,,,
BEGIN DESCRIPTION:
Merged DS Survey WAC110RP
Interstate 64
END DESCRIPTION:
Bridge Culvert--1,0,-1,-1, 0
Deck Dist Width WeirC Skew NumUp NumDn MinLoCord MaxHiCord MaxSubmerge Is_Ogee
16,45,2.6,0, 27, 27, , , 0.98, 0, 0,0,,
       0    92.4     149     153   197.5   274.3  297.99  298.09  315.52  492.52
  516.84  516.94   532.2   540.1   552.1   583.9   594.6   628.4   631.7   639.6
   716.3   760.5   780.1   802.8   814.8   826.7     832
    2010  2009.5 2008.59 2008.59 2007.79  2006.7 2006.48  2006.2 2009.39  2007.6
 2004.11 2004.22 2004.02 2004.04 2003.88 2003.74 2003.61 2003.45 2003.37  2003.4
 2002.84 2002.38 2002.26 2001.94 2001.91 2001.71 2001.71
                                                                 2002.08 2002.08
                                                                                
                                                        
       0    92.4     149     153   197.5   274.3  297.99  298.09  315.52  492.52
  516.84  516.94   532.2   540.1   552.1   583.9   594.6   628.4   631.7   639.6
   716.3   760.5   780.1   802.8   814.8   826.7     832
    2010  2009.5 2008.59 2008.59 2007.79  2006.7 2006.48  2006.2 2009.39  2007.6
 2004.11 2004.22 2004.02 2004.04 2003.88 2003.74 2003.61 2003.45 2003.37  2003.4
 2002.84 2002.38 2002.26 2001.94 2001.91 2001.71 2001.71
                                                                 2002.08 2002.08
                                                                                
                                                        
Pier Skew, UpSta & Num, DnSta & Num=  ,375, 2 ,375, 2 , 0 , 0 , 0 ,,
       3       3
    1975    2005
       3       3
    1975    2005
Pier Skew, UpSta & Num, DnSta & Num=  ,433, 2 ,433, 2 , 0 , 0 , 0 ,,
       3       3
    1975    2005
       3       3
    1975    2005
BR Coef=-1 , 1 , 0 ,, 0 ,,,0.8,0,1.33,0,
WSPro=,,,, 1 ,,,, 0 ,,,, 0 ,,,,-1 ,-1 ,-1 , 0 , 0 , 0 , 0 , 0
BC Design=,, 0 ,, 0 ,,0,,,,
BC HTab HWMax=0
BC HTab TWMax=0
BC HTab MaxFlow=0
BC Use User HTab Curves=0
BC User HTab FreeFlow(D)= 0

Type RM Length L Ch R = 1 ,11089   ,162.7,136.7,111.8
BEGIN DESCRIPTION:
Merged DS Survey WAC108BD
END DESCRIPTION:
XS GIS Cut Line= 4
     2178955.298      288853.384     2179146.959      289030.764
     2179002.603      289224.567     2179068.761      289667.947
#Sta/Elev= 30
       0 2013.14    30.9 2003.44    59.5 2004.15      82 1998.92   136.8  1988.1
   160.9 1992.66   209.6 1992.36   223.6 1992.11   246.8 2002.77   276.9 2006.33
   303.1 2005.25   361.1 1985.43   376.4 1982.63   387.8 1978.43   410.2 1975.29
   432.9 1978.26   453.5 1984.13   456.6  1991.5     517 2004.01   566.5  2003.6
   596.3 1993.85   689.7  1999.6   745.6 1999.63   764.7 1997.86   778.8 2006.32
   805.1 2022.97   825.4 2023.76   888.2  2040.4   926.4 2057.12   951.1 2069.32
#Mann= 18 ,-1 , 0
       0     .12       0    30.9    .016       0      82     .12       0
   160.9    .016       0   209.6     .06       0   246.8    .016       0
   276.9     .08       0   361.1    .016       0   376.4     .12       0
   387.8     .04       0   432.9     .08       0     517    .016       0
   566.5     .08       0   596.3     .12       0   689.7    .016       0
   745.6     .08       0   778.8     .12       0   926.4    .016       0
#XS Ineff= 2 , 0
             296    2006     504         2002.37
Permanent Ineff=
       F       F
Bank Sta=387.8,432.9
XS Rating Curve= 0 ,0
Exp/Cntr=0.5,0.3

Type RM Length L Ch R = 1 ,10952   ,135.7,136.1,133.9
BEGIN DESCRIPTION:
Not Burnt
END DESCRIPTION:
XS GIS Cut Line= 3
     2178735.578      288960.153     2178983.085       289259.41
     2179055.733      289667.455
#Sta/Elev= 30
       0 1998.99    13.3 1995.81    28.9 1997.22    55.3 1997.09    75.7 1986.96
   223.1 1977.25   234.7 1978.92     251 1982.62   271.6 1983.17   281.3 1982.26
   297.6 1976.06   305.6 1972.92   324.7 1975.93   353.6 1992.27   373.7 2000.63
   388.3 2003.57   426.9 2003.97     448 2002.04   476.9 1993.45   566.8 2000.12
   596.9 2000.05   626.9 1998.09   640.2 1999.79   663.5 2018.47   673.5 2023.89
   696.7 2024.61   713.9 2031.39   763.5 2042.79   777.8 2048.43   802.8 2063.24
#Mann= 14 ,-1 , 0
       0     .12       0    28.9    .016       0    75.7     .12       0
   234.7    .016       0   271.6     .08       0   297.6     .04       0
   324.7     .12       0   388.3    .016       0   426.9     .08       0
     448     .12       0   566.8    .016       0   596.9     .08       0
   626.9     .12       0   777.8    .016       0
#XS Ineff= 2 , 0
          261.69 1984.57
Permanent Ineff=
       F       F
Bank Sta=297.6,324.7
XS Rating Curve= 0 ,0
Exp/Cntr=0.3,0.1

Type RM Length L Ch R = 1 ,10816   ,157.4,156.7,156.5
XS GIS Cut Line= 4
     2178537.076      289054.835     2178807.918      289262.651
     2178911.826      289369.966     2179039.582      289664.656
#Sta/Elev= 30
       0 2016.25    15.8 2009.34    34.9 1996.98      68 1996.65    75.8 1996.53
   103.8 1980.02   115.5 1977.06   291.3 1976.88   302.7 1974.64   316.8 1977.98
   354.1 1979.05   378.6 1973.53   385.1 1970.56   402.8 1970.56   412.5 1973.61
   425.8 1976.37   465.5 1997.76     481  2002.3   518.4 2003.07   550.9 1997.56
   586.9 1998.33   650.6 1999.53   685.6 1997.59   693.1 2002.81     713 2022.27
   719.2 2026.06   745.4 2027.12   769.2 2036.79   790.7 2040.77     812 2053.33
#Mann= 12 ,-1 , 0
       0    .016       0      68     .08       0   115.5     .12       0
   316.8    .016       0   354.1     .06       0   378.6     .04       0
   412.5     .12       0   465.5     .08       0     481    .016       0
   518.4     .12       0   586.9    .016       0   650.6     .12       0
#XS Ineff= 2 , 0
           335.8 1981.36
Permanent Ineff=
       F       F
#Block Obstruct= 2 ,-1
   137.5   159.41992.096   227.6   247.8 1976.38
Bank Sta=378.6,412.5
XS Rating Curve= 0 ,0
Exp/Cntr=0.3,0.1

Type RM Length L Ch R = 1 ,10660   ,196.2,193.8,193
BEGIN DESCRIPTION:
Not Burnt
END DESCRIPTION:
XS GIS Cut Line= 3
     2178379.466      289117.976     2178733.362      289400.861
     2179041.198       289753.49
#Sta/Elev= 30
       0 2011.46    21.4 2009.75    35.1 2003.77    61.4 1992.84    84.4 1978.68
    94.5 1977.54   107.1 1981.85   136.5 1981.39   140.4 1980.76   170.1 1974.81
   216.3 1973.42   367.5 1973.78   404.2 1975.15   441.6 1974.33   467.2 1973.37
   487.1 1970.82   495.1 1967.86   512.3 1970.82   537.8 1984.74     577 2001.06
   618.8 2000.86   664.1 1997.81   695.1 1998.67   734.6 1997.45   750.9 1996.98
   780.4 2025.24   834.6 2034.72   853.2 2043.78   892.7 2070.65   921.2 2080.65
#Mann= 20 ,-1 , 0
       0    .016       0    35.1     .12       0   107.1    .016       0
   136.5     .12       0   140.4    .016       0   216.3     .12       0
   367.5    .016       0   404.2     .08       0   441.6     .06       0
   467.2     .12       0   487.1     .04       0   512.3     .12       0
   537.8     .08       0     577    .016       0   618.8     .06       0
   664.1     .08       0   695.1    .016       0   734.6     .12       0
   853.2    .016       0   892.7     .08       0
#XS Ineff= 2 , 0
          393.39  1979.7
Permanent Ineff=
       F       F
Bank Sta=487.1,512.3
XS Rating Curve= 0 ,0
Exp/Cntr=0.3,0.1

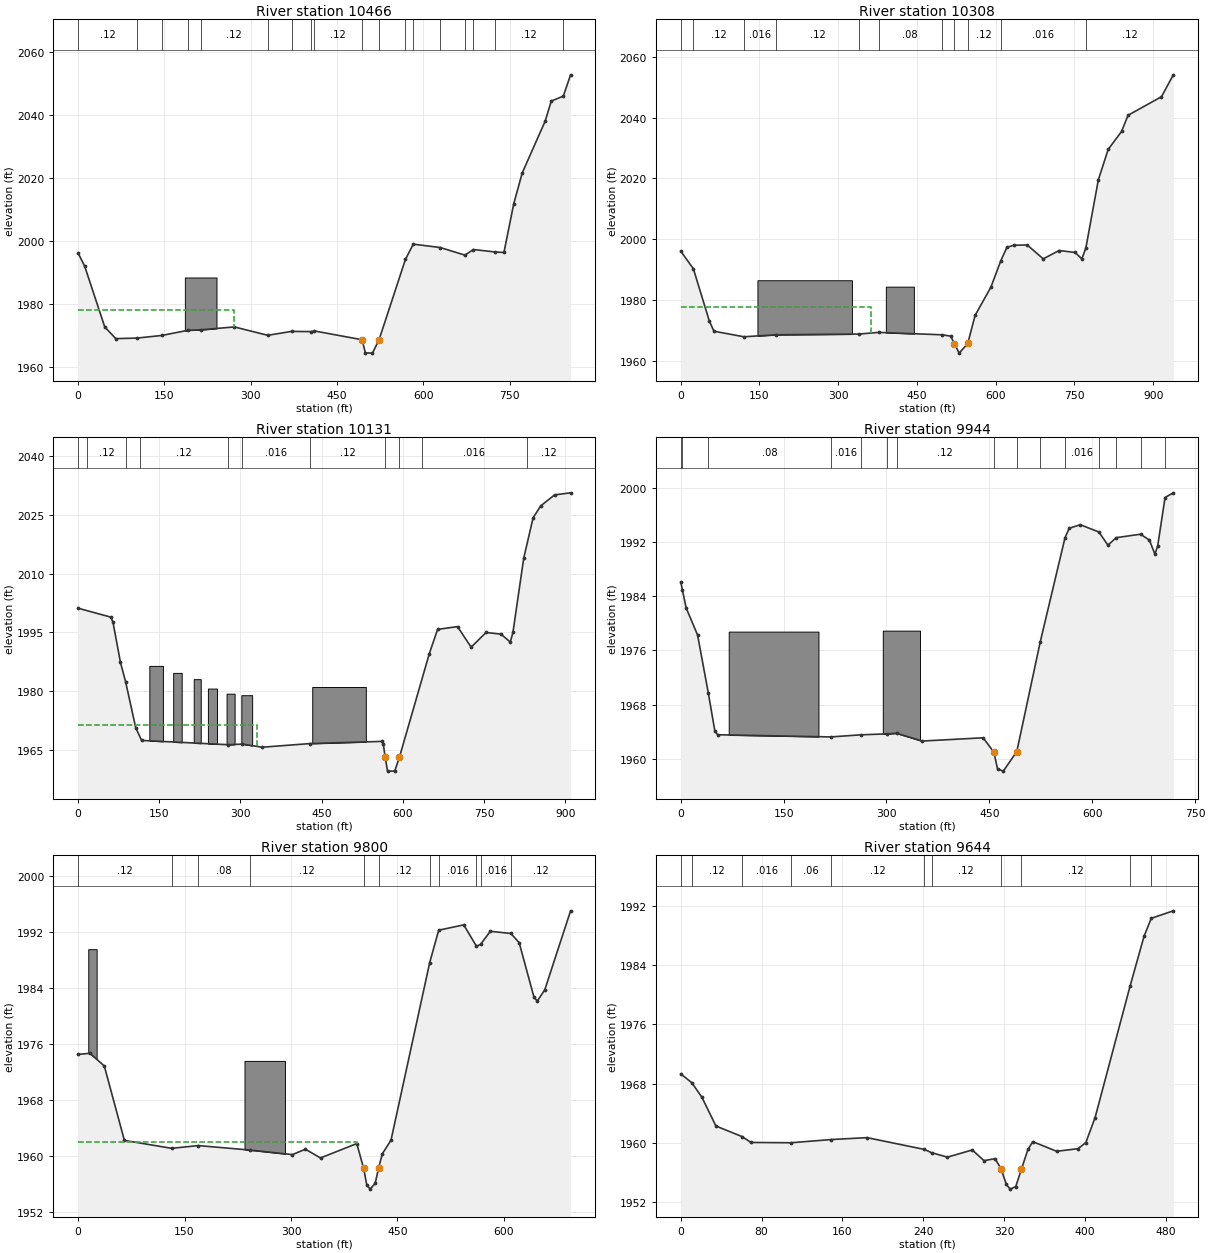
Type RM Length L Ch R = 1 ,10466   ,171.7,157.4,158.6
BEGIN DESCRIPTION:
Not Burnt
END DESCRIPTION:
XS GIS Cut Line= 3
     2178277.492      289246.716     2178600.689      289550.384
     2178911.192       289821.83
#Sta/Elev= 30
       0 1996.31    11.7    1992    46.4  1972.8    65.6 1969.08   102.7 1969.26
   145.8  1970.1   191.6 1971.75   212.9 1971.87   271.6  1972.8   329.6 1970.14
     371 1971.38   404.6 1971.31   410.8 1971.52  493.54 1968.73   499.3 1964.56
   511.6 1964.48  523.15 1968.76   568.9 1994.22   582.5 1999.08   629.3 1998.01
   672.2  1995.6   687.1 1997.37   724.7  1996.6   740.1 1996.43   757.2 2011.94
   771.9  2021.7   811.8 2038.15   822.3 2044.49   843.3 2046.09   855.9 2052.84
#Mann= 18 ,-1 , 0
       0     .12       0   102.7    .016       0   145.8     .12       0
   191.6     .08       0   212.9     .12       0   329.6    .016       0
     371     .12       0   404.6     .08       0   410.8     .12       0
  493.54     .04       0  523.15     .12       0   568.9     .08       0
   582.5    .016       0   629.3     .06       0   672.2     .08       0
   687.1    .016       0   724.7     .12       0   843.3    .016       0
#XS Ineff= 2 , 0
          270.92 1978.23
Permanent Ineff=
       F       F
#Block Obstruct= 1 ,-1
   185.6   240.6  1988.5
Bank Sta=493.54,523.15
XS Rating Curve= 0 ,0
Exp/Cntr=0.3,0.1

Type RM Length L Ch R = 1 ,10308   ,202.1,177.1,175.6
BEGIN DESCRIPTION:
Not Burnt
END DESCRIPTION:
XS GIS Cut Line= 4
      2178146.63      289356.927     2178496.332      289666.319
     2178607.524       289767.15      2178850.92      289977.057
#Sta/Elev= 30
       0 1996.06      24 1990.29    54.6 1973.01    63.3 1969.74   120.3 1967.92
   182.4 1968.58   339.3 1968.81   377.2 1969.36   497.3 1968.57   514.3 1968.13
   521.3 1965.68   530.4 1962.54   546.8 1965.71   560.8 1974.95     591 1984.27
   609.6 1992.85   621.3 1997.29   634.2 1998.02   660.2 1998.09   690.6 1993.53
   720.9 1996.28   751.2 1995.64   764.2 1993.56   771.8 1997.08   795.6 2019.51
   814.3 2029.51   839.8 2035.41   852.2 2040.74   915.9 2046.85   938.4 2054.04
#Mann= 11 ,-1 , 0
       0    .016       0      24     .12       0   120.3    .016       0
   182.4     .12       0   339.3    .016       0   377.2     .08       0
   497.3     .12       0   521.3     .04       0   546.8     .12       0
   609.6    .016       0   771.8     .12       0
#XS Ineff= 2 , 0
          363.17 1977.84
Permanent Ineff=
       F       F
#Block Obstruct= 2 ,-1
   146.1   326.1  1986.5   390.7   444.11984.398
Bank Sta=521.3,546.8
XS Rating Curve= 0 ,0
Exp/Cntr=0.3,0.1

Type RM Length L Ch R = 1 ,10131   ,185.7,187.6,187.7
BEGIN DESCRIPTION:
Not Burnt
END DESCRIPTION:
XS GIS Cut Line= 2
     2177978.254      289511.724     2178709.795      290052.971
#Sta/Elev= 30
       0 2001.14    60.3 1998.86    64.4 1997.66    78.4 1987.26    87.8 1982.39
   106.6 1970.57   117.4 1967.35   277.8 1966.25   303.6 1966.41   340.2 1965.61
   428.4 1966.54   561.7  1967.1     564 1966.39   567.6 1962.99   571.8  1959.5
   585.1  1959.5   593.8 1963.06     649 1989.52   664.3 1995.72   701.1 1996.43
   726.3 1991.17   753.8 1994.93   781.4 1994.51   798.6 1992.48   803.5 1994.93
   823.5 2013.97   840.8 2024.24   854.9  2027.3   880.6  2030.1     910 2030.62
#Mann= 11 ,-1 , 0
       0    .016       0    17.4     .12       0    87.8    .016       0
   113.9     .12       0   277.8    .016       0   303.6    .016       0
   428.4     .12       0   567.6     .04       0   593.8     .12       0
   635.7    .016       0     829     .12       0
#XS Ineff= 2 , 0
          331.24 1971.26
Permanent Ineff=
       F       F
#Block Obstruct= 7 ,-1
   131.7   156.8  1986.4   175.8   191.5 1984.61   213.7   226.7    1983
   239.9   256.7  1980.6   274.4   289.3  1979.3   301.7   321.7  1978.9
   432.7   531.7 1981.01
Bank Sta=567.6,593.8
XS Rating Curve= 0 ,0
Exp/Cntr=0.3,0.1

Type RM Length L Ch R = 1 ,9944    ,151.2,143.5,142.7
BEGIN DESCRIPTION:
Not Burnt
END DESCRIPTION:
XS GIS Cut Line= 3
     2177954.571      289715.797     2178378.812       290042.52
     2178527.581       290148.58
#Sta/Elev= 30
       0  1986.1     2.5 1984.88     7.9 1982.27    24.5 1978.29    40.1 1969.76
    49.7 1964.13    53.8 1963.56   218.6 1963.24   263.1 1963.55   300.5 1963.69
   314.6 1963.78   351.9 1962.63   440.9 1963.11   456.6 1960.98   461.9 1958.52
   470.3 1958.19     490 1961.08   524.1 1977.23   560.3 1992.64   566.4 1994.04
   582.6 1994.56   609.7 1993.49   622.9 1991.54   634.9 1992.65   670.4 1993.16
   683.3  1992.3   691.4 1990.22   695.4  1991.4   706.2 1998.58   718.2 1999.27
#Mann= 15 ,-1 , 0
       0    .016       0     2.5     .12       0    40.1     .08       0
   218.6    .016       0   263.1     .12       0   300.5     .08       0
   314.6     .12       0   456.6     .04       0     490     .12       0
   524.1     .08       0   560.3    .016       0   609.7     .06       0
   634.9    .016       0   670.4     .08       0   706.2     .12       0
#Block Obstruct= 2 ,-1
    69.9   200.81978.786   294.6   348.8 1978.93
Bank Sta=456.6,490
XS Rating Curve= 0 ,0
Exp/Cntr=0.3,0.1

Type RM Length L Ch R = 1 ,9800    ,113.6,156.2,165.3
BEGIN DESCRIPTION:
Not Burnt
END DESCRIPTION:
XS GIS Cut Line= 3
     2177908.225      289878.138     2178158.994      290059.798
     2178473.103      290281.184
#Sta/Elev= 30
       0 1974.52    16.7 1974.69      37 1972.87    65.3 1962.22   131.8 1961.09
   169.4 1961.48   242.2 1960.84   301.9 1960.19   320.4 1960.96   341.6 1959.71
   392.7 1961.77   402.2 1958.28   406.9 1955.82   411.6 1955.25   418.7  1956.1
   423.4 1958.27   428.8 1960.33   440.9 1962.25   495.4 1987.65   508.1  1992.3
   543.4 1993.06   561.3    1990     567 1990.26   580.8 1992.14   609.8 1991.83
   621.5 1990.51   642.3 1982.73     647 1982.15   657.6 1983.78   693.9 1995.07
#Mann= 11 ,-1 , 0
       0     .12       0   131.8    .016       0   169.4     .08       0
   242.2     .12       0   402.2     .04       0   423.4     .12       0
   495.4     .08       0   508.1    .016       0   561.3     .06       0
     567    .016       0   609.8     .12       0
#XS Ineff= 2 , 0
          392.65 1961.94
Permanent Ineff=
       F       F
#Block Obstruct= 2 ,-1
    14.4    26.21989.583   234.5   291.5  1973.6
Bank Sta=402.2,423.4
XS Rating Curve= 0 ,0
Exp/Cntr=0.3,0.1

Type RM Length L Ch R = 1 ,9644    ,99.3,112.3,110
BEGIN DESCRIPTION:
Not Burnt
END DESCRIPTION:
XS GIS Cut Line= 4
     2177889.796      289985.575     2178100.493      290175.629
     2178135.372      290238.981     2178240.008      290318.704
#Sta/Elev= 30
       0 1969.31    10.9 1968.13    20.9 1966.17    34.8 1962.29    60.7 1960.86
    69.5 1960.07   109.1 1960.03   148.6 1960.46   184.4 1960.72   241.2 1959.13
   248.3 1958.69     264 1958.09   288.6 1959.06   300.2 1957.62   311.1 1957.88
   317.1 1956.55   322.3 1954.41   326.1 1953.78   331.6 1954.12   337.3 1956.48
   343.7 1959.13   348.5 1960.18   372.1 1958.88   393.3 1959.23     401 1960.05
   410.2 1963.43   444.8 1981.14   458.7 1987.88   465.8 1990.28   487.6 1991.29
#Mann= 11 ,-1 , 0
       0    .016       0    10.9     .12       0    60.7    .016       0
   109.1     .06       0   148.6     .12       0   241.2     .06       0
   248.3     .12       0   317.1     .04       0   337.3     .12       0
   444.8     .08       0   465.8    .016       0
#XS Ineff= 2 , 0
                           354.9         1959.74
Permanent Ineff=
       F       F
Bank Sta=317.1,337.3
XS Rating Curve= 0 ,0
Exp/Cntr=0.3,0.1

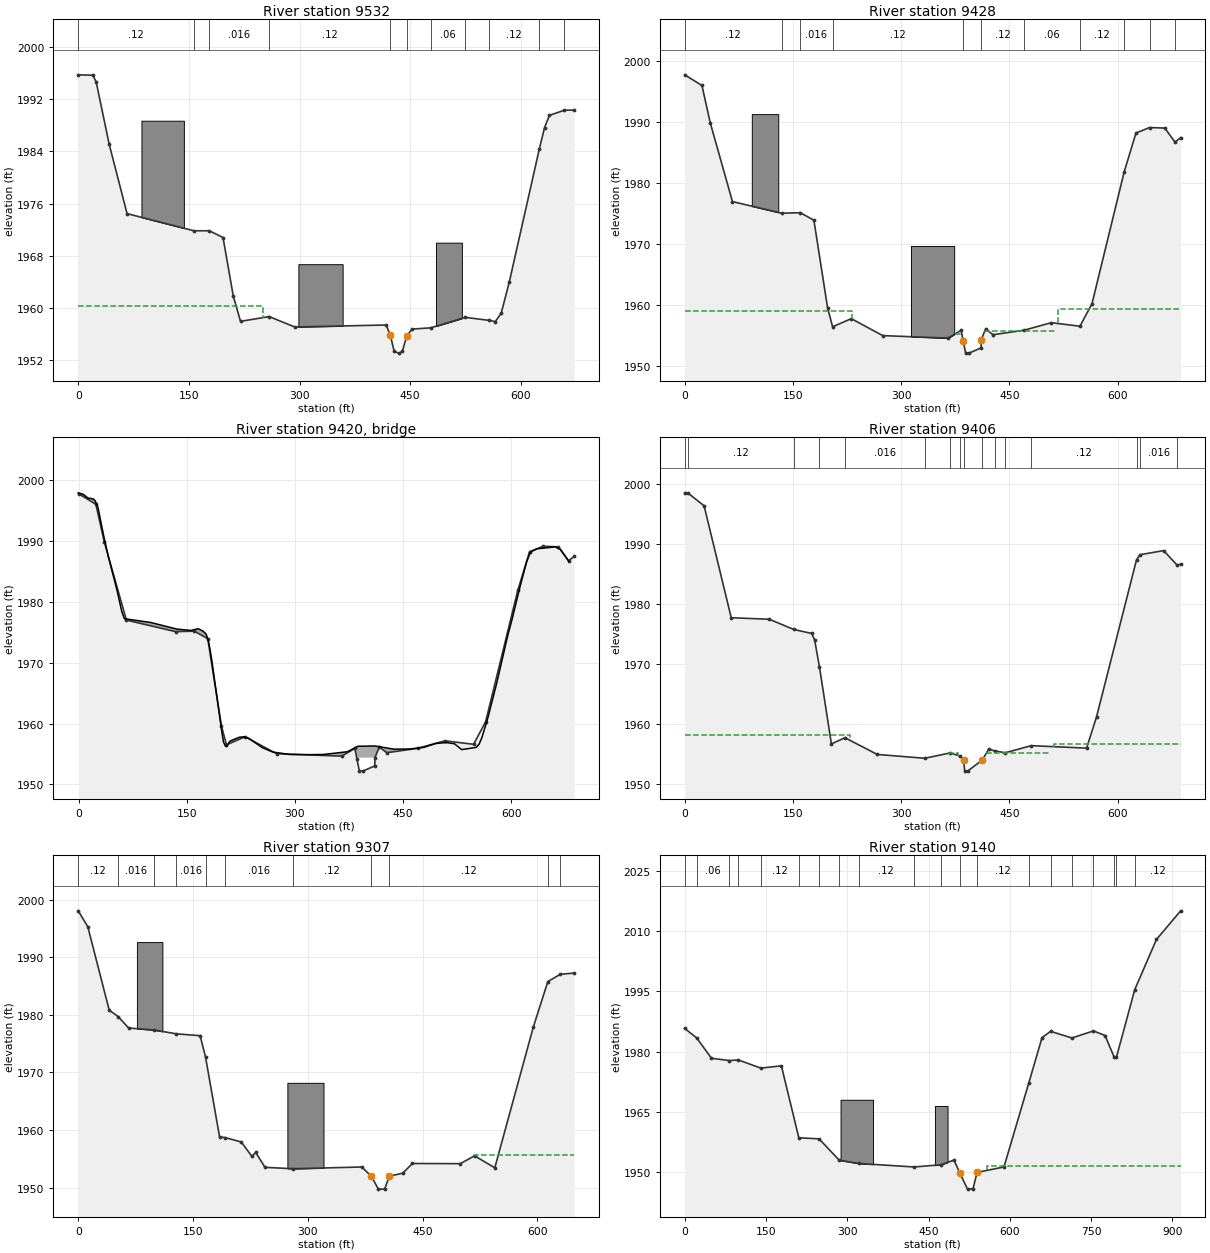
Type RM Length L Ch R = 1 ,9532    ,121.7,101,84.7
BEGIN DESCRIPTION:
Not Burnt
END DESCRIPTION:
XS GIS Cut Line= 4
     2177706.859      289953.543     2177998.703      290217.626
     2178034.294      290290.231     2178202.994      290393.444
#Sta/Elev= 30
       0 1995.72    19.7 1995.66    24.3 1994.66      42 1985.07    66.2 1974.45
   156.8 1971.82   177.7 1971.82   196.3 1970.79   210.2  1961.8     220 1957.94
   258.8 1958.67   293.4 1957.08   417.4 1957.38   423.1 1955.79   428.3 1953.33
   434.9 1953.07   439.3 1953.32   445.2  1955.7   452.6 1956.76   477.6 1956.94
   524.7 1958.55   556.9 1958.09   565.3 1957.91   573.3 1959.18   584.4 1964.02
     625 1984.36   632.1 1987.64   638.7 1989.51   659.1  1990.3   672.2 1990.31
#Mann= 11 ,-1 , 0
       0     .12       0   156.8     .06       0   177.7    .016       0
   258.8     .12       0   423.1     .04       0   445.2     .12       0
   477.6     .06       0   524.7    .016       0   556.9     .12       0
     625     .08       0   659.1    .016       0
#XS Ineff= 2 , 0
          249.97  1960.3
Permanent Ineff=
       F       F
#Block Obstruct= 3 ,-1
    85.7   143.21988.689   298.4   358.4  1966.7     485     520    1970
Bank Sta=423.1,445.2
XS Rating Curve= 0 ,0
Exp/Cntr=0.5,0.3

Type RM Length L Ch R = 1 ,9428    ,25.2,25.1,25.7
BEGIN DESCRIPTION:
Merged DS Survey WAC102BU
END DESCRIPTION:
XS GIS Cut Line= 4
     2177614.515      290079.832     2177912.298       290292.03
     2177946.118      290321.983      2178170.85       290483.03
#Sta/Elev= 30
       0 1997.79    23.9 1996.05    35.6 1989.85    66.2 1977.01   134.4 1975.11
   160.3 1975.19   179.1 1973.95     198 1959.63     205 1956.49   230.9 1957.82
   274.5 1955.04     365 1954.63   383.1 1955.91   385.9 1954.24   389.3 1952.22
   394.1 1952.17   410.8 1953.03     411 1954.39   417.1 1956.14   427.3 1955.19
   470.2 1955.92     508 1957.16   547.8 1956.58   564.5 1960.28   609.1 1981.89
   625.4 1988.24   644.2 1989.15   665.4 1989.06   679.5 1986.76   687.3 1987.49
#Mann= 11 ,-1 , 0
       0     .12       0   134.4     .06       0   160.3    .016       0
     205     .12       0   385.9    .045       0     411     .12       0
   470.2     .06       0   547.8     .12       0   609.1     .08       0
   644.2    .016       0   679.5     .08       0
#XS Ineff= 4 ,-1
       0   231.2    1959  375.06  382.31 1955.36  415.53  513.37 1955.79
   516.7   687.3 1959.48
Permanent Ineff=
       F       F       F       F
#Block Obstruct= 2 ,-1
      93   129.71991.347   313.6   373.51969.741
Bank Sta=385.9,411
XS Rating Curve= 0 ,0
Exp/Cntr=0.5,0.3

Type RM Length L Ch R = 3 ,9420    ,,,
BEGIN DESCRIPTION:
Merged DS Survey WAC100RP
Private Road
END DESCRIPTION:
Bridge Culvert--1,0,-1,-1, 0
Deck Dist Width WeirC Skew NumUp NumDn MinLoCord MaxHiCord MaxSubmerge Is_Ogee
2,15,2.6,0, 60, 60, , , 0.98, 0, 0,0,,
     -.6     6.6    12.9      20    22.9    26.9      35    41.1    52.9    59.9
    63.4    99.8   136.3   155.9   165.7   172.7   176.8   179.8   182.1   184.9
   198.6   200.9   203.3   205.1   209.2   211.9   223.1   229.4   236.1   254.9
     269   292.5   320.7   339.5  372.84  387.33  410.96  427.24   437.7   459.1
     479   495.1     510   521.3   531.3   551.5   555.5   559.5   567.6   579.7
   595.4   600.5   611.8   621.2   625.9   628.3     636   661.2   668.3   680.1
 1997.94 1997.68 1997.08 1996.95 1996.64  1995.5 1990.72  1987.5 1982.07 1978.39
 1977.24 1976.62 1975.53 1975.31 1975.59 1975.19 1974.71 1973.66 1972.28 1970.24
 1958.62 1956.96 1956.37 1956.22 1957.01 1957.22 1957.75 1957.81 1957.56 1956.02
 1955.32 1954.91 1954.88 1954.91 1955.36 1956.26 1956.31 1955.98 1955.78 1955.81
 1956.08 1956.71 1956.87 1956.67 1955.71 1956.07 1956.61 1957.74 1960.93 1966.54
 1974.59 1976.81 1982.31 1986.52 1987.94 1988.32 1988.74 1989.05 1988.63 1986.66
                                                                                
                                                                                
                                                                                
                                         1954.39 1954.39
                                                                                
                                                                                
    -1.1     6.1    12.4    19.5    22.4    26.4    34.5    40.6    52.4    59.4
    62.9    99.3   135.8   155.4   165.2   172.2   176.3   179.3   181.6   184.4
   198.1   200.4   202.8   204.6   208.7   211.4   222.6   228.9   235.6   254.4
   268.5     292   320.2     339  372.34  386.83  410.46  426.74   437.2   458.6
   478.5   494.6   509.5   520.8   530.8     551     555     559   567.1   579.2
   594.9     600   611.3   620.7   625.4   627.8   635.5   660.7   667.8   679.6
 1997.94 1997.68 1997.08 1996.95 1996.64  1995.5 1990.72  1987.5 1982.07 1978.39
 1977.24 1976.62 1975.53 1975.31 1975.59 1975.19 1974.71 1973.66 1972.28 1970.24
 1958.62 1956.96 1956.37 1956.22 1957.01 1957.22 1957.75 1957.81 1957.56 1956.02
 1955.32 1954.91 1954.88 1954.91 1955.36 1956.26 1956.31 1955.98 1955.78 1955.81
 1956.08 1956.71 1956.87 1956.67 1955.71 1956.07 1956.61 1957.74 1960.93 1966.54
 1974.59 1976.81 1982.31 1986.52 1987.94 1988.32 1988.74 1989.05 1988.63 1986.66
                                                                                
                                                                                
                                                                                
                                         1954.39 1954.39
                                                                                
                                                                                
BR Coef=-1 , 1 , 0 ,, 0 ,,,0.8,0,1.2,0,
WSPro=,,,, 1 ,,,, 0 ,,,, 0 ,,,,-1 ,-1 ,-1 , 0 , 0 , 0 , 0 , 0
BC Design=,, 0 ,, 0 ,,0,,,,
BC HTab HWMax=0
BC HTab TWMax=0
BC HTab MaxFlow=0
BC Use User HTab Curves=0
BC User HTab FreeFlow(D)= 0

Type RM Length L Ch R = 1 ,9406    ,101.6,98.6,95.9
BEGIN DESCRIPTION:
Merged US Survey WAC098BD
END DESCRIPTION:
XS GIS Cut Line= 4
     2177598.011      290098.712     2177895.794       290310.91
     2177929.614      290340.863     2178154.346      290501.909
#Sta/Elev= 30
       0 1998.38     4.2 1998.47    26.9 1996.31    64.5 1977.68   117.3 1977.42
   151.2 1975.72     176 1975.06     180 1974.01   186.8 1969.47   203.3 1956.67
   222.1  1957.7   266.8 1954.92   332.7 1954.28   367.9 1955.17   381.9 1954.64
   386.5    1954     388  1952.2     392 1952.14   412.5    1954   421.3 1955.81
   429.4 1955.51   444.3  1955.2   480.3 1956.38   556.9 1955.97   570.7 1961.18
   626.1 1987.32   630.8 1988.17   663.7 1988.85   682.5 1986.41   687.2 1986.59
#Mann= 16 ,-1 , 0
       0     .06       0     4.2     .12       0   151.2    .016       0
   186.8     .12       0   222.1    .016       0   332.7     .12       0
   367.9    .016       0   381.9     .12       0   386.5    .045       0
   412.5    .016       0   429.4     .12       0   444.3    .016       0
   480.3     .12       0   626.1     .08       0   630.8    .016       0
   682.5     .06       0
#XS Ineff= 4 ,-1
       0  229.11 1958.17   364.8  379.29 1955.22  417.95  505.52  1955.2
   511.7   687.2 1956.71
Permanent Ineff=
       F       F       F       F
Bank Sta=386.5,412.5
XS Rating Curve= 0 ,0
Exp/Cntr=0.5,0.3

Type RM Length L Ch R = 1 ,9307    ,150.2,167.3,151.6
BEGIN DESCRIPTION:
Not Burnt
END DESCRIPTION:
XS GIS Cut Line= 4
     2177562.361      290170.647     2177839.257      290397.715
     2177916.845      290447.542      2178072.02      290569.974
#Sta/Elev= 30
       0 1998.05    12.5  1995.3    40.5 1980.81    52.1  1979.7    65.9 1977.71
    98.8 1977.37   128.4  1976.7   159.3 1976.38   166.4 1972.65   184.7 1958.83
     192 1958.69     213 1957.94     227 1955.42   231.9 1956.11   244.1 1953.53
   280.6 1953.29   370.4 1953.59   382.9 1952.01   392.2 1949.75   400.3 1949.75
   406.6 1952.01     424 1952.51   436.6  1954.2   499.2 1954.17   517.9 1955.53
   544.3 1953.45   594.5 1977.81   613.6 1985.77     630 1987.04     648 1987.25
#Mann= 11 ,-1 , 0
       0     .12       0    52.1    .016       0    98.8     .12       0
   128.4    .016       0   166.4     .12       0     192    .016       0
   280.6     .12       0   382.9     .04       0   406.6     .12       0
   613.6     .08       0     630    .016       0
#XS Ineff= 2 , 0
                           517.2         1955.68
Permanent Ineff=
       F       F
#Block Obstruct= 2 ,-1
    76.7     1101992.622   273.3   320.5  1968.2
Bank Sta=382.9,406.6
XS Rating Curve= 0 ,0
Exp/Cntr=0.3,0.1

Type RM Length L Ch R = 1 ,9140    ,150.2,163.3,166.1
BEGIN DESCRIPTION:
H
END DESCRIPTION:
XS GIS Cut Line= 4
     2177436.358      290271.509     2177815.578      290562.308
     2177936.125      290611.789     2178167.899      290812.756
#Sta/Elev= 30
       0 1985.77      22 1983.43    49.4 1978.34    82.5 1977.76      99 1977.92
   140.4 1975.88   178.4 1976.45   210.6 1958.52   247.9 1958.26   285.1 1952.94
   320.7 1952.13   423.2 1951.25   472.8  1951.8   496.9 1952.97   507.5 1949.78
   521.8 1945.73   531.9 1945.81   539.5  1949.9   589.1 1951.25   635.1 1972.29
   659.3 1983.47   675.1 1985.04   714.5 1983.39   754.2 1985.15   775.6    1984
   791.9 1978.76   796.5 1978.55   830.4 1995.45   870.4 2007.93     915 2015.07
#Mann= 20 ,-1 , 0
       0     .12       0      22     .06       0    82.5     .12       0
      99     .06       0   140.4     .12       0   210.6    .016       0
   247.9     .08       0   285.1    .016       0   320.7     .12       0
   423.2    .016       0   472.8     .12       0   507.5    .045       0
   539.5     .12       0   635.1     .08       0   675.1    .016       0
   714.5     .08       0   754.2    .016       0   791.9     .12       0
   796.5     .06       0   830.4     .12       0
#XS Ineff= 2 , 0
                          557.62         1951.57
Permanent Ineff=
       F       F
#Block Obstruct= 2 ,-1
   287.6   347.5    1968   461.7     485 1966.46
Bank Sta=507.5,539.5
XS Rating Curve= 0 ,0
Exp/Cntr=0.3,0.1

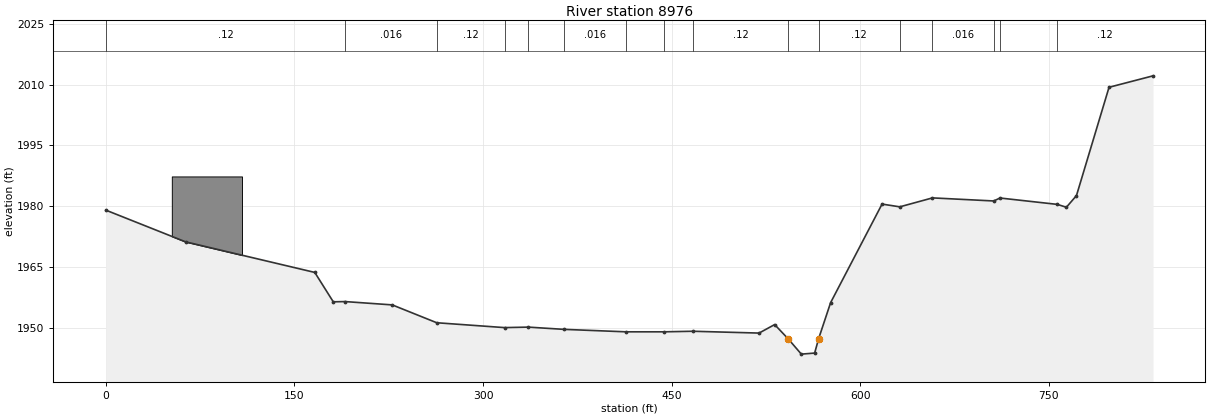
Type RM Length L Ch R = 1 ,8976    ,126.5,129.1,124.8
BEGIN DESCRIPTION:
Not Burnt
END DESCRIPTION:
XS GIS Cut Line= 4
     2177359.638      290404.093     2177786.015      290712.308
     2177849.366      290764.271     2178029.455      290898.804
#Sta/Elev= 30
       0 1979.02    63.4 1971.19   166.2 1963.63   180.9 1956.37   190.3 1956.43
   227.8 1955.61   263.2  1951.2   317.1    1950     336 1950.12   364.2 1949.57
   413.6 1948.96   444.1 1948.96   466.9  1949.1   519.5 1948.65   531.9 1950.75
   542.7 1947.21   553.1 1943.45   563.7 1943.71   566.9  1947.3   576.4 1956.17
   617.3 1980.51   631.4 1979.83   657.4 1982.04   706.1 1981.28   711.1 1982.01
   756.6 1980.44   763.9 1979.73   771.9 1982.61   797.8 2009.36   832.8 2012.19
#Mann= 16 ,-1 , 0
       0     .12       0   190.3    .016       0   263.2     .12       0
   317.1    .016       0     336     .12       0   364.2    .016       0
   413.6     .12       0   444.1     .08       0   466.9     .12       0
   542.7     .04       0   566.9     .12       0   631.4     .08       0
   657.4    .016       0   706.1     .08       0   711.1    .016       0
   756.6     .12       0
#Block Obstruct= 1 ,-1
    52.5   108.31987.341
Bank Sta=542.7,566.9
XS Rating Curve= 0 ,0
Exp/Cntr=0.3,0.1