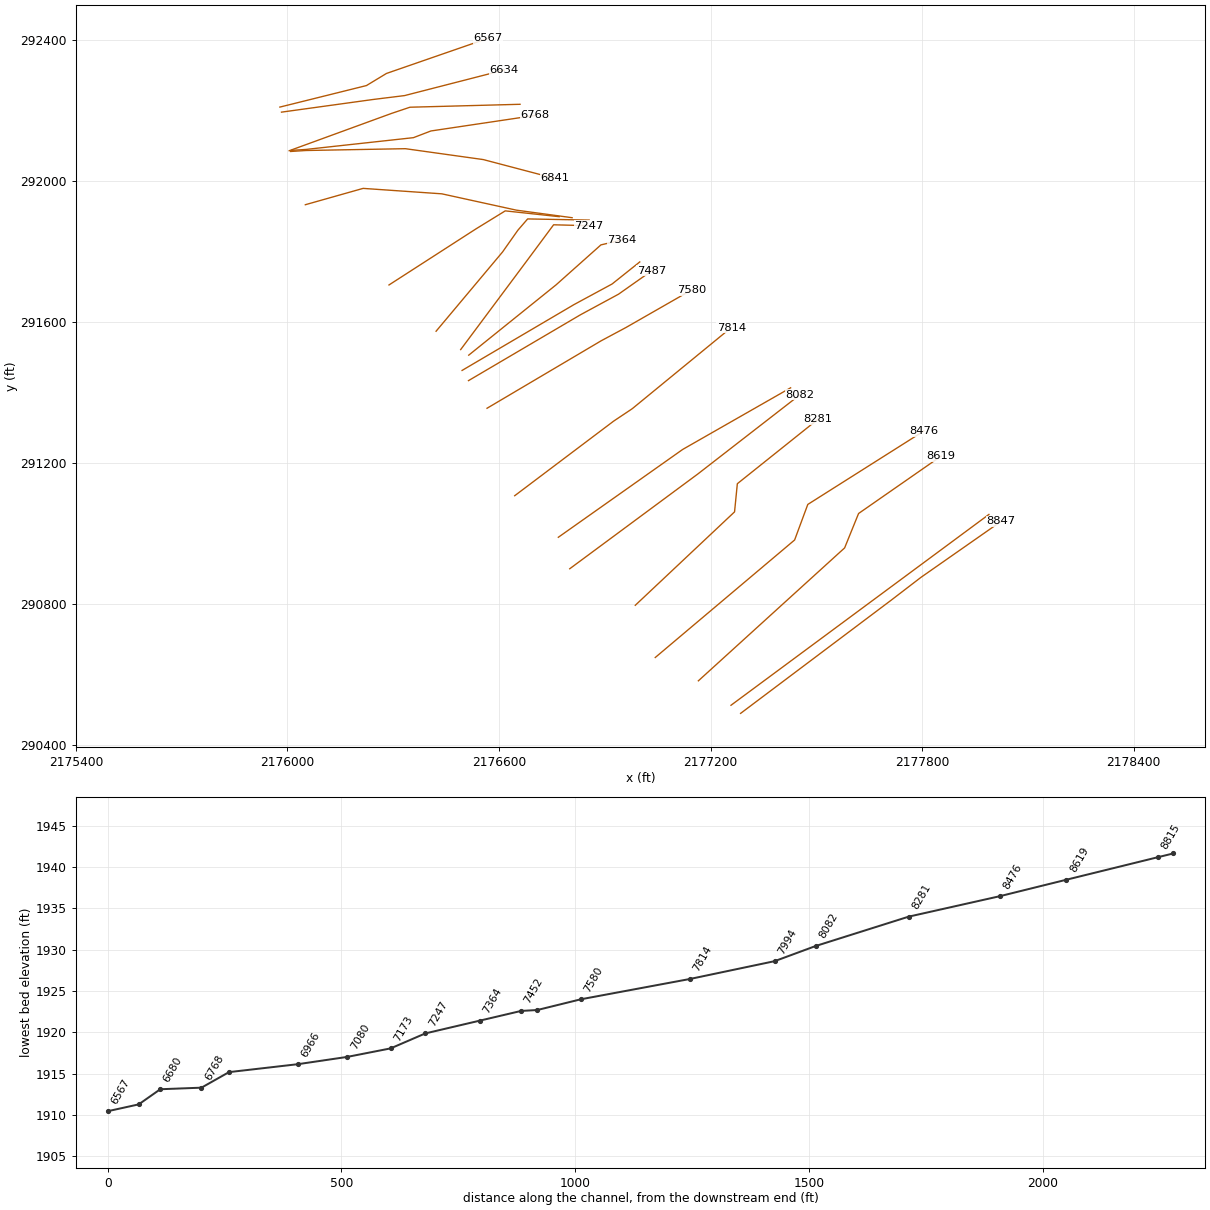
HEC-RAS study WADESCK1.prj: WADESCK1

--- WADESCK1.g01 (geometry) --- (continued)

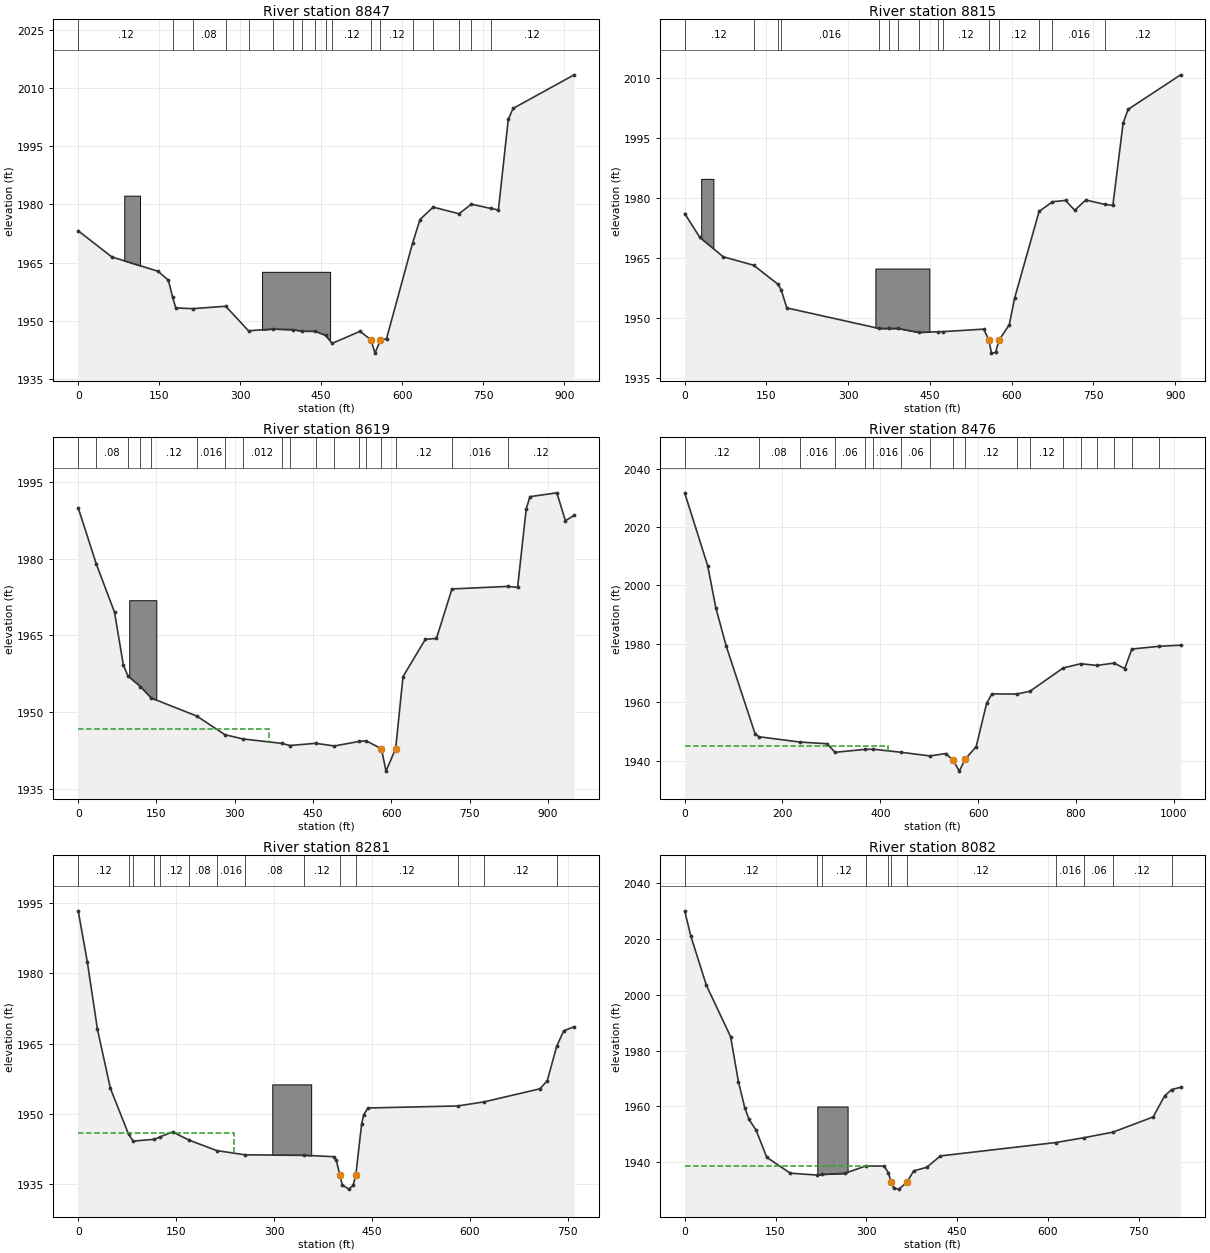
Type RM Length L Ch R = 1 ,8847    ,31.8,32.6,31.1
XS GIS Cut Line= 4
     2177285.197      290489.681     2177712.435      290810.831
     2177796.614      290875.406     2178024.359      291034.539
#Sta/Elev= 30
       0 1973.16    62.3 1966.44   147.8 1962.74     167 1960.44   174.8 1956.04
   180.7 1953.29   212.3 1953.11   273.2 1953.73   315.4  1947.4   359.9 1947.86
   397.4 1947.71   414.6 1947.32   439.3 1947.28   458.3 1946.22   470.1 1944.15
   521.9 1947.26   541.9 1945.11   549.6 1941.65   559.7 1945.03   570.9 1945.34
   619.1 1969.94   632.9 1976.07   657.2 1979.27   705.2 1977.57   728.1 1980.02
   763.5 1978.95   778.1 1978.55   796.4 2001.85   805.2  2004.7   918.4 2013.36
#Mann= 18 ,-1 , 0
       0     .12       0   174.8    .016       0   212.3     .08       0
   273.2     .12       0   315.4    .016       0   359.9     .08       0
   397.4    .016       0   414.6     .08       0   439.3     .12       0
   458.3     .08       0   470.1     .12       0   541.9     .04       0
   559.7     .12       0   619.1     .08       0   657.2    .016       0
   705.2     .08       0   728.1    .016       0   763.5     .12       0
#Block Obstruct= 2 ,-1
    85.3   114.41982.236   340.5   466.51962.605
Bank Sta=541.9,559.7
XS Rating Curve= 0 ,0
Exp/Cntr=0.3,0.1

Type RM Length L Ch R = 1 ,8815    ,162.9,196.2,203.1
XS GIS Cut Line= 2
     2177257.925      290512.677     2177989.466      291053.924
#Sta/Elev= 30
       0 1976.09    27.9  1970.1    70.7 1965.28   126.5 1963.16     171 1958.43
   176.9 1957.09   187.4  1952.5   356.3 1947.37   375.1 1947.37   391.5 1947.36
     429 1946.39   464.2 1946.53   473.6 1946.57   548.7  1947.2   558.3 1944.41
   562.8  1941.2   570.4 1941.37   576.8 1944.46   595.6 1948.32   605.4 1954.98
   650.3 1976.62   674.8 1979.03   698.8 1979.36   715.6  1976.9     736 1979.47
   771.5 1978.35   785.6 1978.11   804.4 1998.68   813.5 2002.11   909.9 2010.75
#Mann= 15 ,-1 , 0
       0     .12       0   126.5    .016       0     171     .12       0
   176.9    .016       0   356.3     .08       0   375.1    .016       0
   391.5     .08       0     429     .12       0   464.2     .08       0
   473.6     .12       0   558.3     .04       0   576.8     .12       0
   650.3     .08       0   674.8    .016       0   771.5     .12       0
#Block Obstruct= 2 ,-1
    30.3    52.71984.758   349.9   448.91962.338
Bank Sta=558.3,576.8
XS Rating Curve= 0 ,0
Exp/Cntr=0.3,0.1

Type RM Length L Ch R = 1 ,8619    ,122.7,142.3,143.9
XS GIS Cut Line= 4
     2177165.464      290582.038     2177580.249      290959.035
     2177619.794       291056.58     2177853.551      291219.155
#Sta/Elev= 30
       0 1989.97    34.7 1978.97    69.6 1969.54    86.5 1959.21    95.4 1957.07
   119.2 1955.01   139.7 1952.78   227.5 1949.23   280.9 1945.61   315.7 1944.76
   390.1  1943.9   405.7 1943.48   455.1 1943.91   490.8 1943.39   538.7 1944.28
     552 1944.39   581.1 1942.85   589.9 1938.47   608.4 1942.87   622.5 1956.96
   665.3 1964.25   686.6 1964.42   716.3  1974.1   823.3  1974.6   842.1 1974.41
   858.6 1989.72   865.7 1992.15   917.4  1992.9   933.7 1987.45   950.5 1988.48
#Mann= 18 ,-1 , 0
       0     .12       0    34.7     .08       0    95.4     .12       0
   119.2     .08       0   139.7     .12       0   227.5    .016       0
   280.9     .06       0   315.7    .012       0   390.1     .12       0
   405.7    .016       0   455.1     .12       0   490.8    .016       0
   538.7     .06       0     552     .12       0   581.1     .04       0
   608.4     .12       0   716.3    .016       0   823.3     .12       0
#XS Ineff= 2 , 0
          365.03 1946.71
Permanent Ineff=
       F       F
#Block Obstruct= 1 ,-1
    97.8   149.71971.895
Bank Sta=581.1,608.4
XS Rating Curve= 0 ,0
Exp/Cntr=0.3,0.1

Type RM Length L Ch R = 1 ,8476    ,193.3,195.4,198.1
XS GIS Cut Line= 4
     2177043.096      290648.159     2177438.427      290981.504
     2177475.775      291082.324     2177805.005      291290.631
#Sta/Elev= 30
       0 2031.71    47.2 2006.68    63.6 1992.42      85 1979.23   143.9  1949.3
   151.5 1948.26   235.5 1946.43   291.3 1945.85   307.5 1942.92   367.9 1943.91
   385.4 1943.98   442.6 1942.93   501.3 1941.68   533.5 1942.49   548.4  1940.4
   561.7 1936.48   573.3 1940.51   596.2 1944.87   617.4 1959.64   628.3 1962.92
     679 1962.85   705.9 1963.79   774.1 1971.79   809.8 1973.22   843.1 1972.65
   878.2 1973.45     900 1971.58   914.4 1978.26   969.1 1979.17  1014.2 1979.58
#Mann= 18 ,-1 , 0
       0     .12       0   151.5     .08       0   235.5    .016       0
   307.5     .06       0   367.9     .08       0   385.4    .016       0
   442.6     .06       0   501.3     .12       0   548.4     .04       0
   573.3     .12       0     679    .016       0   705.9     .12       0
   774.1    .016       0   809.8     .06       0   843.1    .016       0
   878.2     .06       0   914.4     .12       0   969.1    .016       0
#XS Ineff= 2 , 0
          414.87  1945.1
Permanent Ineff=
       F       F
Bank Sta=548.4,573.3
XS Rating Curve= 0 ,0
Exp/Cntr=0.3,0.1

Type RM Length L Ch R = 1 ,8281    ,208.6,198.9,193.3
BEGIN DESCRIPTION:
Not Burnt
END DESCRIPTION:
XS GIS Cut Line= 4
     2176986.463       290796.25     2177268.025      291061.203
     2177275.934      291141.084     2177504.505      291323.783
#Sta/Elev= 30
       0 1993.26    13.9 1982.42    29.4 1968.09    49.2 1955.49    77.1  1945.7
    84.1 1944.23   116.6 1944.61   125.8 1945.15   144.5 1946.18   169.9 1944.43
   212.1 1942.21   255.8  1941.3   346.3 1941.22   391.2  1940.9   395.2 1940.17
   400.5 1937.06   404.4  1934.9   414.3    1934   420.9 1934.78   425.2 1937.08
     434 1947.86   437.3 1949.89   443.9 1951.28     581 1951.71   621.6 1952.58
     707 1955.36   718.3 1957.08   732.7 1964.38   743.5 1967.71   759.5 1968.58
#Mann= 14 ,-1 , 0
       0     .12       0    77.1     .08       0    84.1     .12       0
   116.6     .08       0   125.8     .12       0   169.9     .08       0
   212.1    .016       0   255.8     .08       0   346.3     .12       0
   400.5     .04       0   425.2     .12       0     581    .016       0
   621.6     .12       0   732.7     .08       0
#XS Ineff= 2 , 0
          238.91 1946.01
Permanent Ineff=
       F       F
#Block Obstruct= 1 ,-1
   297.2   356.81956.305
Bank Sta=400.5,425.2
XS Rating Curve= 0 ,0
Exp/Cntr=0.3,0.1

Type RM Length L Ch R = 1 ,8082    ,85.4,87.6,84.9
BEGIN DESCRIPTION:
Not Burnt
END DESCRIPTION:
XS GIS Cut Line= 3
      2176800.54      290899.859     2177163.941      291168.729
     2177453.814      291393.575
#Sta/Elev= 30
       0 2029.97    10.1 2020.98    35.9 2003.29    75.8 1984.98    88.7 1968.92
    99.2 1959.56   106.3 1955.36     118 1951.51   135.5 1941.83   174.3 1936.15
   219.3 1935.47   227.5 1935.73   264.2 1936.08   298.6  1938.7   329.1  1938.7
   336.2 1936.39   340.8 1932.99   345.5 1930.77     354 1930.45   367.1 1932.96
   378.2 1936.99   399.5 1938.23   422.3 1942.33   612.4  1947.1   659.6 1948.85
   706.9 1950.81   773.6 1956.26   792.4 1963.77   804.2 1966.07   818.9 1966.87
#Mann= 11 ,-1 , 0
       0     .12       0   219.3     .06       0   227.5     .12       0
   298.6    .016       0   336.2     .12       0   340.8     .04       0
   367.1     .12       0   612.4    .016       0   659.6     .06       0
   706.9     .12       0   804.2    .016       0
#XS Ineff= 2 , 0
           309.2 1938.89
Permanent Ineff=
       F       F
#Block Obstruct= 1 ,-1
     219     2691959.999
Bank Sta=340.8,367.1
XS Rating Curve= 0 ,0
Exp/Cntr=0.3,0.1

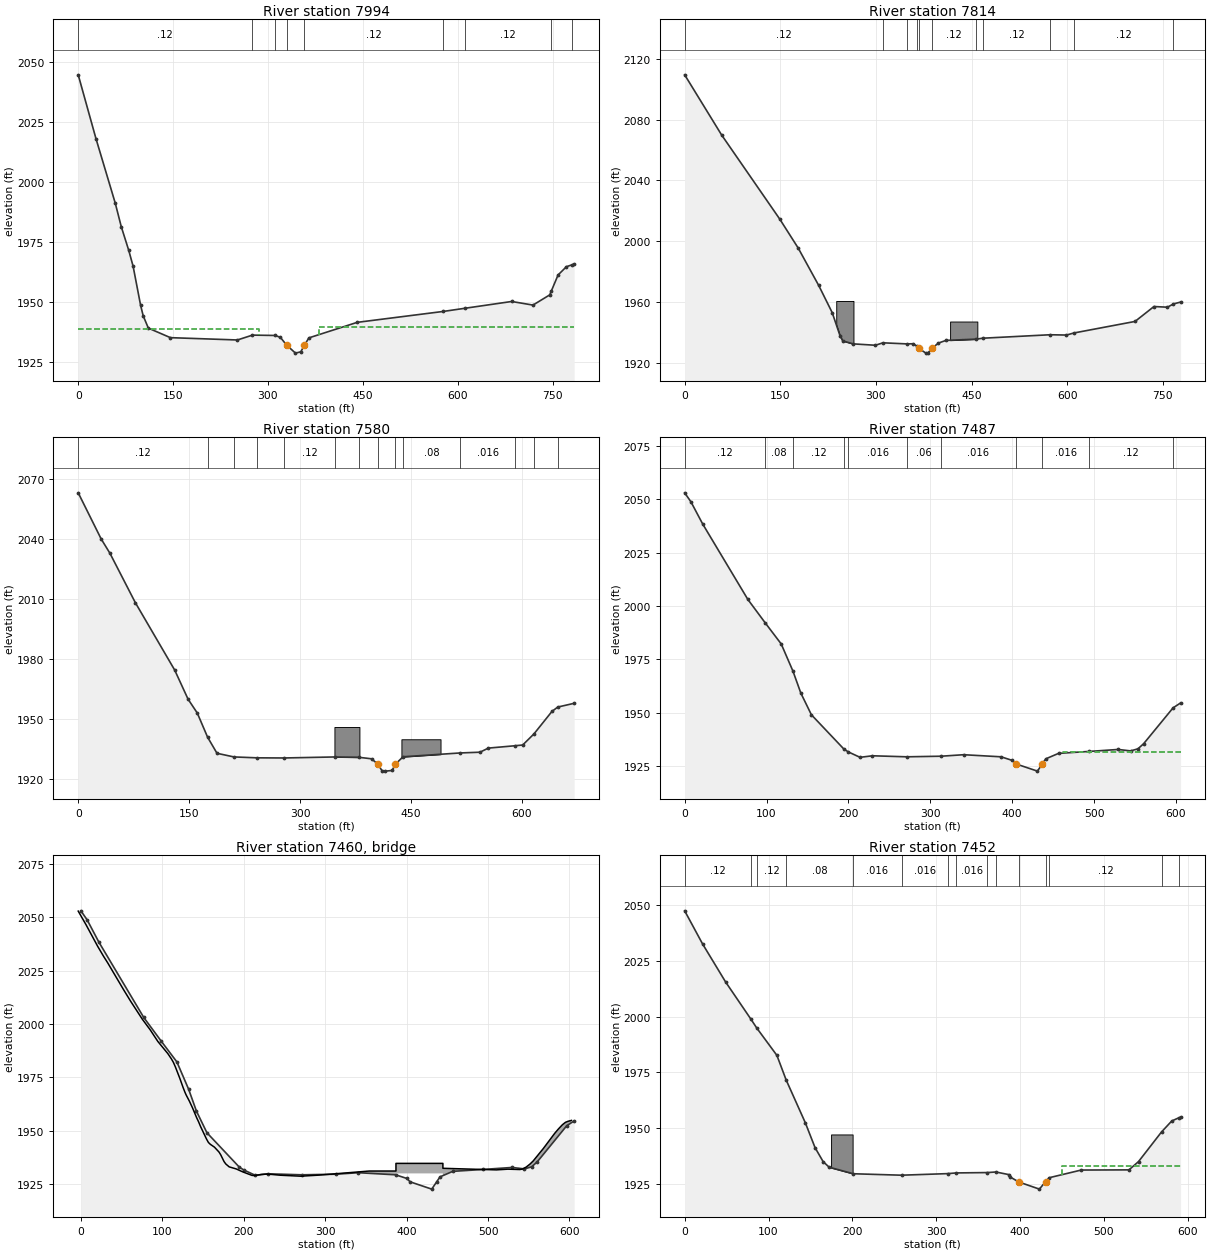
Type RM Length L Ch R = 1 ,7994    ,180.1,180.8,180.2
BEGIN DESCRIPTION:
Not Burnt
END DESCRIPTION:
XS GIS Cut Line= 3
     2176768.208      290989.173     2177120.951      291238.308
     2177427.032      291413.098
#Sta/Elev= 30
       0 2044.81    28.1 2018.15    58.6  1991.2    68.1 1981.39    79.9 1971.51
    86.8 1964.89    98.7 1948.52   102.8 1944.15   110.9 1939.06   145.8 1935.08
   251.7 1934.11   275.5 1936.14   311.7 1935.99   319.7 1935.18   329.5 1931.97
   343.5 1928.62   351.9 1929.17   357.7 1931.94   364.7 1934.99   441.1 1941.47
   577.3 1946.03     611 1947.33   685.3 1950.18     719 1948.68   745.5 1952.94
     748 1954.54   758.7 1961.26   771.9 1964.71   781.4 1965.55   784.1 1965.74
#Mann= 9 ,-1 , 0
       0     .12       0   275.5    .016       0   311.7     .12       0
   329.5     .04       0   357.7     .12       0   577.3    .016       0
     611     .12       0     748     .08       0   781.4    .016       0
#XS Ineff= 2 , 0
          286.49 1938.53   380.1         1939.55
Permanent Ineff=
       F       F
Bank Sta=329.5,357.7
XS Rating Curve= 0 ,0
Exp/Cntr=0.3,0.1

Type RM Length L Ch R = 1 ,7814    ,234.6,233.7,233.7
BEGIN DESCRIPTION:
Not Burnt
END DESCRIPTION:
XS GIS Cut Line= 4
      2176644.49       291107.05     2176925.598      291318.981
     2176977.798       291353.78     2177258.538      291583.912
#Sta/Elev= 30
       0  2109.4    57.9 2069.88   149.4 2014.39     178 1995.56   210.2 1970.96
   231.4 1953.07   243.7 1937.83   247.8 1934.53   264.1 1932.56   299.2 1931.64
   310.9 1933.25   348.4 1932.54   358.5 1932.63   364.9 1930.87   367.3 1929.68
   378.2 1926.47   382.1 1926.83   387.9 1929.69     398 1933.08   409.7 1934.83
   457.2 1935.67   467.6 1936.28   573.1 1938.55   598.8 1938.35   610.4 1939.71
   706.3  1947.3     736  1957.1   757.2 1956.66   766.6 1958.82   777.8 1960.02
#Mann= 11 ,-1 , 0
       0     .12       0   310.9    .016       0   348.4     .12       0
   364.9     .06       0   367.3     .04       0   387.9     .12       0
   457.2    .016       0   467.6     .12       0   573.1    .016       0
   610.4     .12       0   766.6    .016       0
#Block Obstruct= 2 ,-1
   237.7   264.71960.767   416.3     4591947.249
Bank Sta=367.3,387.9
XS Rating Curve= 0 ,0
Exp/Cntr=0.3,0.1

Type RM Length L Ch R = 1 ,7580    ,94.4,93.3,93.5
XS GIS Cut Line= 5
     2176565.965      291355.076     2176889.841      291546.555
      2176960.31      291584.281     2177126.586      291679.486
     2177146.668      291690.499
#Sta/Elev= 30
       0 2063.23      31 2040.18    42.9 2032.99    77.2 2008.33   130.5 1974.55
   148.6 1959.98     161 1953.09     175 1940.97   187.7 1932.93   210.6 1931.11
     242 1930.66     278 1930.59   347.4  1931.1   379.3 1930.94   396.8 1930.17
   405.3 1927.43   410.7  1924.3   415.4 1924.01   424.5 1924.33   428.9 1927.43
   439.2 1931.19   516.8 1933.11   543.3 1933.47   554.7 1935.53   590.8 1936.71
   601.1 1937.08   616.3 1942.61   640.7 1953.88   648.5 1956.06   670.7 1957.94
#Mann= 14 ,-1 , 0
       0     .12       0     175     .08       0   210.6    .016       0
     242     .06       0     278     .12       0   347.4     .06       0
   379.3     .12       0   405.3    .045       0   428.9    .016       0
   439.2     .08       0   516.8    .016       0   590.8     .12       0
   616.3     .08       0   648.5    .016       0
#Block Obstruct= 2 ,-1
   346.5   380.31946.094   437.1     4901939.951
Bank Sta=405.3,428.9
XS Rating Curve= 0 ,0
Exp/Cntr=0.8,0.6

Type RM Length L Ch R = 1 ,7487    ,34.4,34.7,34.1
BEGIN DESCRIPTION:
Merged DS Survey WAC092BU
END DESCRIPTION:
XS GIS Cut Line= 4
     2176513.382      291433.434     2176830.907      291620.221
     2176938.914      291678.641     2177032.749      291744.734
#Sta/Elev= 30
       0 2052.95     7.7  2048.7      22 2038.36    77.2 2003.04    98.7 1991.93
   117.9 1982.24   132.3 1969.47   141.9 1959.22   154.8 1949.08   194.6 1932.99
   200.1 1931.66   214.2 1929.17   229.4 1929.89   271.3 1929.41   313.2 1929.69
   340.8 1930.39   386.5 1929.41   400.3 1927.71   404.4 1926.12   430.9 1922.71
     437 1926.15   441.1 1928.46   456.7 1931.02   493.5 1931.91   529.6 1932.85
   544.8 1932.17   553.7 1933.16   560.6 1935.53   596.6 1952.33   605.8 1954.63
#Mann= 11 ,-1 , 0
       0     .12       0    98.7     .08       0   132.3     .12       0
   194.6     .08       0   200.1    .016       0   271.3     .06       0
   313.2    .016       0   404.4    .045       0     437    .016       0
   493.5     .12       0   596.6    .016       0
#XS Ineff= 2 , 0
          365.88 1929.16   462.7          1931.8
Permanent Ineff=
       F       F
Bank Sta=404.4,437
XS Rating Curve= 0 ,0
Exp/Cntr=0.5,0.3

Type RM Length L Ch R = 3 ,7460    ,,,
BEGIN DESCRIPTION:
Merged US Survey WAC090RP
Old Co 15/6
END DESCRIPTION:
Bridge Culvert--1,0,-1,-1, 0
Deck Dist Width WeirC Skew NumUp NumDn MinLoCord MaxHiCord MaxSubmerge Is_Ogee
10,20,2.6,0, 60, 60, , , 0.98, 0, 0,0,,
    -3.3     6.2    20.6    27.7    33.1    52.3    61.1    75.4      85    94.5
   106.8   111.2   113.6     116   121.6   125.5   127.9   129.3   133.2     137
   142.2   144.5     147   154.2   156.6   158.9     164   169.6   171.7   175.8
     178   182.1   190.9   198.6   210.2   213.5   221.7   229.4   244.8     270
     291  354.25  386.94  386.94  444.61  444.61   510.2   524.5     539   542.1
   546.8   551.5   555.5     568   581.9   586.6   591.3   595.1   598.3   602.5
 2052.82 2046.51 2036.34 2031.75 2028.49 2016.11 2010.63 2002.25 1997.32 1991.82
 1986.12 1983.63 1982.03 1979.94 1974.43 1970.27 1967.94 1966.75  1963.9 1960.81
  1956.1 1954.25 1951.97  1946.2 1944.55  1943.7 1942.36 1940.07 1938.79 1935.61
 1934.47 1933.13 1932.14 1930.81 1929.13 1929.08 1929.58 1929.76 1929.22 1928.76
 1929.23 1931.18 1931.18 1934.76 1934.76 1932.46 1931.72 1932.05 1931.88 1932.07
 1933.01 1934.42  1935.9 1941.75 1948.82 1950.92 1952.82 1953.97 1954.46 1954.87
                                                                                
                                                                                
                                                                                
                                                                                
                         1930.07 1930.07
                                                                                
    -3.3     6.2    20.6    27.7    33.1    52.3    61.1    75.4      85    94.5
   106.8   111.2   113.6     116   121.6   125.5   127.9   129.3   133.2     137
   142.2   144.5     147   154.2   156.6   158.9     164   169.6   171.7   175.8
     178   182.1   190.9   198.6   210.2   213.5   221.7   229.4   244.8     270
     291  354.25  386.94  386.94  444.61  444.61   510.2   524.5     539   542.1
   546.8   551.5   555.5     568   581.9   586.6   591.3   595.1   598.3   602.5
 2052.82 2046.51 2036.34 2031.75 2028.49 2016.11 2010.63 2002.25 1997.32 1991.82
 1986.12 1983.63 1982.03 1979.94 1974.43 1970.27 1967.94 1966.75  1963.9 1960.81
  1956.1 1954.25 1951.97  1946.2 1944.55  1943.7 1942.36 1940.07 1938.79 1935.61
 1934.47 1933.13 1932.14 1930.81 1929.13 1929.08 1929.58 1929.76 1929.22 1928.76
 1929.23 1931.18 1931.18 1934.76 1934.76 1932.46 1931.72 1932.05 1931.88 1932.07
 1933.01 1934.42  1935.9 1941.75 1948.82 1950.92 1952.82 1953.97 1954.46 1954.87
                                                                                
                                                                                
                                                                                
                                                                                
                         1930.07 1930.07
                                                                                
BR Coef=-1 , 1 , 0 ,, 0 ,,,0.8,0,1.2,0,
WSPro=,,,, 1 ,,,, 0 ,,,, 0 ,,,,-1 ,-1 ,-1 , 0 , 0 , 0 , 0 , 0
BC Design=,, 0 ,, 0 ,,0,,,,
BC HTab HWMax=0
BC HTab TWMax=0
BC HTab MaxFlow=0
BC Use User HTab Curves=0
BC User HTab FreeFlow(D)= 0

Type RM Length L Ch R = 1 ,7452    ,58.2,88,93.8
BEGIN DESCRIPTION:
Merged US Survey WAC088BD
END DESCRIPTION:
XS GIS Cut Line= 4
     2176495.249      291462.416     2176812.774      291649.203
     2176920.781      291707.623     2176999.174      291770.152
#Sta/Elev= 30
       0 2047.49    21.3 2032.66    48.7 2015.63    79.2 1998.76      86 1994.88
     110 1982.62     121 1971.61   143.9 1952.37   155.5 1941.21   165.1 1934.96
   172.3 1932.44   201.1  1929.5   258.6 1928.85   313.7 1929.56   324.1 1929.87
   360.8 1930.03   371.2 1930.29   387.1 1929.08   388.1 1928.08   398.4 1925.82
   423.1  1922.6   430.4 1925.98   435.1 1927.75   472.9 1931.16   529.9 1931.24
   541.3 1934.96   568.8 1948.29   580.9 1953.17   589.6 1954.66   591.5 1954.81
#Mann= 15 ,-1 , 0
       0     .12       0    79.2     .08       0      86     .12       0
     121     .08       0   201.1    .016       0   258.6    .016       0
   313.7     .08       0   324.1    .016       0   360.8    .016       0
   371.2     .06       0   398.4    .045       0   430.4    .016       0
   435.1     .12       0   568.8     .08       0   589.6    .016       0
#XS Ineff= 2 , 0
          377.94 1928.73  450.42         1932.84
Permanent Ineff=
       F       F
#Block Obstruct= 1 ,-1
   174.6   200.31947.141
Bank Sta=398.4,430.4
XS Rating Curve= 0 ,0
Exp/Cntr=0.5,0.3

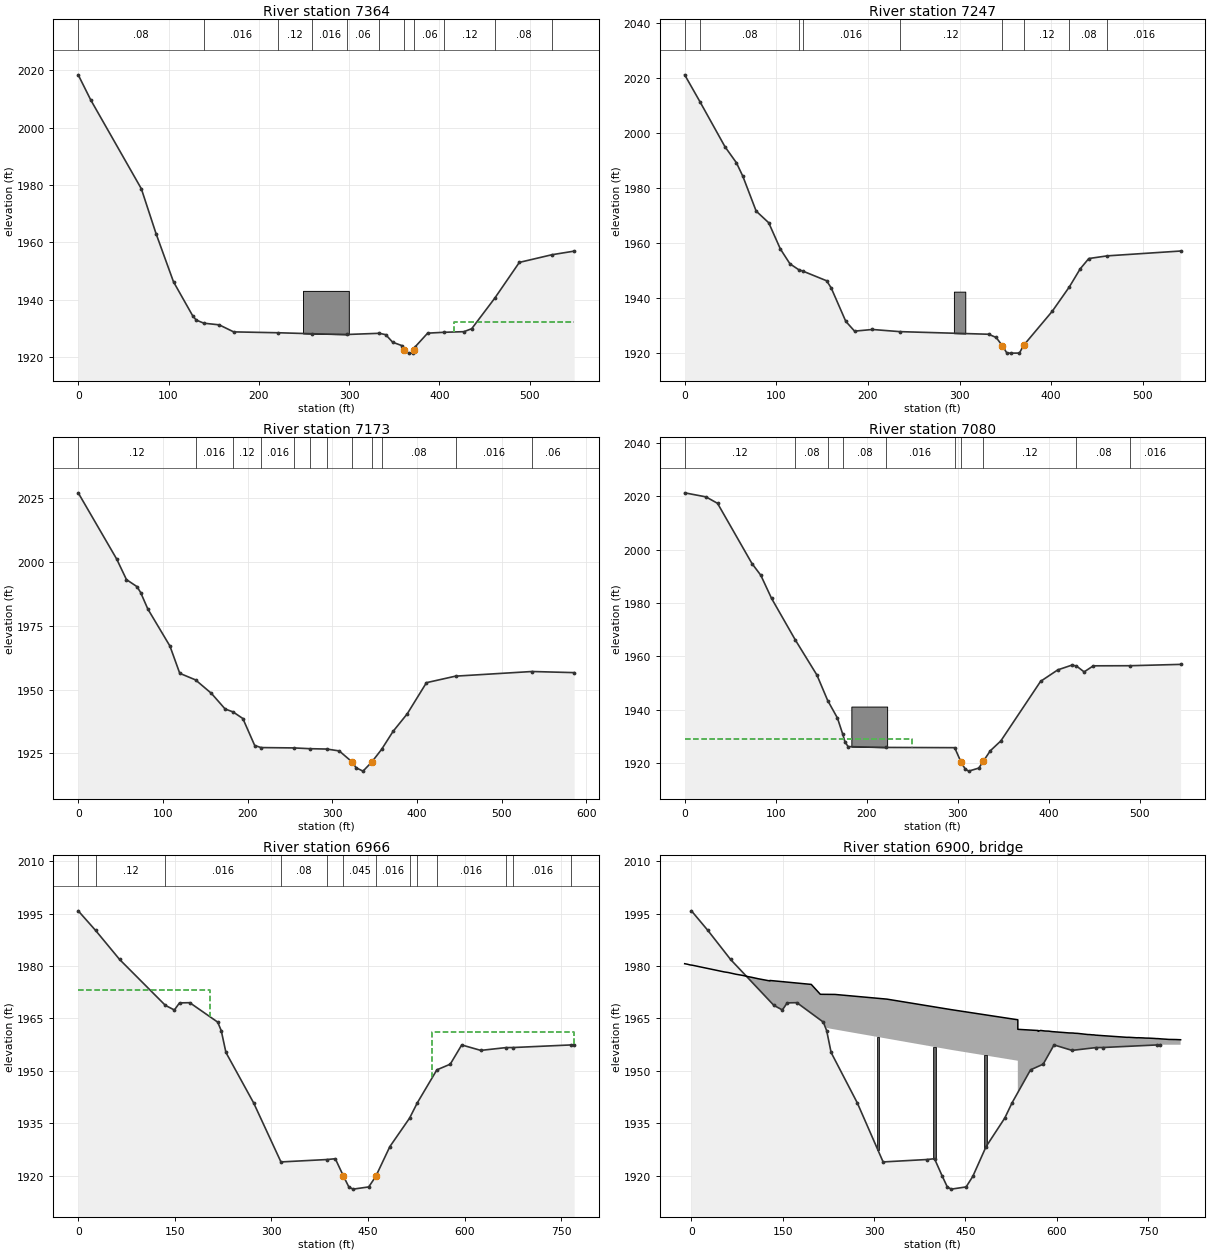
Type RM Length L Ch R = 1 ,7364    ,82.2,116.9,124
XS GIS Cut Line= 4
     2176514.078      291505.728     2176761.895      291705.211
     2176889.008      291818.469     2176948.056      291832.416
#Sta/Elev= 30
       0 2018.45    13.9 2009.67    69.9 1978.73    86.2 1963.07   105.5 1946.29
   126.6 1934.53   130.6 1932.96   139.2 1931.86   156.1 1931.29   172.1 1928.84
   221.6 1928.53   258.9 1928.19   297.7 1927.93   333.4 1928.34   340.5 1927.86
   348.2 1925.22   358.5 1924.04   361.2 1922.37     366 1921.43   370.6  1921.5
   372.2 1922.57   373.2 1923.67   386.9  1928.4   405.5  1928.7   427.1 1928.91
   435.7 1929.95   461.1 1940.55   488.4 1953.06   524.6 1955.74   549.1 1956.99
#Mann= 11 ,-1 , 0
       0     .08       0   139.2    .016       0   221.6     .12       0
   258.9    .016       0   297.7     .06       0   333.4     .06       0
   361.2     .04       0   372.2     .06       0   405.5     .12       0
   461.1     .08       0   524.6    .016       0
#XS Ineff= 2 , 0
                           416.3         1932.41
Permanent Ineff=
       F       F
#Block Obstruct= 1 ,-1
   248.9   299.61943.132
Bank Sta=361.2,372.2
XS Rating Curve= 0 ,0
Exp/Cntr=0.3,0.1

Type RM Length L Ch R = 1 ,7247    ,75.9,74.2,76.3
XS GIS Cut Line= 4
      2176491.23      291521.546     2176676.653      291770.241
     2176754.777      291875.487     2176854.658      291872.893
#Sta/Elev= 30
       0    2021    16.6 2011.27      44 1994.86    56.5 1989.03    63.5 1984.12
      78 1971.49    91.7 1967.25   104.4 1957.74   114.9 1952.32   124.5 1950.18
   129.2 1949.65   154.9 1946.17   159.9 1943.56   175.8 1931.43   185.4 1927.87
   204.9 1928.47   234.7 1927.69   331.7 1926.74   339.9 1925.57   346.8 1922.52
   351.6  1919.9     356 1919.88   365.3  1919.9   369.8 1922.68   401.1 1935.08
   419.9 1944.01   431.6  1950.5     441 1954.25   461.1 1955.22   541.2 1956.98
#Mann= 9 ,-1 , 0
       0     .12       0    16.6     .08       0   124.5     .12       0
   129.2    .016       0   234.7     .12       0   346.8     .04       0
   369.8     .12       0   419.9     .08       0   461.1    .016       0
#Block Obstruct= 1 ,-1
   293.8   306.21942.219
Bank Sta=346.8,369.8
XS Rating Curve= 0 ,0
Exp/Cntr=0.3,0.1

Type RM Length L Ch R = 1 ,7173    ,110.8,92.8,85.3
BEGIN DESCRIPTION:
Not Burnt
END DESCRIPTION:
XS GIS Cut Line= 5
     2176421.472      291573.596     2176610.103      291798.529
     2176653.395      291860.008     2176681.128      291892.118
     2176855.739      291888.833
#Sta/Elev= 30
       0 2026.99    45.4 2001.09      57 1993.02    69.4 1990.28    73.7 1987.98
    82.2 1981.52   108.3 1967.02   119.9 1956.35   138.5 1953.78   157.2 1948.53
   173.5 1942.38   182.8 1941.25   194.4 1938.66   208.4  1928.1   215.9 1927.29
     255 1927.15   273.6 1926.85   293.6 1926.71   308.2 1925.98   323.5 1921.63
   328.2 1919.37   336.3 1918.07   346.4 1921.54   358.2 1926.57   371.7 1933.59
   388.5 1940.49   411.2 1952.69   445.5 1955.24   535.8 1957.06   585.6 1956.62
#Mann= 12 ,-1 , 0
       0     .12       0   138.5    .016       0   182.8     .12       0
   215.9    .016       0     255     .06       0   273.6     .12       0
   293.6     .08       0   323.5     .04       0   346.4     .08       0
   358.2     .08       0   445.5    .016       0   535.8     .06       0
Bank Sta=323.5,346.4
XS Rating Curve= 0 ,0
Exp/Cntr=0.3,0.1

Type RM Length L Ch R = 1 ,7080    ,137.7,105.5,85.3
BEGIN DESCRIPTION:
Not Burnt
END DESCRIPTION:
XS GIS Cut Line= 4
     2176287.904      291704.819     2176534.272      291863.639
     2176617.661      291914.956     2176770.493      291898.519
#Sta/Elev= 30
       0 2021.22    23.4  2019.7    36.1 2017.29    73.9 1994.76    83.6 1990.38
    95.4 1981.73   121.5 1966.17   145.3 1952.99   157.1 1943.47   167.8 1936.93
   173.7 1930.79   176.1 1927.97   179.5 1926.22   221.2 1925.91   296.6 1925.82
   303.3 1920.63   308.2 1917.81     312 1917.04   323.1 1918.18   328.2 1920.81
   335.7 1924.65   347.3 1928.35     391 1950.66   409.9 1954.95   425.6 1956.75
   430.4 1956.38   438.8 1954.19   448.9 1956.46   489.6  1956.5   544.8    1957
#Mann= 10 ,-1 , 0
       0     .12       0   121.5     .08       0   157.1     .12       0
   173.7     .08       0   221.2    .016       0   296.6     .12       0
   303.3    .045       0   328.2     .12       0   430.4     .08       0
   489.6    .016       0
#XS Ineff= 2 , 0
          249.66 1928.95
Permanent Ineff=
       F       F
#Block Obstruct= 1 ,-1
   183.1   222.41941.211
Bank Sta=303.3,328.2
XS Rating Curve= 0 ,0
Exp/Cntr=0.5,0.3

Type RM Length L Ch R = 1 ,6966    ,152.5,147.4,150.7
BEGIN DESCRIPTION:
Merged US Survey WAC082BU
END DESCRIPTION:
XS GIS Cut Line= 5
     2176050.582      291932.411      2176214.51      291978.739
     2176437.833      291963.296     2176649.276      291916.969
     2176807.265      291895.587
#Sta/Elev= 30
       0 1995.78      27 1990.17    64.2 1981.88   135.3 1968.74   149.3 1967.41
   157.3 1969.44   173.2  1969.5   216.6 1963.94   222.1  1961.5   229.4 1955.25
   272.4 1940.83   314.8 1923.94   386.6 1924.63   399.2 1924.86   411.9 1919.88
   420.3 1916.76   426.9 1916.16   451.1 1916.79   462.1 1919.81   483.9 1928.32
   514.6 1936.49   526.6 1940.86   556.9 1950.28   577.7 1951.91   595.5 1957.41
   625.1 1955.85   664.3 1956.65   675.4 1956.67   764.7 1957.41   770.1 1957.47
#Mann= 13 ,-1 , 0
       0     .08       0      27     .12       0   135.3    .016       0
   314.8     .08       0   386.6    .016       0   411.9    .045       0
   462.1    .016       0   514.6     .12       0   526.6     .08       0
   556.9    .016       0   664.3     .08       0   675.4    .016       0
   764.7     .06       0
#XS Ineff= 2 , 0
           204.8    1973     549            1961
Permanent Ineff=
       F       F
Bank Sta=411.9,462.1
XS Rating Curve= 0 ,0
Exp/Cntr=0.5,0.3

Type RM Length L Ch R = 3 ,6900    ,,,
BEGIN DESCRIPTION:
Merged DS Survey WAC080RP
Interstate 64
END DESCRIPTION:
Bridge Culvert--1,0,-1,-1, 0
Deck Dist Width WeirC Skew NumUp NumDn MinLoCord MaxHiCord MaxSubmerge Is_Ogee
1,120,2.6,0, 195, 196, , , 0.98, 0, 0,0,,
   -11.1    -6.8    -2.2     1.1    10.9    14.2    31.6    37.2    43.8    47.6
    53.6    60.4    73.3    83.1    90.3    92.4      93      97    98.8   109.4
   119.2   122.5  128.69  128.79   196.8  211.68  235.85  321.02   426.3  536.05
  536.05  569.42  569.52   570.2   571.6     572   573.5   574.9   575.6   576.8
   577.7   579.5   580.6   583.4   583.5   586.3   586.8   590.1   591.4   592.1
   593.4   595.3   596.8   597.8   599.3   600.1   600.7   603.2   603.4   603.5
   604.3   606.4   606.7   607.2   609.3     610   611.1   612.1   613.4     615
   615.1     619     620     623   623.6   625.3   626.5   626.7   626.9   629.3
   632.2   633.3   634.2   637.7   639.6   640.1   640.4   641.5     643   643.5
   644.2   645.7   646.9   648.4   648.9   651.1   653.5   653.7   653.8   654.1
   656.4   657.1   658.2   660.5   661.8   662.8   663.9   664.5   666.7   667.1
   667.4   669.8   696.6   697.8   699.3     700   701.2     702   704.6   704.7
   707.3     708   709.3     710   711.4   712.7   713.9   714.8   715.3   717.3
     718   718.2   718.5   721.6   723.2   723.4   726.1   727.8   728.4   729.9
   731.4   731.8   734.1   736.8   737.1   738.6   741.8     742   742.1   742.6
   744.8   745.4   746.4   747.5   752.2   755.6   755.7     759   760.7   762.5
   763.3   765.4   765.8     766   766.3   768.4   769.5     771   771.6   772.9
   773.6   776.1   776.4     777   778.7   779.9   781.3   782.3   783.9   785.3
   786.4   786.8   787.7     789   790.3   791.6     793   793.8   794.2   795.2
   797.3   798.4   800.8   801.9   803.4
 1980.65 1980.51  1980.3 1980.23 1979.87 1979.72 1979.14 1978.91 1978.68 1978.51
 1978.31 1978.13 1977.63 1977.34 1977.08 1976.98 1976.95 1976.82 1976.77 1976.36
 1976.03 1975.94 1975.73 1975.86 1974.73  1971.9 1971.86 1970.52 1967.52 1964.61
 1961.88 1961.54 1961.32 1961.39 1961.46 1961.46 1961.56 1961.53 1961.53 1961.51
 1961.49 1961.42  1961.4 1961.38 1961.37 1961.36 1961.36 1961.26 1961.24 1961.23
 1961.21 1961.18 1961.16 1961.15 1961.13 1961.12 1961.11 1961.08 1961.07 1961.07
 1961.06 1961.04 1961.03 1961.03    1961 1960.99 1960.98 1960.98 1960.96 1960.93
 1960.93 1960.87 1960.85 1960.84 1960.84 1960.83 1960.82 1960.82 1960.82 1960.76
 1960.75 1960.74 1960.72 1960.65 1960.63 1960.62 1960.62 1960.59 1960.56 1960.55
 1960.54  1960.5 1960.47 1960.44 1960.43 1960.39 1960.38 1960.38 1960.38 1960.38
 1960.32 1960.31  1960.3  1960.3 1960.26 1960.24 1960.21 1960.21 1960.18 1960.18
 1960.17 1960.14  1959.8 1959.78 1959.76 1959.75 1959.73 1959.73 1959.72 1959.72
 1959.68 1959.68 1959.66 1959.65 1959.63 1959.62  1959.6 1959.59 1959.59  1959.6
  1959.6  1959.6  1959.6 1959.56 1959.54 1959.54 1959.51 1959.51  1959.5 1959.48
 1959.46 1959.46 1959.48 1959.47 1959.46 1959.45 1959.42 1959.42 1959.42 1959.41
 1959.39 1959.38 1959.38 1959.37 1959.35 1959.33 1959.33 1959.29 1959.27 1959.24
 1959.23 1959.23 1959.23 1959.23 1959.22 1959.18 1959.17 1959.15 1959.14 1959.13
 1959.12 1959.09 1959.09 1959.08 1959.06 1959.04 1959.03 1959.01 1958.99 1958.99
 1958.99 1958.99 1958.99 1958.98 1958.97 1958.96 1958.97 1958.97 1958.97 1958.96
 1958.95 1958.94 1958.91 1958.91  1958.9
                                                                                
                                                                                
                                 1963.39 1962.57 1961.83 1959.23 1956.01 1952.89
                                                                                
                                                                                
                                                                                
                                                                                
                                                                                
                                                                                
                                                                                
                                                                                
                                                                                
                                                                                
                                                                                
                                                                                
                                                                                
                                                                                
                                                                                
                                                                                
                                        
   -11.1    -6.8    -2.2     1.1    10.9    14.2    31.6    37.2    43.8    47.6
    53.6    60.4    73.3    83.1    90.3    92.4      93      97    98.8   109.4
   119.2   122.5  128.69  128.79   164.8  191.68  215.85  301.02   406.3  508.38
  536.05  546.05  569.42  569.52   570.2   571.6     572   573.5   574.9   575.6
   576.8   577.7   579.5   580.6   583.4   583.5   586.3   586.8   590.1   591.4
   592.1   593.4   595.3   596.8   597.8   599.3   600.1   600.7   603.2   603.4
   603.5   604.3   606.4   606.7   607.2   609.3     610   611.1   612.1   613.4
     615   615.1     619     620     623   623.6   625.3   626.5   626.7   626.9
   629.3   632.2   633.3   634.2   637.7   639.6   640.1   640.4   641.5     643
   643.5   644.2   645.7   646.9   648.4   648.9   651.1   653.5   653.7   653.8
   654.1   656.4   657.1   658.2   660.5   661.8   662.8   663.9   664.5   666.7
   667.1   667.4   669.8   696.6   697.8   699.3     700   701.2     702   704.6
   704.7   707.3     708   709.3     710   711.4   712.7   713.9   714.8   715.3
   717.3     718   718.2   718.5   721.6   723.2   723.4   726.1   727.8   728.4
   729.9   731.4   731.8   734.1   736.8   737.1   738.6   741.8     742   742.1
   742.6   744.8   745.4   746.4   747.5   752.2   755.6   755.7     759   760.7
   762.5   763.3   765.4   765.8     766   766.3   768.4   769.5     771   771.6
   772.9   773.6   776.1   776.4     777   778.7   779.9   781.3   782.3   783.9
   785.3   786.4   786.8   787.7     789   790.3   791.6     793   793.8   794.2
   795.2   797.3   798.4   800.8   801.9   803.4
 1980.65 1980.51  1980.3 1980.23 1979.87 1979.72 1979.14 1978.91 1978.68 1978.51
 1978.31 1978.13 1977.63 1977.34 1977.08 1976.98 1976.95 1976.82 1976.77 1976.36
 1976.03 1975.94 1975.73 1975.86 1974.73  1971.9 1971.86 1970.52 1967.52 1964.61
 1961.88 1963.56 1961.54 1961.32 1961.39 1961.46 1961.46 1961.56 1961.53 1961.53
 1961.51 1961.49 1961.42  1961.4 1961.38 1961.37 1961.36 1961.36 1961.26 1961.24
 1961.23 1961.21 1961.18 1961.16 1961.15 1961.13 1961.12 1961.11 1961.08 1961.07
 1961.07 1961.06 1961.04 1961.03 1961.03    1961 1960.99 1960.98 1960.98 1960.96
 1960.93 1960.93 1960.87 1960.85 1960.84 1960.84 1960.83 1960.82 1960.82 1960.82
 1960.76 1960.75 1960.74 1960.72 1960.65 1960.63 1960.62 1960.62 1960.59 1960.56
 1960.55 1960.54  1960.5 1960.47 1960.44 1960.43 1960.39 1960.38 1960.38 1960.38
 1960.38 1960.32 1960.31  1960.3  1960.3 1960.26 1960.24 1960.21 1960.21 1960.18
 1960.18 1960.17 1960.14  1959.8 1959.78 1959.76 1959.75 1959.73 1959.73 1959.72
 1959.72 1959.68 1959.68 1959.66 1959.65 1959.63 1959.62  1959.6 1959.59 1959.59
  1959.6  1959.6  1959.6  1959.6 1959.56 1959.54 1959.54 1959.51 1959.51  1959.5
 1959.48 1959.46 1959.46 1959.48 1959.47 1959.46 1959.45 1959.42 1959.42 1959.42
 1959.41 1959.39 1959.38 1959.38 1959.37 1959.35 1959.33 1959.33 1959.29 1959.27
 1959.24 1959.23 1959.23 1959.23 1959.23 1959.22 1959.18 1959.17 1959.15 1959.14
 1959.13 1959.12 1959.09 1959.09 1959.08 1959.06 1959.04 1959.03 1959.01 1958.99
 1958.99 1958.99 1958.99 1958.99 1958.98 1958.97 1958.96 1958.97 1958.97 1958.97
 1958.96 1958.95 1958.94 1958.91 1958.91  1958.9
                                                                                
                                                                                
                                 1963.39 1962.57 1961.83 1959.23 1956.01 1952.89
                                                                                
                                                                                
                                                                                
                                                                                
                                                                                
                                                                                
                                                                                
                                                                                
                                                                                
                                                                                
                                                                                
                                                                                
                                                                                
                                                                                
                                                                                
                                                                                
                                                
Pier Skew, UpSta & Num, DnSta & Num=  ,306, 2 ,267, 2 , 0 , 0 , 0 ,,
       4       4
    1910    1965
       4       4
    1910    1965
Pier Skew, UpSta & Num, DnSta & Num=  ,399, 2 ,362, 2 , 0 , 0 , 0 ,,
       4       4
    1910    1965
       4       4
    1910    1965
Pier Skew, UpSta & Num, DnSta & Num=  ,483, 2 ,445, 2 , 0 , 0 , 0 ,,
       4       4
    1910    1965
       4       4
    1910    1965
BR Coef=-1 , 1 , 0 ,, 0 ,,,0.8,0,1.2,0,
WSPro=,,,, 1 ,,,, 0 ,,,, 0 ,,,,-1 ,-1 ,-1 , 0 , 0 , 0 , 0 , 0
BC Design=,, 0 ,, 0 ,,0,,,,
BC HTab HWMax=0
BC HTab TWMax=0
BC HTab MaxFlow=0
BC Use User HTab Curves=0
BC User HTab FreeFlow(D)= 0

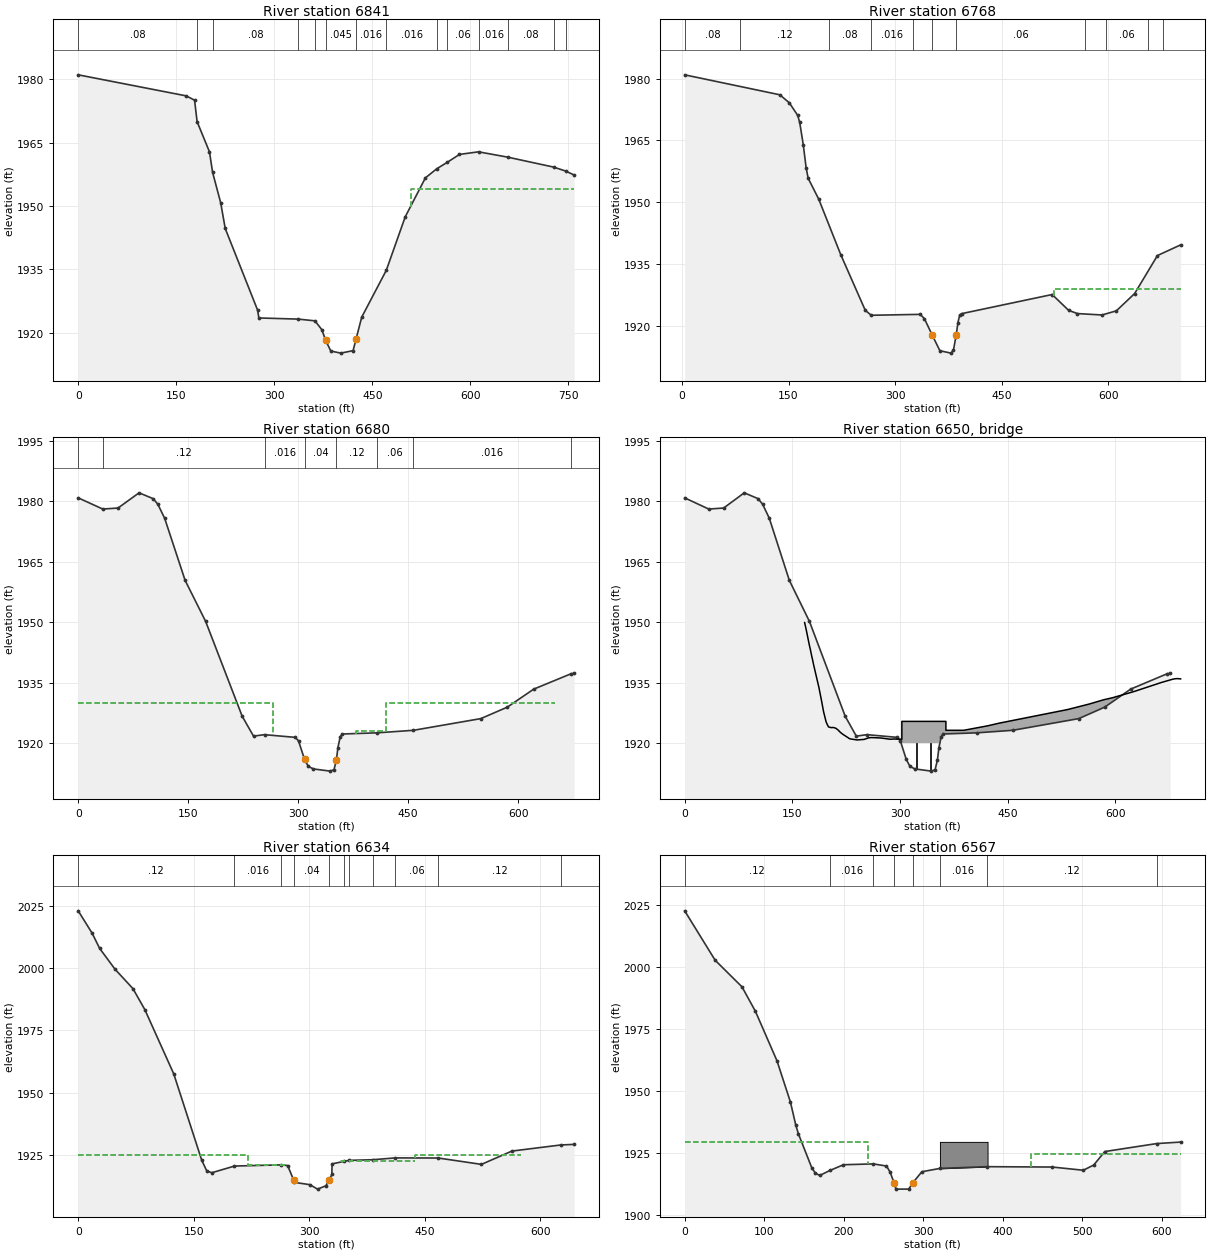
Type RM Length L Ch R = 1 ,6841    ,36.5,58.9,72.6
BEGIN DESCRIPTION:
Merged US Survey WAC078BD
END DESCRIPTION:
XS GIS Cut Line= 5
      2176008.97      292083.436     2176052.088      292086.184
     2176334.371      292091.336     2176555.284      292060.455
     2176758.446      292006.996
#Sta/Elev= 30
       0 1981.05   165.2 1976.07     178 1975.05   181.9 1969.96   200.8 1962.83
   205.6 1957.95     218 1950.76   224.9 1944.69   274.3 1925.43   276.4 1923.52
   336.7 1923.25   362.2 1922.84   372.7 1920.74   378.5 1918.24   386.4  1915.7
   401.7  1915.2   420.5 1915.79   425.1 1918.54   433.7 1923.71   471.3 1934.79
   500.3 1947.46   531.1 1956.66   548.6 1958.83   564.5 1960.34   583.3 1962.22
   612.4 1962.83   656.8 1961.58   727.5 1959.21   745.9 1958.27   758.7 1957.34
#Mann= 14 ,-1 , 0
       0     .08       0   181.9    .016       0   205.6     .08       0
   336.7    .016       0   362.2    .016       0   378.5    .045       0
   425.1    .016       0   471.3    .016       0   548.6     .08       0
   564.5     .06       0   612.4    .016       0   656.8     .08       0
   727.5    .016       0   745.9     .08       0
#XS Ineff= 2 , 0
             190 1962.28   508.4            1954
Permanent Ineff=
       F       F
Bank Sta=378.5,425.1
XS Rating Curve= 0 ,0
Exp/Cntr=0.5,0.3

Type RM Length L Ch R = 1 ,6768    ,81.5,88.1,89
BEGIN DESCRIPTION:
Not Burnt
END DESCRIPTION:
XS GIS Cut Line= 5
     2176011.921       292086.63     2176051.898      292089.178
     2176357.274      292122.616     2176406.727      292141.574
     2176701.322      292185.525
#Sta/Elev= 30
     3.8 1980.94   137.7 1976.09     151 1974.15   162.8 1971.11   165.7 1969.38
   170.7 1963.96   174.7  1958.4   177.6  1955.8   192.5 1950.72   223.5 1937.23
     258 1923.71   266.4 1922.52   335.3 1922.74   341.2  1921.7   352.3 1917.66
     363  1913.9   378.6 1913.32   382.1 1914.06   385.9 1917.67   388.4 1920.76
   390.9 1922.58   393.5 1922.91     521 1927.56   544.2 1923.71   556.6 1922.93
   591.2 1922.59   611.4  1923.6   637.1  1927.8   669.2 1937.03   701.8 1939.62
#Mann= 11 ,-1 , 0
     3.8     .08       0    81.6     .12       0     207     .08       0
   266.4    .016       0   325.8     .12       0   352.3     .04       0
   385.9     .06       0   567.5     .12       0     597     .06       0
   656.2     .08       0     677    .016       0
#XS Ineff= 2 , 0
                          523.89         1928.81
Permanent Ineff=
       F       F
Bank Sta=352.3,385.9
XS Rating Curve= 0 ,0
Exp/Cntr=0.5,0.3

Type RM Length L Ch R = 1 ,6680    ,54.3,46.1,42.2
BEGIN DESCRIPTION:
Merged DS Survey WAC072BU
END DESCRIPTION:
XS GIS Cut Line= 4
     2176004.893      292085.501      2176294.96      292191.331
     2176347.304      292208.951     2176659.587      292217.261
#Sta/Elev= 30
       0 1980.87    33.5  1978.1    54.3 1978.35      83 1982.12   102.2 1980.68
   108.6 1979.29   117.9 1975.81   145.8 1960.42   173.8 1950.25   223.7 1926.71
   239.1 1921.81   254.1 1922.17     296  1921.5   300.5 1920.61   308.7 1916.03
   313.9 1914.29   320.9 1913.67   343.8 1913.13   348.9 1913.49   352.1  1915.9
   354.2 1918.97   357.4 1921.68     360 1922.33     407 1922.62   457.2 1923.25
   549.1 1926.15   585.2 1928.99   621.2 1933.45   672.3 1937.28   676.4 1937.35
#Mann= 8 ,-1 , 0
       0     .08       0    33.5     .12       0   254.1    .016       0
   308.7     .04       0   352.1     .12       0     407     .06       0
   457.2    .016       0   672.3     .12       0
#XS Ineff= 4 ,-1
       0     265    1930     265   285.7 1921.52   378.4     420    1923
     420     650    1930
Permanent Ineff=
       F       F       F       F
Bank Sta=308.7,352.1
XS Rating Curve= 0 ,0
Exp/Cntr=0.5,0.3

Type RM Length L Ch R = 3 ,6650    ,,,
BEGIN DESCRIPTION:
Merged DS Survey WAC070RP
Exit to Highway 60
END DESCRIPTION:
Bridge Culvert--1,0,-1,-1, 0
Deck Dist Width WeirC Skew NumUp NumDn MinLoCord MaxHiCord MaxSubmerge Is_Ogee
10,30,2.6,0, 44, 60, , , 0.98, 0, 0,0,,
   167.1   169.3   173.7   175.1   177.1     178   179.7     187   190.3   193.6
     197   198.2   200.3     204   206.9   210.2   213.5   216.9   220.2     230
   240.1     250     256     260   273.2   286.5  290.41  302.55  302.55  363.91
  363.91  388.74     422   438.6   533.3   563.3   583.5   596.2     626   664.4
   678.6   682.4   686.2   690.9
 1949.97 1948.19 1944.35 1943.26 1941.54 1940.87 1939.43 1933.87  1930.9 1927.78
 1925.36 1924.86  1924.1 1923.91 1923.95 1923.79 1923.36 1922.74 1922.28 1921.14
 1920.86 1920.99 1921.37 1921.45 1921.35 1921.03 1921.09 1921.04 1925.46 1925.46
 1923.25 1923.25 1924.36 1925.04 1928.39 1929.75 1930.81 1931.33 1932.86 1935.12
 1935.85 1936.01 1936.07 1935.99
                                                                                
                                                                                
                                                                 1920.09 1920.09
                                                                                
                                
    18.1    20.7    24.1    30.7      34      40    47.3    50.6    53.9    57.2
    61.3    70.5    73.8    77.1    87.1    94.4      97   102.2   110.5   116.9
   126.9   140.1   142.3   146.7   148.1   152.7     160   163.3   166.6     170
   173.3     177   179.9   183.2   186.5   189.9   193.2     203   213.1     223
     229     233   246.2   259.5  275.55  275.55  336.91  336.91  361.74     395
   411.6   506.3   536.3   556.5   569.2     599   637.4   651.6   659.2   663.9
 2017.55 2016.09 2014.33 2010.37 2008.73  2006.1 2002.35 2000.85 1999.58 1998.52
 1997.43  1994.4  1993.2 1991.71 1986.48 1981.82 1980.25 1976.86  1971.2 1966.57
 1959.89 1949.97 1948.19 1944.35 1943.26 1939.43 1933.87  1930.9 1927.78 1925.36
  1924.1 1923.91 1923.95 1923.79 1923.36 1922.74 1922.28 1921.14 1920.86 1920.99
 1921.37 1921.45 1921.35 1921.03 1921.04 1925.46 1925.46 1923.25 1923.25 1924.36
 1925.04 1928.39 1929.75 1930.81 1931.33 1932.86 1935.12 1935.85 1936.07 1935.99
                                                                                
                                                                                
                                                                                
                                                                                
                                         1920.09 1920.09
                                                                                
Pier Skew, UpSta & Num, DnSta & Num=  ,323, 2 ,295.95, 2 , 0 , 0 , 0 ,,
     1.5     1.5
    1910    1923
     1.5     1.5
    1910    1923
Pier Skew, UpSta & Num, DnSta & Num=  ,343, 2 ,315.95, 2 , 0 , 0 , 0 ,,
     1.5     1.5
    1910    1923
     1.5     1.5
    1910    1923
BR Coef=-1 , 1 , 0 ,, 0 ,,,0.8,0,1.33,0,
WSPro=,,,, 1 ,,,, 0 ,,,, 0 ,,,,-1 ,-1 ,-1 , 0 , 0 , 0 , 0 , 0
BC Design=,, 0 ,, 0 ,,0,,,,
BC HTab HWMax=0
BC HTab TWMax=0
BC HTab MaxFlow=0
BC Use User HTab Curves=0
BC User HTab FreeFlow(D)= 0

Type RM Length L Ch R = 1 ,6634    ,47.6,66.5,74.7
BEGIN DESCRIPTION:
Merged US Survey WAC068BD
END DESCRIPTION:
XS GIS Cut Line= 4
     2175983.019      292195.004     2176242.101      292230.798
     2176332.168      292241.967     2176614.634      292314.527
#Sta/Elev= 30
       0 2022.95      18    2014    27.9 2007.85    47.8 1999.52      71 1991.76
    86.5 1983.32     124 1957.57   160.4 1922.86     167 1918.55   173.6 1917.89
   202.9 1920.56   263.1 1921.03   271.9 1920.76  279.66 1915.03   280.8 1914.01
   300.8 1913.09   310.7  1911.3   321.5 1912.63   325.7 1914.85   329.3 1917.18
   329.6 1921.43   345.7 1922.48   351.9 1922.84   382.8  1923.1   411.6 1923.83
   467.5 1923.78   523.5 1921.23   563.1 1926.57   626.7 1929.02   643.9 1929.25
#Mann= 11 ,-1 , 0
       0     .12       0   202.9    .016       0   263.1     .12       0
  279.66     .04       0   325.7    .016       0   345.7     .12       0
   351.9     .06       0   382.8     .12       0   411.6     .06       0
   467.5     .12       0   626.7     .08       0
#XS Ineff= 4 ,-1
       0     220    1925     220  269.78 1921.04   340.8     437  1922.4
     437     575    1925
Permanent Ineff=
       F       F       F       F
Bank Sta=279.66,325.7
XS Rating Curve= 0 ,0
Exp/Cntr=0.5,0.3

Type RM Length L Ch R = 1 ,6567    ,43.3,47.8,50.1
XS GIS Cut Line= 4
     2175978.406      292209.337     2176223.908      292270.362
     2176280.725      292304.732     2176568.313      292404.336
#Sta/Elev= 30
       0 2022.65    38.3 2002.74    72.1    1992      89 1982.12   116.1 1962.18
     133 1945.56   139.7 1936.31   143.1 1932.69     160 1918.94   164.5 1916.87
   169.9 1915.99   182.7    1918   199.7  1920.3   237.1 1920.64   253.8 1919.78
   258.2 1917.44   263.3 1913.04   264.6 1912.37   265.5 1910.47   281.8 1910.49
   286.8    1913   298.3 1917.48   320.8 1918.81   380.1 1919.52   462.4 1919.37
   501.3 1918.08   514.5  1920.2   528.3 1925.62   593.6 1928.83   623.7 1929.44
#Mann= 8 ,-1 , 0
       0     .12       0   182.7    .016       0   237.1     .06       0
   263.3    .045       0   286.8     .12       0   320.8    .016       0
   380.1     .12       0   593.6    .016       0
#XS Ineff= 2 , 0
          230.36 1929.62  435.77         1924.45
Permanent Ineff=
       F       F
#Block Obstruct= 1 ,-1
     321   380.91929.518
Bank Sta=263.3,286.8
XS Rating Curve= 0 ,0
Exp/Cntr=0.3,0.1