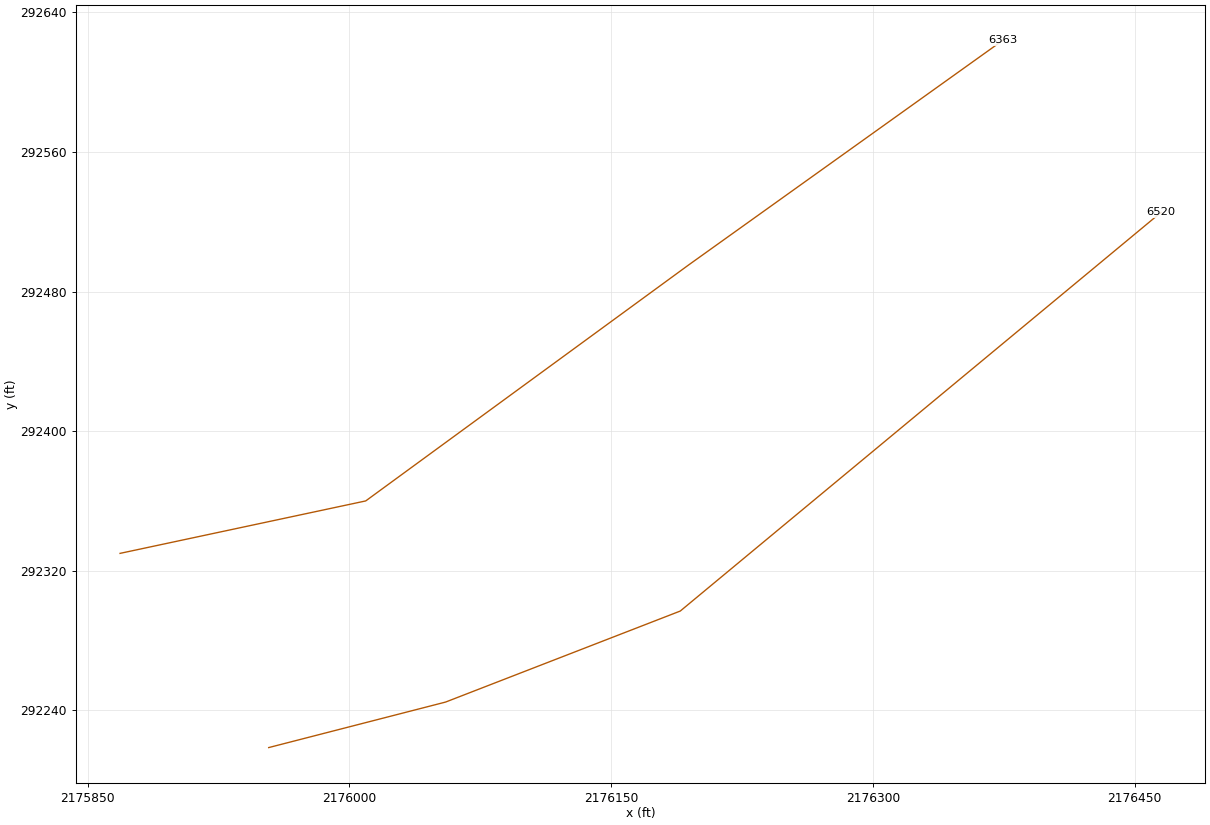
HEC-RAS study WADESCK1.prj: WADESCK1

--- WADESCK1.g01 (geometry) --- (continued)

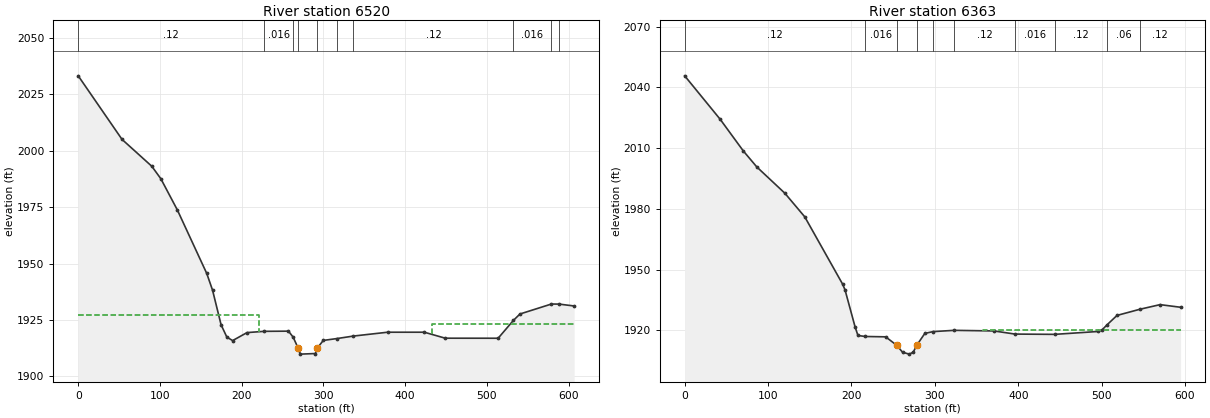
Type RM Length L Ch R = 1 ,6520    ,157.4,156.5,156
BEGIN DESCRIPTION:
E
END DESCRIPTION:
XS GIS Cut Line= 4
     2175953.814      292218.729     2176055.173       292244.81
     2176189.657      292296.967     2176465.173      292525.427
#Sta/Elev= 30
       0  2033.2    53.6 2005.03      90 1993.13   101.1 1987.59   121.3 1973.75
   157.2 1945.66   164.3 1938.27   174.8 1922.87   181.8 1917.44   188.9 1915.88
   206.5 1919.42   227.6 1919.98   257.2 1920.06   262.9 1917.43   269.1  1912.5
   271.8 1909.88   290.1 1910.14   292.4 1912.52   299.8 1915.95   316.9  1916.8
   336.7 1917.89   378.6 1919.59   423.4 1919.59     449 1916.94   513.7 1916.92
   532.4 1924.83   540.4 1927.66   578.9 1932.08   588.3 1932.05   606.7 1931.21
#Mann= 10 ,-1 , 0
       0     .12       0   227.6    .016       0   262.9     .12       0
   269.1     .04       0   292.4     .12       0   316.9     .06       0
   336.7     .12       0   532.4    .016       0   578.9     .08       0
   588.3    .016       0
#XS Ineff= 2 , 0
          221.45 1927.09  432.84          1923.1
Permanent Ineff=
       F       F
Bank Sta=269.1,292.4
XS Rating Curve= 0 ,0
Exp/Cntr=0.3,0.1

Type RM Length L Ch R = 1 ,6363    ,86.7,86.8,87
BEGIN DESCRIPTION:
Not Burnt
END DESCRIPTION:
XS GIS Cut Line= 4
     2175868.618       292330.02     2176009.399      292360.074
     2176194.471      292495.319     2176374.797      292624.236
#Sta/Elev= 30
       0 2045.68    42.7 2024.15    70.3 2008.59    86.5 2000.68   120.1 1987.72
     144 1976.04   189.4  1942.8   192.3 1939.95   204.4 1921.61   207.8 1917.45
   216.6 1916.96     241 1916.79  254.17 1912.64   261.3 1909.17   269.3 1908.25
     274 1909.18   278.7 1912.87     288  1918.5   297.9 1919.37   323.3    1920
     371 1919.69   396.1 1918.15   443.7 1918.01   496.1 1919.44   500.1 1920.05
   506.6 1922.77   518.4 1927.36     546 1930.42   570.1 1932.69   594.7 1931.39
#Mann= 10 ,-1 , 0
       0     .12       0   216.6    .016       0  254.17    .045       0
   278.7     .12       0   297.9     .08       0   323.3     .12       0
   396.1    .016       0   443.7     .12       0   506.6     .06       0
     546     .12       0
#XS Ineff= 2 , 0
                           357.3         1920.13
Permanent Ineff=
       F       F
Bank Sta=254.17,278.7
XS Rating Curve= 0 ,0
Exp/Cntr=0.3,0.1