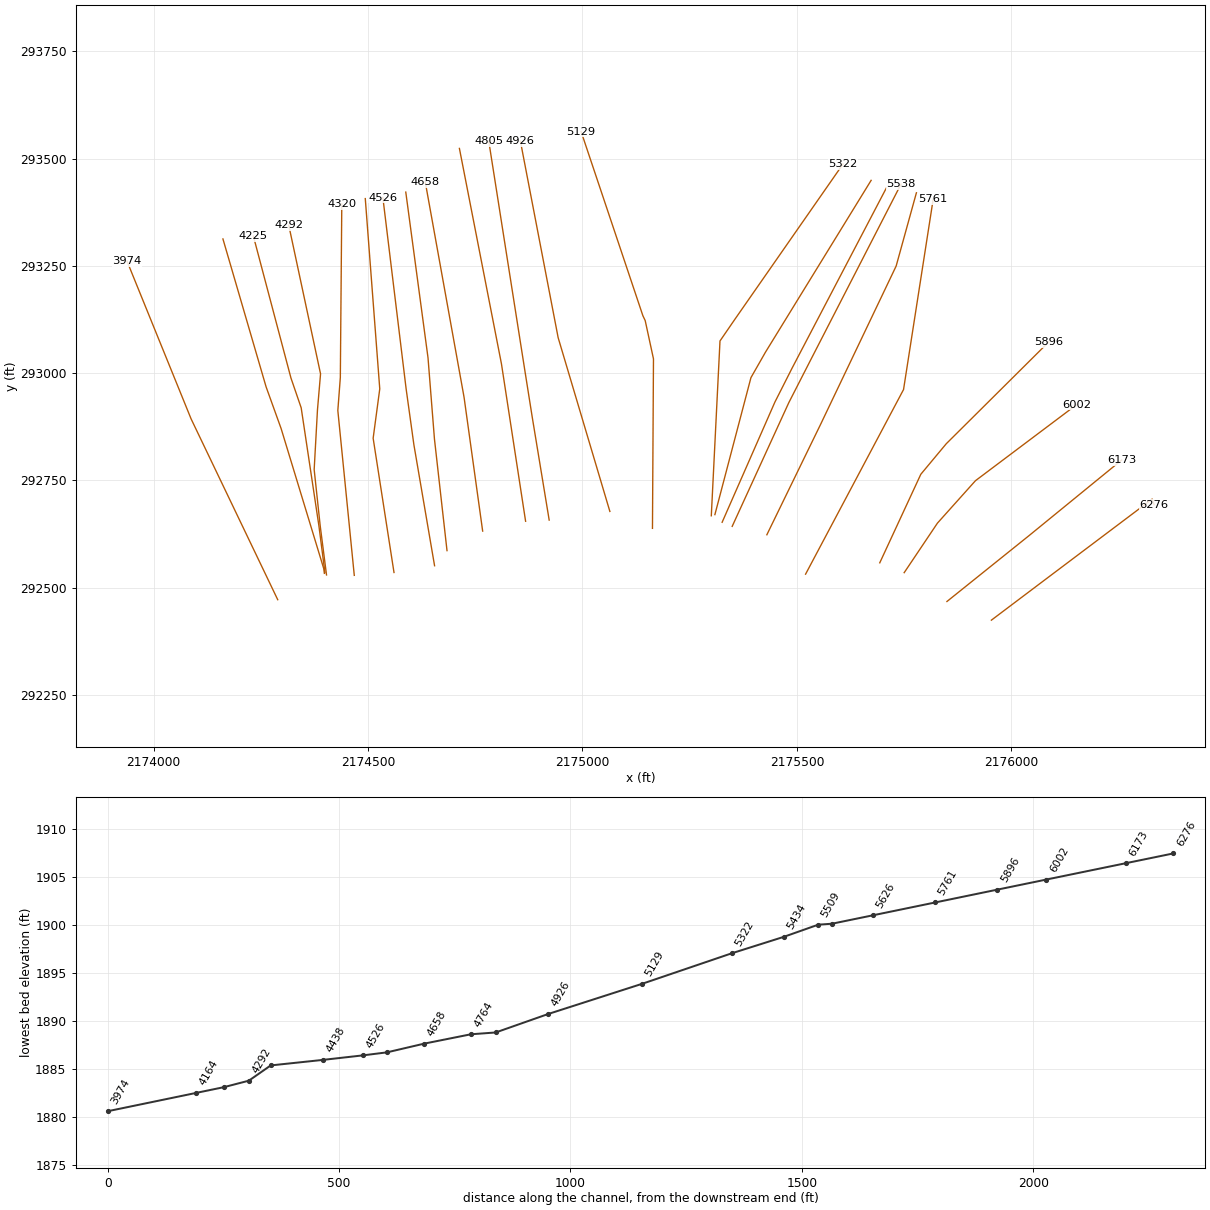
HEC-RAS study WADESCK1.prj: WADESCK1

--- WADESCK1.g01 (geometry) --- (continued)

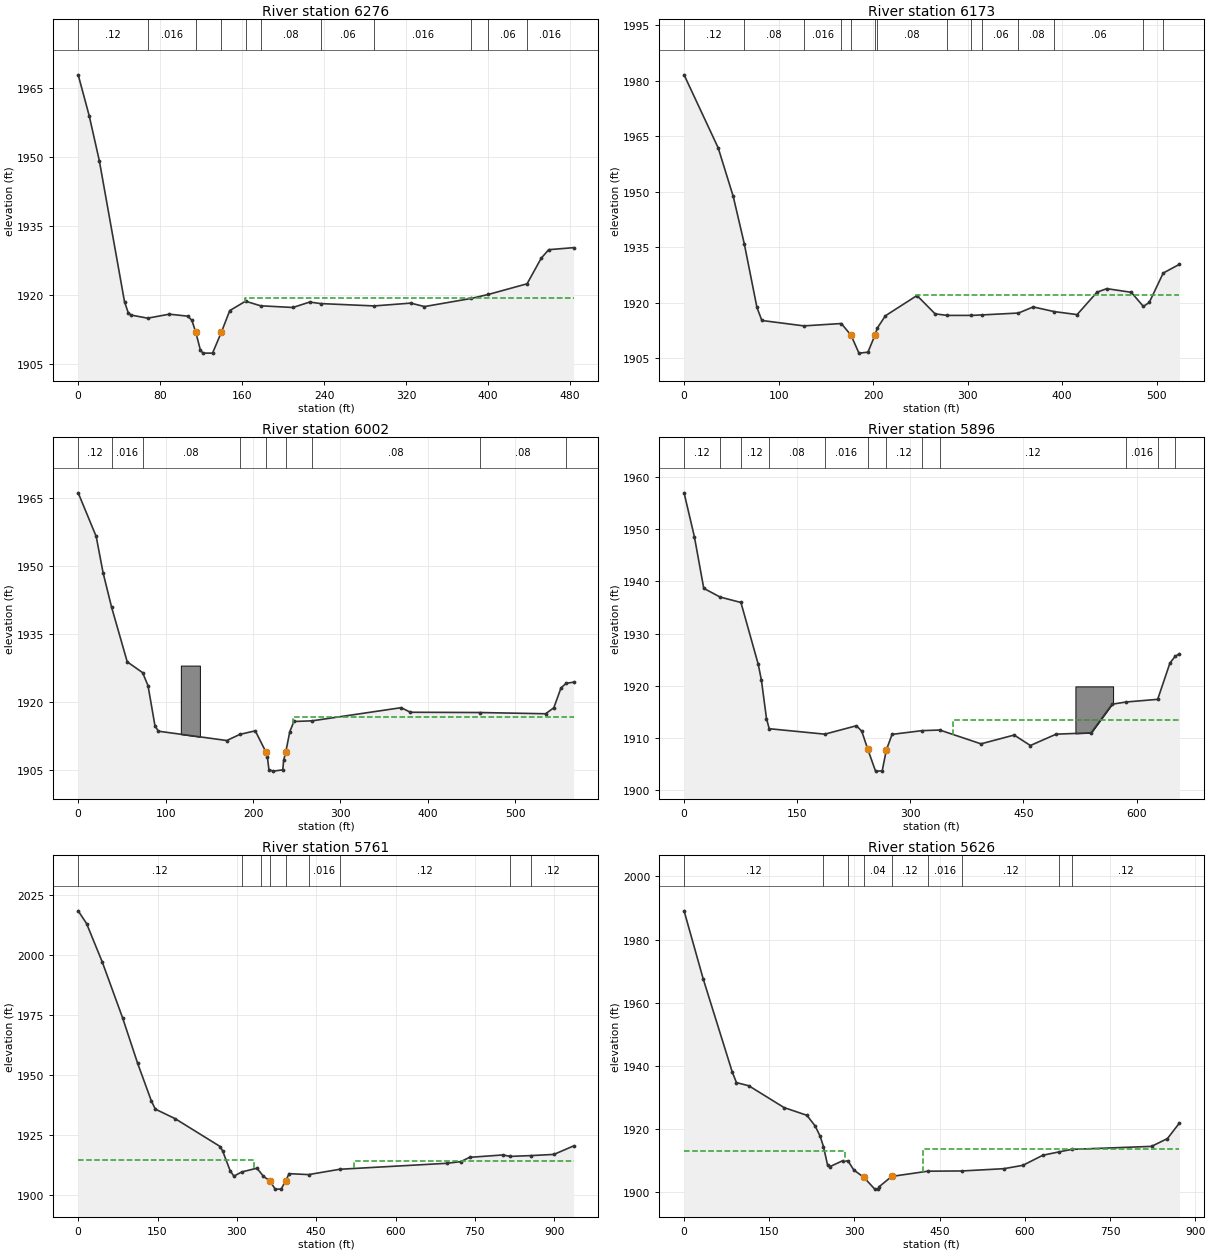
Type RM Length L Ch R = 1 ,6276    ,102,102.9,103.5
BEGIN DESCRIPTION:
Not Burnt
END DESCRIPTION:
XS GIS Cut Line= 4
     2175953.245      292424.138     2176079.028      292518.945
     2176328.134       292706.49     2176332.491      292693.078
#Sta/Elev= 30
       0 1967.83    10.7 1958.99    20.6 1949.23    45.2 1918.62    48.8 1916.25
    51.4 1915.73    67.8 1915.04    88.9 1915.91   106.8 1915.48   110.9  1914.6
   114.7 1912.02   119.2 1908.17   121.7 1907.46   131.1 1907.46   139.7 1911.99
   147.9 1916.69   163.3 1918.72     178 1917.73   209.5 1917.36   225.9 1918.54
   236.5 1918.21   288.8  1917.7   324.5 1918.31   337.9 1917.56   383.5 1919.32
   400.2 1920.19     438  1922.5   451.8 1928.05   459.1  1929.9   483.4 1930.34
#Mann= 11 ,-1 , 0
       0     .12       0    67.8    .016       0   114.7     .04       0
   139.7     .05       0   163.3     .12       0     178     .08       0
   236.5     .06       0   288.8    .016       0   383.5     .08       0
   400.2     .06       0     438    .016       0
#XS Ineff= 2 , 0
                           162.4         1919.42
Permanent Ineff=
       F       F
Bank Sta=114.7,139.7
XS Rating Curve= 0 ,0
Exp/Cntr=0.3,0.1

Type RM Length L Ch R = 1 ,6173    ,165.2,171.5,173.3
XS GIS Cut Line= 3
     2175849.636      292467.637     2176041.826      292621.864
     2176256.952      292797.444
#Sta/Elev= 30
       0 1981.62    36.1 1961.89      52 1948.78    63.7    1936    77.1 1918.77
    82.3 1915.26   126.7  1913.8   166.4 1914.44   176.7 1911.24     185 1906.44
   194.5 1906.69   202.2 1911.44   204.4  1913.2     213 1916.53   246.4    1922
   265.6 1917.05   278.4 1916.63     304 1916.63   315.7 1916.77   353.8 1917.27
   369.3 1918.92   391.8 1917.65   415.8 1916.85   436.8 1922.89   447.2 1923.86
   473.1 1922.87   485.9 1919.06   492.1 1920.12   506.9 1928.07   524.1 1930.44
#Mann= 14 ,-1 , 0
       0     .12       0    63.7     .08       0   126.7    .016       0
   166.4     .12       0   176.7     .04       0   202.2     .12       0
   204.4     .08       0   278.4     .06       0     304     .08       0
   315.7     .06       0   353.8     .08       0   391.8     .06       0
   485.9     .12       0   506.9    .016       0
#XS Ineff= 2 , 0
                           245.8         1922.06
Permanent Ineff=
       F       F
Bank Sta=176.7,202.2
XS Rating Curve= 0 ,0
Exp/Cntr=0.3,0.1

Type RM Length L Ch R = 1 ,6002    ,106.3,105.9,106.4
XS GIS Cut Line= 4
     2175749.982      292534.864     2175827.491      292650.336
     2175916.072      292749.199     2176151.762      292926.362
#Sta/Elev= 30
       0  1966.2    20.6 1956.56    28.5 1948.53    38.2 1940.95    56.1 1928.88
    73.7 1926.49    79.9  1923.6    87.8 1914.79    91.7 1913.56     170  1911.5
     185 1912.86   202.6 1913.64   214.5 1909.06   216.5 1907.76   218.2 1905.06
   223.2 1904.74     234 1905.02   235.1  1907.2   237.5 1909.01   242.1 1913.48
   246.8  1915.7   267.7 1915.85   369.4 1918.75   380.1 1917.74   459.8 1917.68
   534.7 1917.41   544.1 1918.74   552.3 1923.12   558.2 1924.14   566.7 1924.38
#Mann= 9 ,-1 , 0
       0     .12       0    38.2    .016       0    73.7     .08       0
     185    .016       0   214.5    .045       0   237.5     .12       0
   267.7     .08       0   459.8     .08       0   558.2    .016       0
#XS Ineff= 2 , 0
                           245.8         1916.71
Permanent Ineff=
       F       F
#Block Obstruct= 1 ,-1
   117.4   139.21928.052
Bank Sta=214.5,237.5
XS Rating Curve= 0 ,0
Exp/Cntr=0.3,0.1

Type RM Length L Ch R = 1 ,5896    ,132.4,134.8,140.6
XS GIS Cut Line= 4
     2175693.037        292557.8     2175788.737      292764.226
     2175848.054      292835.408     2176086.908      293072.679
#Sta/Elev= 30
       0 1956.91    13.7 1948.51    26.1 1938.65    47.8 1936.98    75.4 1935.94
    98.4 1924.09   102.6 1921.04   109.3 1913.74   112.9  1911.8   186.6 1910.76
   228.6 1912.37   235.6 1911.32   243.6 1907.87   253.9 1903.69   262.7 1903.73
   268.2 1907.72   275.8 1910.72   315.4 1911.43     339 1911.55   393.7 1908.91
   437.7 1910.59   459.2 1908.59   493.4 1910.76   539.8 1911.01   567.6 1916.49
   586.2 1916.91     628 1917.42   644.2 1924.34   651.2 1925.66   656.9 1926.12
#Mann= 12 ,-1 , 0
       0     .12       0    47.8    .016       0    75.4     .12       0
   112.9     .08       0   186.6    .016       0   243.6     .04       0
   268.2     .12       0   315.4    .016       0     339     .12       0
   586.2    .016       0     628     .12       0   651.2    .016       0
#XS Ineff= 2 , 0
                             357         1913.55
Permanent Ineff=
       F       F
#Block Obstruct= 1 ,-1
   518.9   568.91919.896
Bank Sta=243.6,268.2
XS Rating Curve= 0 ,0
Exp/Cntr=0.3,0.1

Type RM Length L Ch R = 1 ,5761    ,134,134.9,136
XS GIS Cut Line= 3
     2175520.093      292531.362     2175748.459       292961.71
      2175817.61      293405.677
#Sta/Elev= 30
       0 2018.44    15.9 2013.12    45.6 1997.04    84.2 1973.64   112.4 1954.83
   138.4 1939.08   145.9 1935.71     183 1931.78   268.4 1920.12   273.2  1918.2
   287.2 1910.08   294.3 1907.76   309.3 1909.53     338 1911.08   350.2 1907.69
   362.3 1905.81   372.4 1902.35   383.6 1902.35   392.4 1905.87   398.7  1908.8
   435.6 1908.41   494.2 1910.63   696.7 1913.12   723.3 1913.82   739.9 1915.61
     803 1916.61   816.3    1916   856.1 1916.34   899.3 1916.83   936.5 1920.37
#Mann= 9 ,-1 , 0
       0     .12       0   309.3    .016       0   346.5     .12       0
   362.3     .04       0   392.4     .12       0   435.6    .016       0
   494.2     .12       0   816.3    .016       0   856.1     .12       0
#XS Ineff= 2 , 0
          332.21  1914.3   521.7         1914.28
Permanent Ineff=
       F       F
Bank Sta=362.3,392.4
XS Rating Curve= 0 ,0
Exp/Cntr=0.3,0.1

Type RM Length L Ch R = 1 ,5626    ,88.3,87.8,87.3
XS GIS Cut Line= 4
     2175429.837      292623.236     2175556.233      292882.972
     2175731.243      293249.659     2175778.468      293420.502
#Sta/Elev= 30
       0 1989.08    33.8 1967.48    84.9 1938.06    92.2 1934.73   114.1 1933.71
   176.1 1926.82   216.3 1924.37   230.9 1920.98   239.8 1917.68   245.5 1914.44
   252.8 1908.58   256.4 1908.09   279.3    1910   288.9 1909.88     299 1907.04
   316.2  1904.8   335.9 1901.01   342.3 1901.01   343.8 1901.81   365.6 1905.03
   429.4 1906.69   489.2 1906.76   563.2 1907.48   596.8 1908.55   631.7 1911.73
   660.7 1912.81   682.9 1913.59   823.2 1914.54   851.2 1917.01   872.4 1921.95
#Mann= 9 ,-1 , 0
       0     .12       0   245.5    .016       0   288.9     .12       0
   316.2     .04       0   365.6     .12       0   429.4    .016       0
   489.2     .12       0   660.7    .016       0   682.9     .12       0
#XS Ineff= 2 , 0
       0  283.25    1913  420.05       0 1913.58
Permanent Ineff=
       F       F
Bank Sta=316.2,365.6
XS Rating Curve= 0 ,0
Exp/Cntr=0.5,0.3

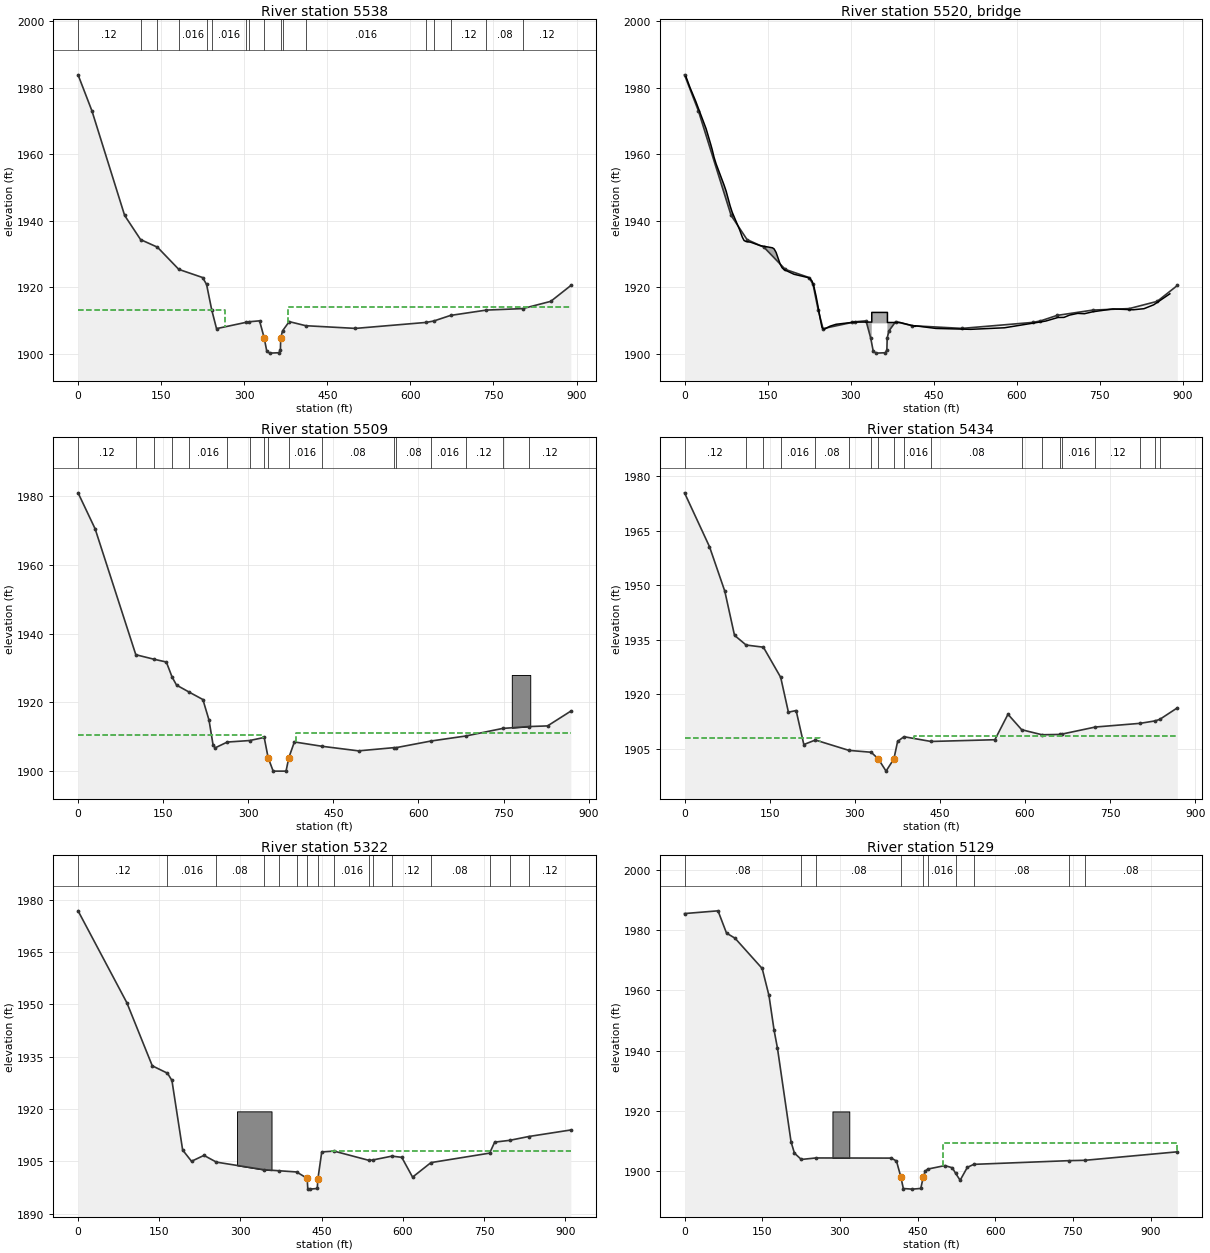
Type RM Length L Ch R = 1 ,5538    ,29.6,29.7,29.8
BEGIN DESCRIPTION:
Merged DS Survey WAC062BU
END DESCRIPTION:
XS GIS Cut Line= 4
     2175349.017      292642.828     2175480.835      292930.873
     2175524.774      293016.799     2175742.517      293440.567
#Sta/Elev= 30
       0 1983.88      25 1973.06    84.1 1941.57   112.9  1934.3   143.3 1932.02
   181.9 1925.34   224.8 1922.89     232 1920.82   241.3 1913.16     250 1907.51
   303.2  1909.4   307.8 1909.56   327.7 1909.86   336.1 1904.69   340.8 1900.64
   346.2 1900.14   362.5 1900.26   365.3 1901.05   365.9 1904.73   369.2 1906.85
   381.2 1909.62   411.1 1908.39   500.8 1907.58   628.4 1909.38   642.1  1909.8
   672.6 1911.49   737.1 1913.09   802.9 1913.54   853.4 1915.72   889.7 1920.49
#Mann= 17 ,-1 , 0
       0     .12       0   112.9     .08       0   143.3     .12       0
   181.9    .016       0     232     .12       0   241.3    .016       0
   303.2     .08       0   307.8    .016       0   336.1    .045       0
   365.9    .016       0   369.2     .12       0   411.1    .016       0
   628.4     .08       0   642.1    .016       0   672.6     .12       0
   737.1     .08       0   802.9     .12       0
#XS Ineff= 2 , 0
       0     265 1913.19  379.17       0 1914.07
Permanent Ineff=
       F       F
Bank Sta=336.1,365.9
XS Rating Curve= 0 ,0
Exp/Cntr=0.5,0.3

Type RM Length L Ch R = 3 ,5520    ,,,
BEGIN DESCRIPTION:
Merged US Survey WAC060RP
Old Anthony Creek Road
END DESCRIPTION:
Bridge Culvert--1,0,-1,-1, 0
Deck Dist Width WeirC Skew NumUp NumDn MinLoCord MaxHiCord MaxSubmerge Is_Ogee
5,18,2.6,0, 60, 60, , , 0.98, 0, 0,0,,
     2.6    10.1    20.2      39    47.4    49.9    53.4      57    71.5    75.1
    82.3    85.9    99.4   104.3   106.8   107.6   111.2   119.2   136.4   158.8
   161.7   165.3   172.5   176.1   179.7   197.8   223.1   226.7   230.3   233.9
   237.5   241.1   244.7   248.3   251.9   262.7   273.6  307.24  338.06  338.06
  366.32  366.32   389.1  416.75  416.85   453.8   516.8   577.8   652.2   674.2
     685   695.1   709.8   721.9   736.7   773.3   810.1   829.5   846.9   876.2
 1983.35 1979.97 1975.94 1967.65 1962.92 1961.43 1959.03  1957.1 1950.67  1948.9
 1944.47 1942.61 1937.29 1935.06 1934.24 1934.01 1933.71 1933.52  1932.5 1931.83
  1931.5 1930.45 1926.99 1925.84 1925.27 1923.86 1922.87 1922.53 1921.82 1919.97
  1917.3 1914.16 1910.69 1907.77 1907.27 1908.25 1908.82 1909.48 1909.48 1912.39
 1912.39 1909.36 1909.36 1908.18 1908.36 1907.57  1907.3 1907.77 1909.79 1910.87
 1910.89 1911.58  1912.1    1912 1912.57 1913.44 1913.19 1913.51 1914.67 1917.99
                                                                                
                                                                                
                                                                                
                                                                          1909.1
  1909.1
                                                                                
       0     4.6    12.1    22.2      41    49.4    55.4      59    73.5    77.1
    84.3    87.9   101.4   106.3   108.8   109.6   113.2   121.2   138.4   160.8
   163.7   167.3   174.5   178.1   181.7   199.8   225.1   228.7   232.3   235.9
   239.5   243.1   246.7   250.3   253.9   264.7   275.6  309.24  340.06  340.06
  368.32  368.32   391.1  418.75  418.85   455.8   518.8   579.8   654.2   676.2
     687   697.1   711.8   723.9   738.7   775.3   812.1   831.5   848.9   878.2
 1980.92 1983.35 1979.97 1975.94 1967.65 1962.92 1959.03  1957.1 1950.67  1948.9
 1944.47 1942.61 1937.29 1935.06 1934.24 1934.01 1933.71 1933.52  1932.5 1931.83
  1931.5 1930.45 1926.99 1925.84 1925.27 1923.86 1922.87 1922.53 1921.82 1919.97
  1917.3 1914.16 1910.69 1907.77 1907.27 1908.25 1908.82 1909.48 1909.48 1912.39
 1912.39 1909.36 1909.36 1908.18 1908.36 1907.57  1907.3 1907.77 1909.79 1910.87
 1910.89 1911.58  1912.1    1912 1912.57 1913.44 1913.19 1913.51 1914.67 1917.99
                                                                                
                                                                                
                                                                                
                                                                          1909.1
  1909.1
                                                                                
BR Coef=-1 , 1 , 0 ,, 0 ,,,0.8,0,1.2,0,
WSPro=,,,, 1 ,,,, 0 ,,,, 0 ,,,,-1 ,-1 ,-1 , 0 , 0 , 0 , 0 , 0
BC Design=,, 0 ,, 0 ,,0,,,,
BC HTab HWMax=0
BC HTab TWMax=0
BC HTab MaxFlow=0
BC Use User HTab Curves=0
BC User HTab FreeFlow(D)= 0

Type RM Length L Ch R = 1 ,5509    ,75.6,74.6,73.6
BEGIN DESCRIPTION:
Merged US Survey WAC058BD
END DESCRIPTION:
XS GIS Cut Line= 4
     2175325.562      292652.305     2175448.591      292932.539
     2175488.625      293011.629      2175708.32      293431.492
#Sta/Elev= 30
       0 1980.92    30.1 1970.45   101.8 1933.87   133.8 1932.56   155.6 1931.75
   165.8 1927.36   173.6 1925.04     196 1922.99     220 1920.85   230.8 1914.88
     238 1907.63   241.5 1906.79     263 1908.49   302.5 1908.93   328.1 1909.83
     335 1903.96   343.9 1900.04   366.6 1900.04   371.5 1903.96   381.3 1908.52
     430 1907.26   494.3 1905.93   557.2 1906.87   559.9 1906.84   622.1 1908.79
   683.1 1910.24   748.4 1912.45   794.2 1912.99   827.5 1913.18   868.6 1917.49
#Mann= 17 ,-1 , 0
       0     .12       0   101.8     .08       0   133.8     .12       0
   165.8     .08       0     196    .016       0     263     .08       0
   302.5    .016       0   328.1     .12       0     335    .045       0
   371.5    .016       0     430     .08       0   557.2    .016       0
   559.9     .08       0   622.1    .016       0   683.1     .12       0
   748.4     .08       0   794.2     .12       0
#XS Ineff= 2 , 0
       0  326.54 1910.68     384       0    1911
Permanent Ineff=
       F       F
#Block Obstruct= 1 ,-1
   764.5     7971927.991
Bank Sta=335,371.5
XS Rating Curve= 0 ,0
Exp/Cntr=0.5,0.3

Type RM Length L Ch R = 1 ,5434    ,103.8,112.3,108
XS GIS Cut Line= 4
      2175308.67      292670.145     2175392.738      292989.537
     2175426.526      293048.755     2175672.922      293449.445
#Sta/Elev= 30
       0 1975.43      44  1960.6      71 1948.33    88.1 1936.18   108.6  1933.5
     139 1932.91   169.5 1924.61   183.1    1915   196.7 1915.46   210.3 1906.09
   230.6 1907.34   289.6 1904.49     329 1903.97   341.6 1902.13   355.2 1898.77
     369 1902.13   375.6 1906.95   386.7 1908.25   434.5 1906.94     547 1907.42
   570.1 1914.43   594.3 1910.17   630.1 1908.79   662.6 1908.88   664.9 1908.96
   724.2 1910.92   802.7 1911.93   828.8 1912.59   837.6 1913.02   868.6  1916.2
#Mann= 19 ,-1 , 0
       0     .12       0   108.6     .08       0     139     .12       0
   169.5    .016       0   230.6     .08       0   289.6    .016       0
     329     .12       0   341.6     .04       0     369     .12       0
   386.7    .016       0   434.5     .08       0   594.3    .016       0
   630.1     .06       0   662.6     .08       0   664.9    .016       0
   724.2     .12       0   802.7    .016       0   828.8     .12       0
   837.6    .016       0
#XS Ineff= 2 , 0
       0   239.2 1907.89   405.2       0 1908.52
Permanent Ineff=
       F       F
Bank Sta=341.6,369
XS Rating Curve= 0 ,0
Exp/Cntr=0.3,0.1

Type RM Length L Ch R = 1 ,5322    ,161.1,193.3,205.5
XS GIS Cut Line= 4
     2175300.309      292667.441      2175320.57      293075.008
     2175355.487      293125.846     2175607.374      293487.467
#Sta/Elev= 30
       0 1976.83    90.2 1950.47   137.1 1932.41   165.2 1930.28   173.4 1928.22
   193.2 1908.28   209.6 1905.04   232.6 1906.73   255.6  1904.8   343.7 1902.61
   371.8 1902.32   403.7 1901.98   423.2 1900.16   424.4  1897.2   427.9 1897.06
   441.9 1897.24   443.1 1900.03   450.2 1907.72   472.8 1907.96     538 1905.28
   545.5 1905.45   579.9 1906.52     598 1906.17     618  1900.5   651.9 1904.66
   760.3 1907.38   769.7 1910.53   797.6 1911.05   832.5 1912.14   910.4 1914.02
#Mann= 16 ,-1 , 0
       0     .12       0   165.2    .016       0   255.6     .08       0
   343.7    .016       0   371.8     .08       0   403.7     .12       0
   423.2     .04       0   443.1     .12       0   472.8    .016       0
     538     .08       0   545.5    .016       0   579.9     .12       0
   651.9     .08       0   760.3    .016       0   797.6     .06       0
   832.5     .12       0
#XS Ineff= 2 , 0
       0                   467.9       0 1907.99
Permanent Ineff=
       F       F
#Block Obstruct= 1 ,-1
   293.6   357.41919.352
Bank Sta=423.2,443.1
XS Rating Curve= 0 ,0
Exp/Cntr=0.3,0.1

Type RM Length L Ch R = 1 ,5129    ,201,202.7,204.5
XS GIS Cut Line= 5
     2175163.157      292638.178     2175165.505      293033.275
     2175146.217      293122.479     2175140.818      293133.825
     2174996.777      293563.186
#Sta/Elev= 30
       0 1985.55    64.7 1986.46    81.1 1979.05    97.5 1977.36     150 1967.28
   163.1  1958.3     173 1946.72   179.5 1940.78   205.8 1909.57   212.3 1905.86
   225.5 1903.76   253.8 1904.26   399.4 1904.21   409.4 1903.23   417.7    1898
   422.6 1894.09   439.8 1893.89   456.3 1894.11   461.1 1897.92   464.6 1899.83
   469.9 1900.56   502.8 1901.72   517.2 1900.99   523.4 1899.21   532.3 1896.84
   546.2 1901.13   558.6 1902.13   742.6 1903.36   773.6 1903.48   951.8  1906.3
#Mann= 10 ,-1 , 0
       0     .08       0   225.5    .016       0   253.8     .08       0
   417.7    .045       0   461.1     .12       0   469.9    .016       0
   523.4     .06       0   558.6     .08       0   742.6    .016       0
   773.6     .08       0
#XS Ineff= 2 , 0
                          498.87         1909.21
Permanent Ineff=
       F       F
#Block Obstruct= 1 ,-1
   285.7   318.2 1919.73
Bank Sta=417.7,461.1
XS Rating Curve= 0 ,0
Exp/Cntr=0.3,0.1

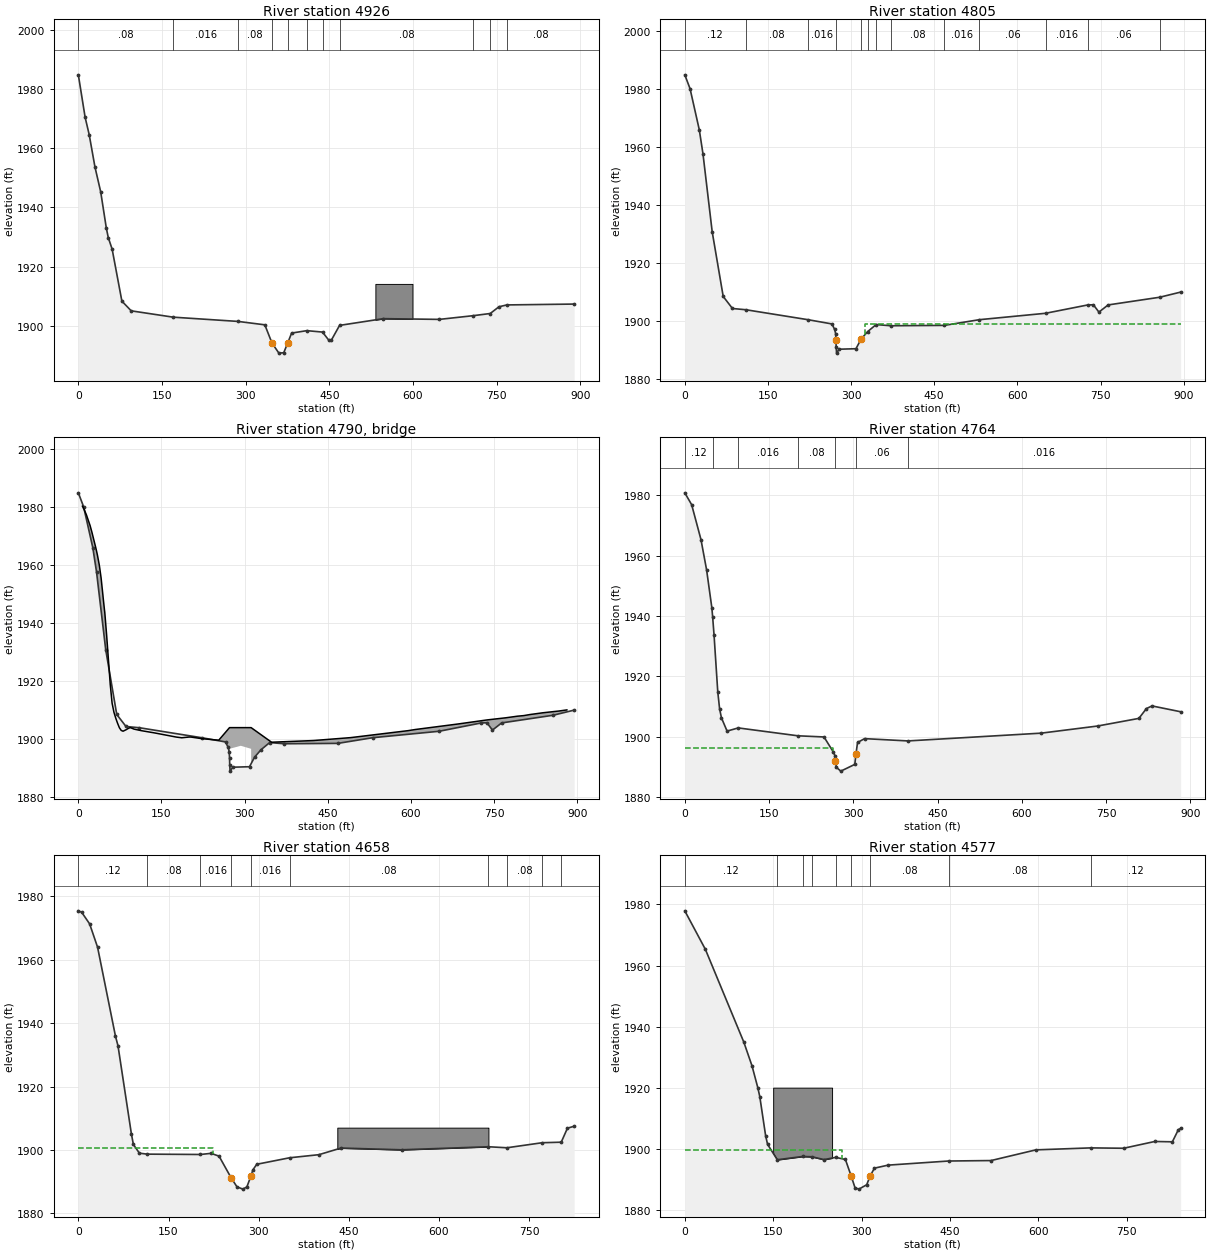
Type RM Length L Ch R = 1 ,4926    ,122.1,113.9,116.2
XS GIS Cut Line= 3
     2175063.838      292677.601     2174943.292      293082.637
     2174855.293      293540.713
#Sta/Elev= 30
       0 1984.86    12.2 1970.48    19.5 1964.61    29.8  1953.7    40.1 1945.29
    50.3 1932.91    53.8 1929.74    60.6 1925.93    78.1 1908.33    94.8 1905.05
   170.1 1902.91   286.5 1901.47   334.4 1900.32   347.2 1894.16   359.6 1890.75
   368.3 1890.89   375.5 1894.22   382.4 1897.53   409.7 1898.35   437.8 1897.87
     449 1895.14   453.5 1895.09   468.4 1900.13     547 1902.41   647.3 1902.16
   708.3 1903.42   738.5 1904.15   754.2 1906.43   768.4 1907.05     889 1907.34
#Mann= 11 ,-1 , 0
       0     .08       0   170.1    .016       0   286.5     .08       0
   347.2     .04       0   375.5     .08       0   409.7    .016       0
   437.8     .06       0   468.4     .08       0   708.3    .016       0
   738.5     .06       0   768.4     .08       0
#XS Ineff= 2 , 0
                             438         1897.62
Permanent Ineff=
       F       F
#Block Obstruct= 1 ,-1
   532.6   599.1 1914.16
Bank Sta=347.2,375.5
XS Rating Curve= 0 ,0
Exp/Cntr=0.5,0.3

Type RM Length L Ch R = 1 ,4805    ,52,53.7,53.1
BEGIN DESCRIPTION:
Merged DS Survey WAC052BU
END DESCRIPTION:
XS GIS Cut Line= 5
     2174922.383      292657.432       2174883.3       292894.72
     2174881.759      292904.361     2174865.915      293004.351
     2174781.522      293540.782
#Sta/Elev= 30
       0 1984.73     9.5 1979.94    26.1 1965.83    32.8 1957.49    49.4 1930.67
    69.3 1908.34      86  1904.2   110.3 1903.77   222.3 1900.34   265.5 1898.88
   270.3 1896.99   272.1 1895.57   272.8 1893.33   273.1    1891   273.8 1888.82
   278.6 1890.17   308.8 1890.34   318.1 1893.67   329.9 1896.24   345.2 1898.66
   371.8 1898.25   468.1 1898.38   531.2 1900.34   650.8 1902.55   727.1 1905.43
   737.1 1905.48   747.1 1902.96   763.7 1905.43   856.7 1908.08   894.5 1909.85
#Mann= 13 ,-1 , 0
       0     .12       0   110.3     .08       0   222.3    .016       0
   272.8    .045       0   318.1     .06       0   329.9    .016       0
   345.2    .016       0   371.8     .08       0   468.1    .016       0
   531.2     .06       0   650.8    .016       0   727.1     .06       0
   856.7    .016       0
#XS Ineff= 2 , 0
          260.14 1898.77  324.73         1898.86
Permanent Ineff=
       F       F
Bank Sta=272.8,318.1
XS Rating Curve= 0 ,0
Exp/Cntr=0.5,0.3

Type RM Length L Ch R = 3 ,4790    ,,,
BEGIN DESCRIPTION:
Merged DS Survey WAC050RP
Pocohantas Trail/ Highway 92
END DESCRIPTION:
Bridge Culvert--1,0,-1,-1, 0
Deck Dist Width WeirC Skew NumUp NumDn MinLoCord MaxHiCord MaxSubmerge Is_Ogee
4,30,2.6,0, 54, 54, , , 0.98, 0, 0,0,,
     7.4       8    11.3    14.6    21.2    24.5    31.1    32.4    34.4    37.7
    38.3    41.1    44.4    44.6    47.1    47.7      51    57.6    60.9    64.2
    67.5    70.8    74.1    77.4    80.7    86.2    90.7      94   100.6   113.8
   136.9   176.6   186.5   199.8   203.1   222.9  253.27  272.73   293.1  311.73
  348.62   424.1   491.4   594.5   607.8   684.3   737.5   770.7   792.5   803.7
     814   838.2   867.2   881.4
 1980.13 1979.95 1978.62 1977.13 1973.46 1971.16 1966.11 1965.05 1963.33 1959.97
 1959.24 1955.36 1949.36 1948.93 1944.47 1943.55 1935.84 1918.62 1912.26 1909.14
 1907.08 1905.31 1903.76 1902.84 1902.58 1903.09 1903.61 1903.81 1903.29 1902.76
 1902.01 1900.56 1900.31 1900.57 1900.56 1900.01 1899.47 1903.81 1903.81 1903.81
 1898.78 1899.36 1900.37 1902.76 1903.16 1905.05 1906.47 1907.19 1907.76 1907.96
  1908.3 1908.93 1909.54 1909.92
                                                                                
                                                                                
                                                                                
                                                         1896.51 1897.56 1896.51
                                                                                
                                
      .9     1.5     4.8     8.1    14.7      18    24.6    25.9    27.9    31.2
    31.8    34.6    37.9    38.1    40.6    41.2    44.5    51.1    54.4    57.7
      61    64.3    67.6    70.9    74.2    79.7    84.2    87.5    94.1   107.3
   130.4   170.1     180   193.3   196.6   216.4  246.77  266.23   286.6  305.23
  342.12   417.6   484.9     588   601.3   677.8     731   764.2     786   797.2
   807.5   831.7   860.7   874.9
 1980.13 1979.95 1978.62 1977.13 1973.46 1971.16 1966.11 1965.05 1963.33 1959.97
 1959.24 1955.36 1949.36 1948.93 1944.47 1943.55 1935.84 1918.62 1912.26 1909.14
 1907.08 1905.31 1903.76 1902.84 1902.58 1903.09 1903.61 1903.81 1903.29 1902.76
 1902.01 1900.56 1900.31 1900.57 1900.56 1900.01 1899.47 1903.81 1903.81 1903.81
 1898.78 1899.36 1900.37 1902.76 1903.16 1905.05 1906.47 1907.19 1907.76 1907.96
  1908.3 1908.93 1909.54 1909.92
                                                                                
                                                                                
                                                                                
                                                         1896.51 1897.56 1896.51
                                                                                
                                
BR Coef=-1 , 1 , 0 ,, 0 ,,,0.8,0,1.2,0,
WSPro=,,,, 1 ,,,, 0 ,,,, 0 ,,,,-1 ,-1 ,-1 , 0 , 0 , 0 , 0 , 0
BC Design=,, 0 ,, 0 ,,0,,,,
BC HTab HWMax=0
BC HTab TWMax=0
BC HTab MaxFlow=0
BC Use User HTab Curves=0
BC User HTab FreeFlow(D)= 0

Type RM Length L Ch R = 1 ,4764    ,100.9,100.5,99.6
BEGIN DESCRIPTION:
Merged DS Survey WAC048BD
END DESCRIPTION:
XS GIS Cut Line= 3
     2174867.393      292654.698     2174811.107      293021.619
     2174713.094      293523.837
#Sta/Elev= 30
       0 1980.87    12.2 1976.94    28.8 1965.38    38.8 1955.35    48.1 1942.85
    49.6 1939.73    52.1 1933.71    58.7 1914.93      62 1909.22    65.3 1906.26
    75.3  1901.9    95.2 1902.95   201.4 1900.34   247.9 1899.95   264.5 1894.97
   267.8 1893.55   268.2 1892.15   269.9 1889.88   277.8 1888.63   302.7 1890.86
   304.8  1894.3   307.6 1898.12   320.1  1899.4   397.4 1898.64   634.8 1901.22
   735.1 1903.58   808.6 1906.11     822 1909.37     832 1910.24   882.9 1908.31
#Mann= 7 ,-1 , 0
       0     .12       0    49.6     .08       0    95.2    .016       0
   201.4     .08       0   268.2    .045       0   304.8     .06       0
   397.4    .016       0
#XS Ineff= 2 , 0
          263.62  1896.4  306.83          1896.4
Permanent Ineff=
       F       F
Bank Sta=268.2,304.8
XS Rating Curve= 0 ,0
Exp/Cntr=0.5,0.3

Type RM Length L Ch R = 1 ,4658    ,81,80.7,77.5
BEGIN DESCRIPTION:
Not Burnt
END DESCRIPTION:
XS GIS Cut Line= 3
     2174767.294      292631.794     2174723.897      292944.009
     2174633.488      293445.482
#Sta/Elev= 30
       0 1975.47     5.5 1975.03    18.8 1971.35      32 1963.99    61.8  1935.9
      66 1932.87    88.3 1905.04    91.6 1901.75   101.6    1899   114.8  1898.7
     203 1898.59   220.8 1898.95   234.1 1898.06   253.9 1891.32   263.9 1888.38
   273.8 1887.66   280.4 1888.37   287.1 1891.78   290.4 1893.74   296.8  1895.5
   351.4 1897.55   400.2 1898.53   436.9 1900.62   537.8 1900.07   682.1 1901.03
   712.9 1900.71   771.6  1902.3   803.3 1902.47   813.6 1906.88   824.8 1907.51
#Mann= 10 ,-1 , 0
       0     .12       0   114.8     .08       0     203    .016       0
   253.9     .04       0   287.1    .016       0   351.4     .08       0
   682.1     .12       0   712.9     .08       0   771.6     .12       0
   803.3     .08       0
#XS Ineff= 2 , 0
          224.53 1900.75
Permanent Ineff=
       F       F
#Block Obstruct= 1 ,-1
   430.8   682.21907.062
Bank Sta=253.9,287.1
XS Rating Curve= 0 ,0
Exp/Cntr=0.3,0.1

Type RM Length L Ch R = 1 ,4577    ,50.4,51.2,54.1
XS GIS Cut Line= 4
     2174684.186      292586.189     2174654.931      292846.142
     2174639.886      293035.882     2174588.062       293422.05
#Sta/Elev= 30
       0 1977.92    34.9 1965.31   100.2  1934.9   114.1 1927.12     124 1919.93
   127.3 1917.03   137.2 1904.24   140.5 1901.42     157 1896.37     200 1897.45
   215.9 1897.35   236.3 1896.42   256.1 1897.15   272.6 1896.47   282.4 1891.05
     289 1887.16   295.6 1886.75   308.8 1888.19   314.5 1891.03   321.9 1893.62
     345 1894.61   447.7 1895.96   519.8 1896.11   595.9 1899.61   688.9 1900.26
   744.9 1900.14   797.8 1902.36   827.6 1902.25   837.7  1906.2   841.6 1906.65
#Mann= 9 ,-1 , 0
       0     .12       0     157     .08       0     200     .12       0
   215.9    .016       0   256.1     .08       0   282.4     .04       0
   314.5     .08       0   447.7     .08       0   688.9     .12       0
#XS Ineff= 2 , 0
          266.84 1899.61
Permanent Ineff=
       F       F
#Block Obstruct= 1 ,-1
     150     250    1920
Bank Sta=282.4,314.5
XS Rating Curve= 0 ,0
Exp/Cntr=0.3,0.1

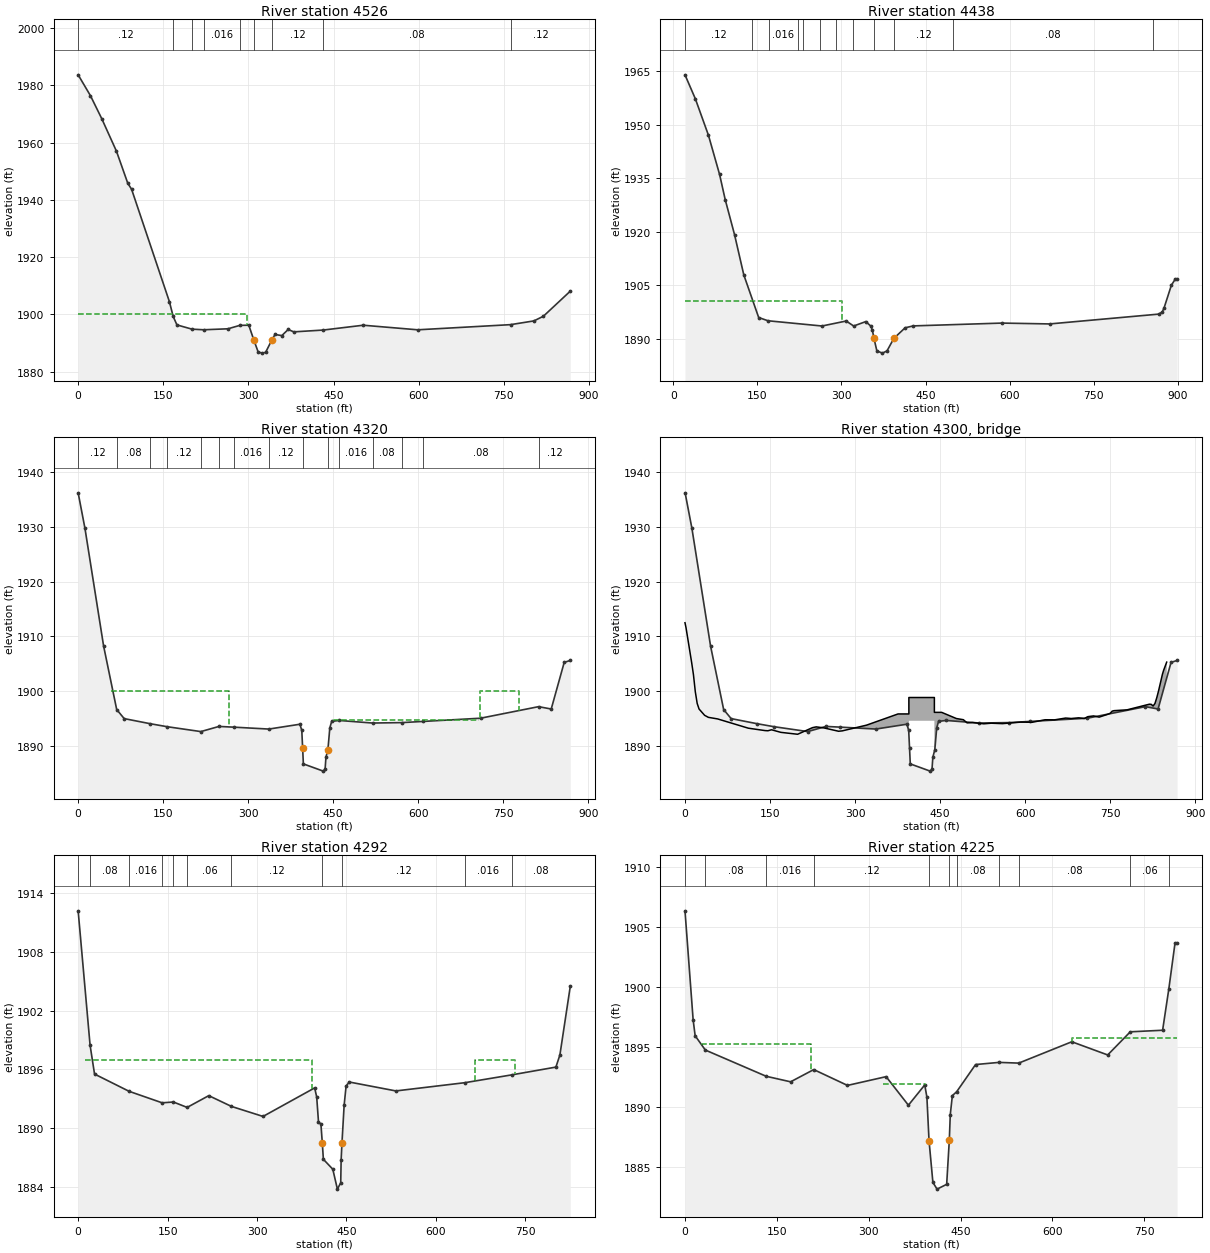
Type RM Length L Ch R = 1 ,4526    ,92.4,88,72.8
BEGIN DESCRIPTION:
Not Burnt
END DESCRIPTION:
XS GIS Cut Line= 4
     2174655.186      292551.028     2174606.968      292833.106
     2174588.886      292963.296      2174534.64      293409.318
#Sta/Elev= 30
       0 1983.68    21.7 1976.38    41.6 1968.35    67.5 1956.99    87.5 1945.75
    94.1 1943.72   160.7 1904.45   167.4 1899.26     174  1896.3   200.5 1894.82
     221  1894.6   263.9 1894.94   284.8 1896.14   300.6 1896.19   309.3 1891.13
     317 1886.89   323.6 1886.44   330.2  1886.7   341.3 1891.06   346.8 1892.95
   358.8 1892.57     370  1894.7   379.9 1893.87   431.6  1894.5   502.2 1896.19
   598.1 1894.59   761.7 1896.39   802.9  1897.7   819.6 1899.34   866.9 1908.09
#Mann= 9 ,-1 , 0
       0     .12       0   167.4     .08       0   200.5     .12       0
     221    .016       0   284.8     .12       0   309.3     .04       0
   341.3     .12       0   431.6     .08       0   761.7     .12       0
#XS Ineff= 2 , 0
           296.7    1900
Permanent Ineff=
       F       F
Bank Sta=309.3,341.3
XS Rating Curve= 0 ,0
Exp/Cntr=0.3,0.1

Type RM Length L Ch R = 1 ,4438    ,104.4,111.9,99.1
BEGIN DESCRIPTION:
Not Burnt
END DESCRIPTION:
XS GIS Cut Line= 4
     2174560.608      292535.253     2174511.999      292848.197
     2174527.407      292963.296     2174493.654      293406.902
#Sta/Elev= 30
    20.9 1964.04    39.4  1957.3    62.7  1947.1    82.6 1936.08    92.6 1929.04
   109.2 1919.24   125.8  1907.9   152.3 1895.95   168.9 1895.04   265.2 1893.57
   308.4 1894.97   321.7 1893.57   343.4 1894.81   352.2 1893.55   355.1 1892.41
     358 1890.07   363.1 1886.59     373 1885.96   381.2 1886.59   393.4  1890.1
   413.5 1893.07   428.1  1893.6   586.3 1894.39   671.3 1894.15   865.4  1896.9
     872 1897.48   875.3 1898.63   888.4 1905.03     895 1906.65   898.6 1906.65
#Mann= 12 ,-1 , 0
    20.9     .12       0   141.1     .08       0     171    .016       0
   222.1     .08       0   231.5     .12       0   261.9    .016       0
   290.4     .08       0   320.6     .12       0     358     .04       0
   393.4     .12       0   499.6     .08       0   855.6     .12       0
#XS Ineff= 2 , 0
          301.64  1900.6
Permanent Ineff=
       F       F
Bank Sta=358,393.4
XS Rating Curve= 0 ,0
Exp/Cntr=0.5,0.3

Type RM Length L Ch R = 1 ,4320    ,49.6,47.4,47
BEGIN DESCRIPTION:
Merged DS Survey WAC042BU
END DESCRIPTION:
XS GIS Cut Line= 4
        2174468.      292528.588      2174429.66      292912.848
     2174435.491      292989.818       2174438.9      293394.286
#Sta/Elev= 30
      .3  1936.2    12.3 1929.72    45.2 1908.23    68.3 1896.63    81.5 1894.98
   127.7 1894.04   157.3  1893.5   216.7 1892.61   248.7 1893.55   274.4 1893.42
   336.6 1893.07   391.4 1893.95   394.7 1892.83   396.2 1889.59   397.5 1886.71
   432.6 1885.39   435.8 1885.71   437.3 1887.91   440.8 1889.32   444.1 1893.26
   447.4 1894.47   460.5 1894.64   519.5 1894.17   571.5 1894.25   608.2 1894.46
   709.9 1895.05   812.3 1897.16   834.6 1896.73   857.5 1905.24   868.2  1905.6
#Mann= 15 ,-1 , 0
      .3     .12       0    68.3     .08       0   127.7    .016       0
   157.3     .12       0   216.7    .016       0   248.7     .08       0
   274.4    .016       0   336.6     .12       0   396.2     .04       0
   440.8     .12       0   460.5    .016       0   519.5     .08       0
   571.5     .12       0   608.2     .08       0   812.3     .12       0
#XS Ineff= 4 ,-1
   57.55  265.57    1900  270.38  388.13 1893.19  451.67  706.61 1894.77
  709.84   777.2    1900
Permanent Ineff=
       F       F       F       F
Bank Sta=396.2,440.8
XS Rating Curve= 0 ,0
Exp/Cntr=0.5,0.3

Type RM Length L Ch R = 3 ,4300    ,,,
BEGIN DESCRIPTION:
Merged US Survey WAC040RP
White Gate Drive
END DESCRIPTION:
Bridge Culvert--1,0,-1,-1, 0
Deck Dist Width WeirC Skew NumUp NumDn MinLoCord MaxHiCord MaxSubmerge Is_Ogee
4,20,2.6,0, 60, 60, , , 0.98, 0, 0,0,,
      .1     1.9    11.8      15    18.3    21.6    24.9    34.7    41.3    57.7
   111.8   141.4   146.3   152.8   169.2   198.8     225   231.6   244.7     271
   277.5   320.2  375.87     395     395     440     440  452.85  478.87   491.1
   497.7   507.5   527.2   540.3     560   592.5   612.5   635.5   651.9   671.6
   681.4   694.6   704.4     711   720.8   730.7     747   750.4   753.6   756.9
   779.9   819.3   822.6   825.8   829.1   832.4   835.7   842.3   844.5   849.8
 1912.48 1911.58 1905.24 1903.01 1899.88 1897.75 1896.73 1895.58 1895.21 1894.92
 1893.23 1892.79 1892.76 1892.94 1892.47 1892.12 1893.33 1893.47 1893.29 1892.67
 1892.74 1893.78 1895.83 1895.83 1898.83 1898.83 1896.12 1896.12 1894.99 1894.78
  1894.2 1894.26 1894.03 1894.14 1894.06 1894.34 1894.31 1894.77 1894.75 1895.08
    1895 1895.12    1895 1895.34 1895.47 1895.25 1895.81 1895.97 1896.34 1896.43
 1896.58 1897.61 1897.58 1897.28 1897.74 1898.83 1900.15 1903.09 1903.83 1905.29
                                                                                
                                                                                
                                 1894.58 1894.58
                                                                                
                                                                                
                                                                                
       0     6.1     6.7     7.9    17.8      21    24.3    27.6    30.9    40.7
    47.3    63.7   117.8   147.4   158.8   175.2   204.8     231   237.6     277
   283.5   326.2  381.87     402     402     447     447  458.85  484.87   497.1
   503.7   513.5   533.2   546.3     566   598.5   618.5   641.5   657.9   677.6
   687.4   700.6   710.4     717   726.8   736.7     753   756.4   759.6   762.9
   785.9   825.3   828.6   831.8   835.1   838.4   841.7   848.3   850.5   855.8
    1912 1912.48 1912.21 1911.58 1905.24 1903.01 1899.88 1897.75 1896.73 1895.58
 1895.21 1894.92 1893.23 1892.79 1892.94 1892.47 1892.12 1893.33 1893.47 1892.67
 1892.74 1893.78 1895.83 1895.83 1898.83 1898.83 1896.12 1896.12 1894.99 1894.78
  1894.2 1894.26 1894.03 1894.14 1894.06 1894.34 1894.31 1894.77 1894.75 1895.08
    1895 1895.12    1895 1895.34 1895.47 1895.25 1895.81 1895.97 1896.34 1896.43
 1896.58 1897.61 1897.58 1897.28 1897.74 1898.83 1900.15 1903.09 1903.83 1905.29
                                                                                
                                                                                
                                 1894.58 1894.58
                                                                                
                                                                                
                                                                                
BR Coef=-1 , 1 , 0 ,, 0 ,,,0.8,0,1.2,0,
WSPro=,,,, 1 ,,,, 0 ,,,, 0 ,,,,-1 ,-1 ,-1 , 0 , 0 , 0 , 0 , 0
BC Design=,, 0 ,, 0 ,,0,,,,
BC HTab HWMax=0
BC HTab TWMax=0
BC HTab MaxFlow=0
BC Use User HTab Curves=0
BC User HTab FreeFlow(D)= 0

Type RM Length L Ch R = 1 ,4292    ,43.7,53.5,59
BEGIN DESCRIPTION:
Merged DS Survey WAC038BD
END DESCRIPTION:
XS GIS Cut Line= 6
      2174403.29      292529.556     2174388.527       292644.34
     2174374.503      292775.144     2174382.225      292914.805
     2174389.371      292998.264     2174315.242      293344.867
#Sta/Elev= 30
       0 1912.17      20 1898.48    27.5 1895.53    85.5 1893.77   140.8  1892.6
   159.8 1892.68   182.8 1892.13   219.1 1893.33   257.2 1892.23   310.1 1891.21
   396.7 1894.12   400.1 1893.19   403.1 1890.66   407.2 1890.42  409.52 1888.49
   411.3 1886.84   427.1 1885.83   434.8  1883.8   440.4 1884.45   441.1  1886.8
  442.45 1888.46   446.1 1892.34   449.4  1894.3   454.6 1894.72   532.9 1893.81
   648.6 1894.65   727.5 1895.45   801.3 1896.24     808 1897.48   825.4 1904.47
#Mann= 11 ,-1 , 0
       0     .12       0      20     .08       0    85.5    .016       0
   140.8     .12       0   159.8    .016       0   182.8     .06       0
   257.2     .12       0  409.52     .04       0  442.45     .12       0
   648.6    .016       0   727.5     .08       0
#XS Ineff= 4 ,-1
   12.09     3931896.925     393  398.45    1890  457.69  658.89    1891
   665.8  733.161896.925
Permanent Ineff=
       F       F       F       F
Bank Sta=409.52,442.45
XS Rating Curve= 0 ,0
Exp/Cntr=0.5,0.3

Type RM Length L Ch R = 1 ,4225    ,60.7,61,61.3
XS GIS Cut Line= 5
     2174399.537      292535.223     2174385.552      292643.957
     2174344.234      292919.172     2174320.385      292988.614
     2174232.706      293319.691
#Sta/Elev= 30
       0 1906.34    13.3 1897.25    16.6 1895.92    33.2 1894.73   132.7 1892.54
   172.5 1892.08   210.3  1893.1   265.4 1891.78   328.5 1892.51   364.9 1890.13
   391.6 1891.82   395.1  1890.8   398.6 1887.16   404.9 1883.69   411.7 1883.13
   427.4 1883.53   431.7 1887.19   433.3 1889.35   436.7 1890.93   443.7 1891.25
   474.6 1893.52   512.9  1893.7   545.1 1893.64   631.8 1895.42   690.4 1894.32
   727.3 1896.25   780.1 1896.38   790.2 1899.81   800.4 1903.66   803.8 1903.67
#Mann= 11 ,-1 , 0
       0     .12       0    33.2     .08       0   132.7    .016       0
   210.3     .12       0   398.6     .04       0   431.7     .12       0
   443.7     .08       0   512.9    .016       0   545.1     .08       0
   727.3     .06       0   790.2     .12       0
#XS Ineff= 3 ,-1
   27.63  205.53 1895.25  323.31  391.38 1891.92  632.12   803.8 1895.74
Permanent Ineff=
       F       F       F
Bank Sta=398.6,431.7
XS Rating Curve= 0 ,0
Exp/Cntr=0.3,0.1

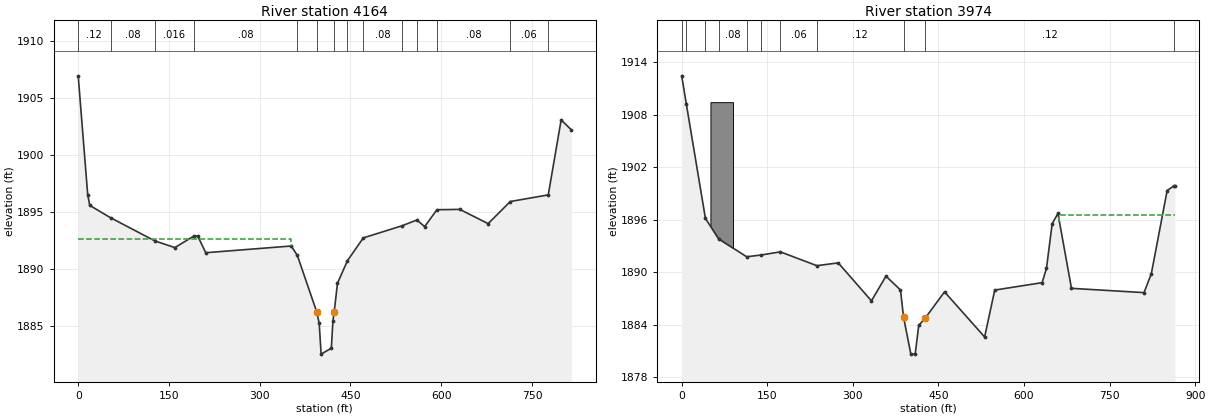
Type RM Length L Ch R = 1 ,4164    ,183.9,190.5,193.7
XS GIS Cut Line= 5
     2174398.276      292533.262     2174396.887      292544.063
     2174297.533      292870.512     2174262.382      292968.154
      2174161.81      293312.833
#Sta/Elev= 30
       0 1906.92    15.7 1896.51    19.1 1895.56    53.4 1894.48   126.6 1892.45
   159.7 1891.86   190.6 1892.85   197.5 1892.88   210.8 1891.41   352.1    1892
   362.2 1891.17   394.1 1886.24   398.3 1885.23   401.5 1882.52   418.4 1883.04
     421 1885.43   423.2 1886.25   428.5 1888.73     445 1890.71   471.2 1892.71
     535 1893.77   559.8 1894.28   572.6  1893.7   592.9 1895.18   630.7 1895.21
   677.5 1893.96   714.2  1895.9   776.9 1896.48   798.2 1903.05     815 1902.19
#Mann= 14 ,-1 , 0
       0     .12       0    53.4     .08       0   126.6    .016       0
   190.6     .08       0   362.2     .06       0   394.1     .04       0
   423.2     .06       0     445     .12       0   471.2     .08       0
     535    .016       0   559.8    .016       0   592.9     .08       0
   714.2     .06       0   776.9     .12       0
#XS Ineff= 2 , 0
          352.33  1892.6
Permanent Ineff=
       F       F
Bank Sta=394.1,423.2
XS Rating Curve= 0 ,0
Exp/Cntr=0.3,0.1

Type RM Length L Ch R = 1 ,3974    ,151.6,147.5,135.8
XS GIS Cut Line= 3
     2174289.531      292471.818     2174087.563      292893.382
     2173938.208      293261.082
#Sta/Elev= 30
       0 1912.43     8.2 1909.19    41.6 1896.14    64.7 1893.79   113.9 1891.75
   138.5 1891.94     173 1892.31   236.9 1890.73   274.4 1891.05   332.6 1886.71
   358.1 1889.53   383.5 1887.95   388.9 1884.84   401.7 1880.62   409.3 1880.62
   415.5  1883.9   427.2 1884.77   460.7 1887.74     531 1882.58   548.7 1887.94
   631.8 1888.79   639.4 1890.43   649.4 1895.53   659.5  1896.7   683.2 1888.14
   810.4 1887.65   823.2 1889.82   850.9 1899.32   863.5 1899.88   864.3 1899.84
#Mann= 11 ,-1 , 0
       0     .12       0     8.2     .08       0    41.6     .12       0
    64.7     .08       0   113.9     .12       0   138.5    .016       0
     173     .06       0   236.9     .12       0   388.9     .04       0
   427.2     .12       0   863.5     .06       0
#XS Ineff= 2 , 0
                           662.1         1896.53
Permanent Ineff=
       F       F
#Block Obstruct= 1 ,-1
    50.4    89.91909.419
Bank Sta=388.9,427.2
XS Rating Curve= 0 ,0
Exp/Cntr=0.3,0.1