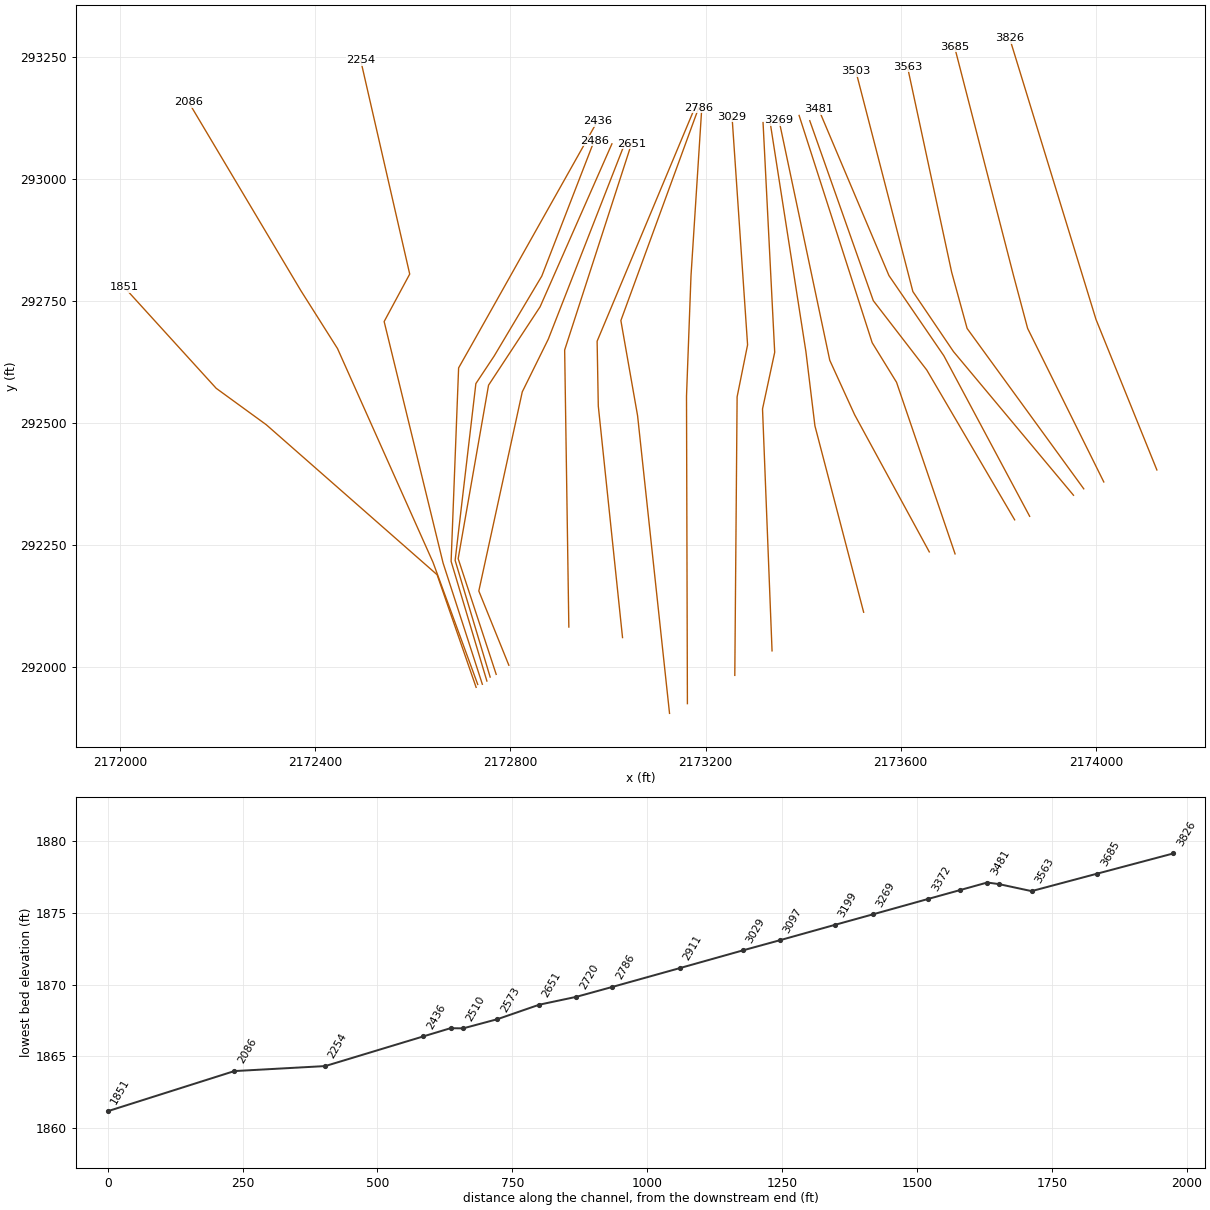
HEC-RAS study WADESCK1.prj: WADESCK1

--- WADESCK1.g01 (geometry) --- (continued)

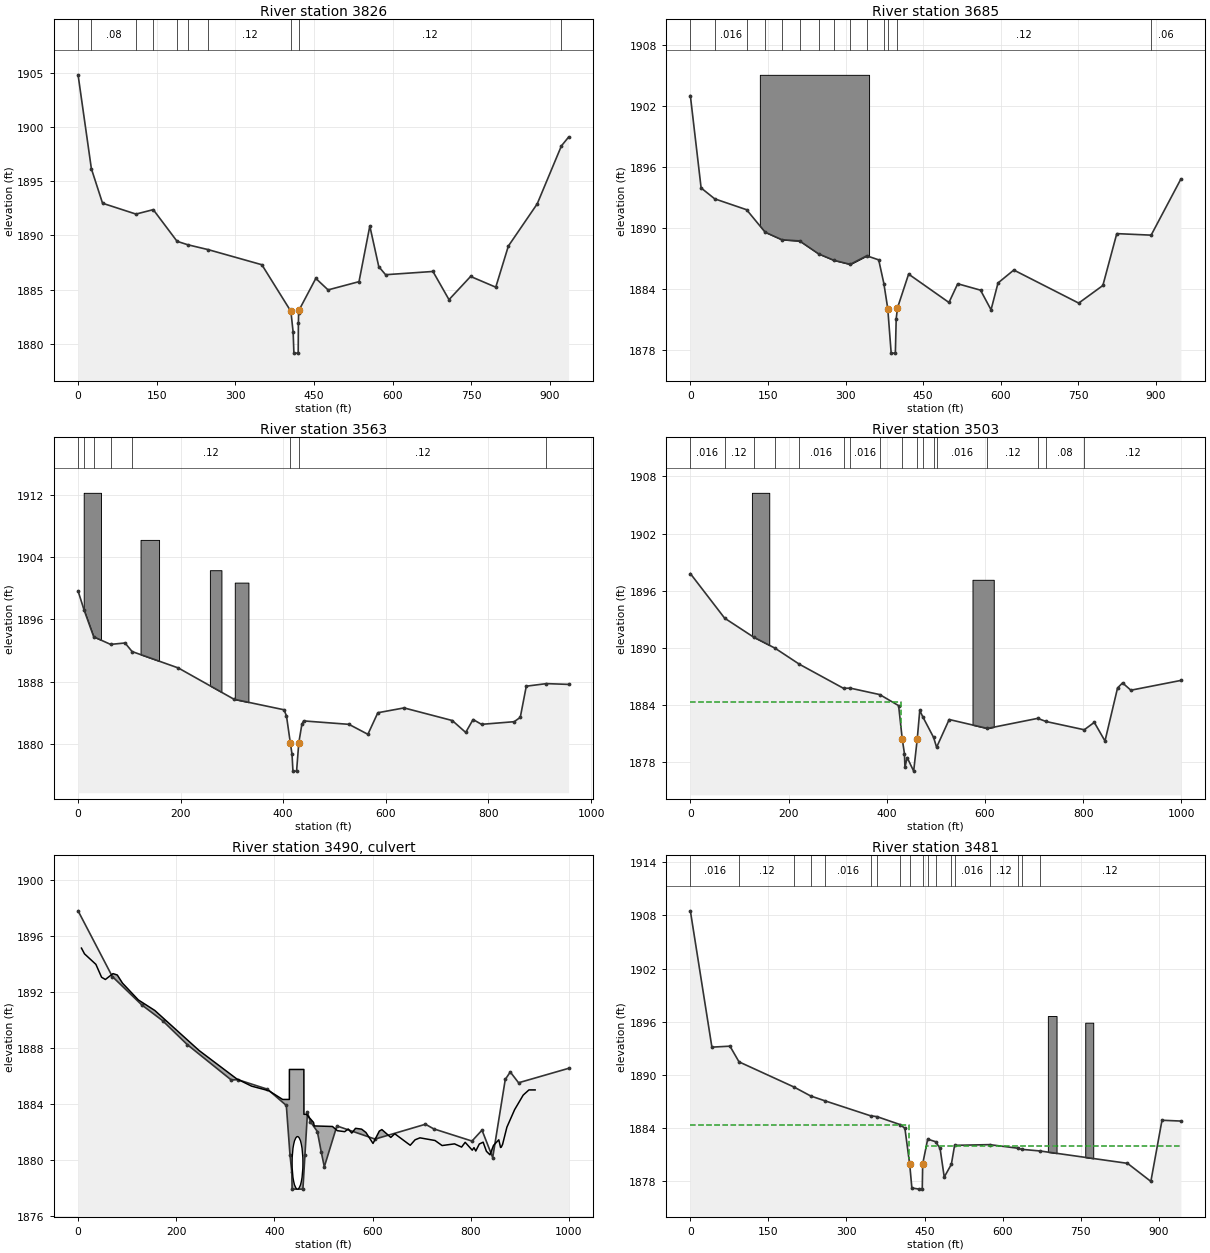
Type RM Length L Ch R = 1 ,3826    ,138.6,141.1,133.1
XS GIS Cut Line= 3
     2174124.933      292403.721     2174000.177      292712.209
      2173823.25      293288.355
#Sta/Elev= 30
       0 1904.81    25.4 1896.15    46.7 1892.97   110.4 1891.97   143.4 1892.38
   188.8 1889.46   209.4 1889.14   248.4 1888.69   350.5  1887.3   405.9    1883
   410.2 1881.06   411.6 1879.15   419.8 1879.15   420.2 1881.94   420.6 1882.85
   421.7 1883.14   453.4 1886.04   476.8 1884.98   535.8 1885.74   556.4 1890.87
   573.5 1887.12   586.5 1886.38   676.8 1886.68   707.4 1884.08   748.6 1886.22
   796.6 1885.23   820.6 1889.02   875.6 1892.91   921.8 1898.26   935.5 1899.07
#Mann= 10 ,-1 , 0
       0     .12       0    25.4     .08       0   110.4    .016       0
   143.4     .06       0   188.8     .08       0   209.4     .06       0
   248.4     .12       0   405.9     .04       0   421.7     .12       0
   921.8     .06       0
Bank Sta=405.9,421.7
XS Rating Curve= 0 ,0
Exp/Cntr=0.3,0.1

Type RM Length L Ch R = 1 ,3685    ,120.2,121.8,119.9
XS GIS Cut Line= 4
     2174016.127      292379.134     2173860.084      292693.747
     2173831.287      292801.684     2173710.127      293271.553
#Sta/Elev= 30
       0 1903.06    20.8 1893.98    47.1 1892.91   108.7 1891.84   144.5 1889.63
   176.8 1888.89   211.1 1888.77   247.8  1887.5   277.2 1886.87     309 1886.47
   340.9 1887.31     364 1886.91     374 1884.58   381.5 1882.12   388.1 1877.74
   396.2 1877.74   397.8  1881.1   400.2 1882.17   421.8 1885.51   499.8 1882.72
   516.7 1884.56   560.8 1883.93   581.1    1882   594.6 1884.64   625.1 1885.91
   750.5 1882.66   797.2 1884.39   824.1 1889.49   890.5 1889.34     948 1894.86
#Mann= 14 ,-1 , 0
       0     .12       0    47.1    .016       0   108.7     .12       0
   144.5     .08       0   176.8     .12       0   211.1     .08       0
   247.8     .12       0   277.2     .08       0     309     .12       0
   340.9     .06       0     374     .12       0   381.5     .04       0
   400.2     .12       0   890.5     .06       0
#Block Obstruct= 1 ,-1
   134.3   345.41905.104
Bank Sta=381.5,400.2
XS Rating Curve= 0 ,0
Exp/Cntr=0.3,0.1

Type RM Length L Ch R = 1 ,3563    ,54.8,60.6,88.9
XS GIS Cut Line= 4
      2173975.06      292365.077     2173736.031      292693.742
     2173704.395      292808.863      2173613.88        293229.8
#Sta/Elev= 30
       0 1899.66      12 1897.16    30.5 1893.77    63.4  1892.8    91.6 1892.98
   105.3 1891.88   195.5 1889.77   304.1 1885.75   401.5  1884.4   406.3 1883.61
   413.8 1880.15   417.1  1878.7   418.9 1876.52     426 1876.52   430.3 1880.16
   436.3 1882.53   439.7 1882.97   528.1 1882.53     565 1881.25   584.4 1884.02
   635.5 1884.64   729.5 1883.02   755.7 1881.49   770.1 1883.15   786.5 1882.53
   850.3 1882.87   862.1 1883.43   873.8 1887.43   913.1 1887.76   956.3 1887.66
#Mann= 8 ,-1 , 0
       0     .12       0      12    .016       0    30.5     .08       0
    63.4    .016       0   105.3     .12       0   413.8     .04       0
   430.3     .12       0   913.1     .06       0
#Block Obstruct= 4 ,-1
      11    44.71912.267   121.8   157.91906.221     257   279.51902.328
   305.5   332.11900.735
Bank Sta=413.8,430.3
XS Rating Curve= 0 ,0
Exp/Cntr=0.5,0.3

Type RM Length L Ch R = 1 ,3503    ,21.5,21.5,43.4
BEGIN DESCRIPTION:
Merged DS Survey WAC032BU
END DESCRIPTION:
XS GIS Cut Line= 4
     2173954.067      292351.858     2173708.041      292646.402
     2173624.864      292769.359     2173507.934      293221.408
#Sta/Elev= 30
       0 1897.79    69.8  1893.1   129.6 1891.08   172.2 1889.95   222.2 1888.25
     312 1885.72   325.7 1885.74   385.8 1885.06   424.2  1883.9   431.6  1880.4
   436.1 1878.85   437.1  1877.4   441.6 1878.44   454.9 1877.01   462.2  1880.4
   467.3  1883.4   473.3 1882.74   495.5 1880.55   501.6 1879.52   527.2 1882.44
     605  1881.5   707.6 1882.56   724.5 1882.23   802.4 1881.36   822.8 1882.14
   844.6 1880.18   870.2 1885.76   880.4 1886.29   897.3 1885.52   999.2 1886.55
#Mann= 17 ,-1 , 0
       0    .016       0    69.8     .12       0   129.6     .08       0
   172.2     .12       0   222.2    .016       0     312     .12       0
   325.7    .016       0   385.8     .12       0   431.6     .04       0
   462.2    .016       0   473.3    .016       0   495.5     .12       0
   501.6    .016       0     605     .12       0   707.6    .016       0
   724.5     .08       0   802.4     .12       0
#XS Ineff= 2 , 0
             429 1884.33     465            1882
Permanent Ineff=
       F       F
#Block Obstruct= 2 ,-1
   125.4   160.71906.282   574.7     6181897.135
Bank Sta=431.6,462.2
XS Rating Curve= 0 ,0
Exp/Cntr=0.5,0.3

Type RM Length L Ch R = 2 ,3490    ,,,
BEGIN DESCRIPTION:
Merged US Survey WAC030RP.
Freeland Avenue
END DESCRIPTION:
Bridge Culvert--1,0,-1,-1, 0
Deck Dist Width WeirC Skew NumUp NumDn MinLoCord MaxHiCord MaxSubmerge Is_Ogee
3,15,2.6,0, 60, 60, , , 0.98, 0, 0,0,,
     6.9    13.1    36.3    47.9    55.6    71.1    79.9    90.5   122.8   156.3
   246.6   322.7   353.4   388.7  416.67  430.39  430.49  459.96   460.1  465.17
  479.63   481.1   518.2   528.1   543.1   550.3   557.5   565.2   577.6   586.4
   600.8   613.6   618.8     637   645.1   676.6   686.5   696.4   727.1   741.5
   766.8   781.2   788.5   802.9   806.5   810.1   817.3   825.1   831.8     839
   846.2     857   860.6   862.2   864.7   873.5   889.2   906.7   918.4     931
 1895.13 1894.72 1893.97 1893.05 1892.89 1893.31 1893.21 1892.63 1891.43 1890.68
 1887.82 1885.81 1885.28 1884.95 1884.33 1884.33 1886.47 1886.47 1883.27 1883.27
 1882.69 1882.44  1882.4  1882.1 1882.03 1882.22 1881.93 1882.27 1882.21 1881.97
 1881.19 1882.07 1882.18 1881.62 1881.88 1881.06 1881.45 1881.59  1881.4 1881.04
 1881.16 1880.93 1881.27 1880.71 1880.89 1880.65 1881.15 1881.28 1880.63 1880.38
 1881.05 1881.45  1880.9 1880.94 1881.12 1882.35  1883.6 1884.64 1885.01 1885.01
                                                                                
                                                                                
                                                                                
                                                                                
                                                                                
                                                                                
    -4.2       2    25.2    36.8    44.5      60    68.8    79.4   111.7   145.2
   235.5   311.6   342.3   377.6  405.57  419.29  419.39  448.86  448.96  468.63
   488.7   507.1     517   528.4     532   539.2   546.4   554.1   566.5   575.3
   589.7   602.5   607.7   625.9     634   665.5   675.4   685.3     716   730.4
   755.7   770.1   777.4   791.8   795.4     799   806.2     814   820.7   827.9
   835.1   845.9   849.5   851.1   853.6   862.4   878.1   895.6   907.3   919.9
 1895.13 1894.72 1893.97 1893.05 1892.89 1893.31 1893.21 1892.63 1891.43 1890.68
 1887.82 1885.81 1885.28 1884.95 1884.33 1884.33 1886.47 1886.47 1883.27 1883.27
 1882.36  1882.4  1882.1 1882.17 1882.03 1882.22 1881.93 1882.27 1882.21 1881.97
 1881.19 1882.07 1882.18 1881.62 1881.88 1881.06 1881.45 1881.59  1881.4 1881.04
 1881.16 1880.93 1881.27 1880.71 1880.89 1880.65 1881.15 1881.28 1880.63 1880.38
 1881.05 1881.45  1880.9 1880.94 1881.12 1882.35  1883.6 1884.64 1885.01 1885.01
                                                                                
                                                                                
                                                                                
                                                                                
                                                                                
                                                                                
BR Coef=-1 , 1 , 0 ,, 0 ,,,0.8,0,1.2,0,
WSPro=,,,, 1 ,,,, 0 ,,,, 0 ,,,,-1 ,-1 ,-1 , 0 , 0 , 0 , 0 , 0
Culvert=5,3.75,22,15,0.024,0.5,1,41,1,1877.93,447,1877.12,435.2, Culvert #1 , 0 ,3
     447   435.2
BC Culvert Barrel=1,Barrel #1,0
Culvert Bottom n=0.04
BR U #Sta/Elev= 30
       0 1897.79    69.8  1893.1   129.6 1891.08   172.2 1889.95   222.2 1888.25
     312 1885.72   325.7 1885.74   385.8 1885.06   424.2  1883.9   431.6  1880.4
   435.4 1879.12     436 1877.93     458 1877.93   462.2  1880.4   467.3  1883.4
   473.3 1882.74   487.4 1882.04   495.5 1880.55   501.6 1879.52   527.2 1882.44
     605  1881.5   707.6 1882.56   724.5 1882.23   802.4 1881.36   822.8 1882.14
   844.6 1880.18   870.2 1885.76   880.4 1886.29   897.3 1885.52   999.2 1886.55
BR U #Mann= 17
       0    .016    69.8     .12   129.6     .08   172.2     .12   222.2    .016
     312     .12   325.7    .016   385.8     .12   431.6     .04   462.2    .016
   473.3    .016   495.5     .12   501.6    .016     605     .12   707.6    .016
   724.5     .08   802.4     .12
BR D #Sta/Elev= 30
       0 1908.52    41.4 1893.14    76.1 1893.25    93.5 1891.48   198.8 1888.65
   231.2 1887.63   259.3 1887.07   300.2 1885.29   346.5 1885.39   358.6  1885.3
   402.6 1884.41   412.2 1883.99   421.5  1879.9   424.2 1877.12   446.2 1877.12
   446.4 1879.96     456 1882.76   471.1 1882.47   479.8 1881.72   487.8 1878.48
   501.5 1879.92   507.7 1882.06   574.9 1882.14   630.1 1881.73   636.3 1881.61
   671.1 1881.43   839.9 1880.03   884.8 1877.99   906.2 1884.89   942.5  1884.8
BR D #Mann= 18
       0    .016    93.5     .12   198.8     .08   231.2     .12   259.3    .016
   346.5     .12   358.6    .016   402.6     .12   421.5     .04   446.4    .016
     456     .12   471.1    .016   501.5     .12   507.7    .016   574.9     .12
   630.1    .016   636.3     .08   671.1     .12
BC Design=,, 0 ,, 0 ,,0,,,,
BC HTab HWMax=0
BC HTab TWMax=0
BC HTab MaxFlow=0
BC Use User HTab Curves=0
BC User HTab FreeFlow(D)= 0

Type RM Length L Ch R = 1 ,3481    ,48.3,49.7,46.4
BEGIN DESCRIPTION:
Merged US Survey WAC028BD
END DESCRIPTION:
XS GIS Cut Line= 4
      2173864.22      292308.718     2173688.323      292637.809
     2173575.839      292802.142     2173431.719      293143.109
#Sta/Elev= 30
       0 1908.52    41.4 1893.14    76.1 1893.25    93.5 1891.48   198.8 1888.65
   231.2 1887.63   259.3 1887.07   346.5 1885.39   358.6  1885.3   402.6 1884.41
   412.2 1883.99   421.5  1879.9   425.6 1877.25   439.5 1877.12   445.6 1877.19
   446.4 1879.96     456 1882.76   471.1 1882.47   479.8 1881.72   487.8 1878.48
   501.5 1879.92   507.7 1882.06   574.9 1882.14   630.1 1881.73   636.3 1881.61
   671.1 1881.43   839.9 1880.03   884.8 1877.99   906.2 1884.89   942.5  1884.8
#Mann= 18 ,-1 , 0
       0    .016       0    93.5     .12       0   198.8     .08       0
   231.2     .12       0   259.3    .016       0   346.5     .12       0
   358.6    .016       0   402.6     .12       0   421.5     .04       0
   446.4    .016       0     456     .12       0   471.1    .016       0
   501.5     .12       0   507.7    .016       0   574.9     .12       0
   630.1    .016       0   636.3     .08       0   671.1     .12       0
#XS Ineff= 2 , 0
             420 1884.33   452.2            1882
Permanent Ineff=
       F       F
#Block Obstruct= 2 ,-1
   686.9   703.6 1896.65   758.7   774.11895.899
Bank Sta=421.5,446.4
XS Rating Curve= 0 ,0
Exp/Cntr=0.5,0.3

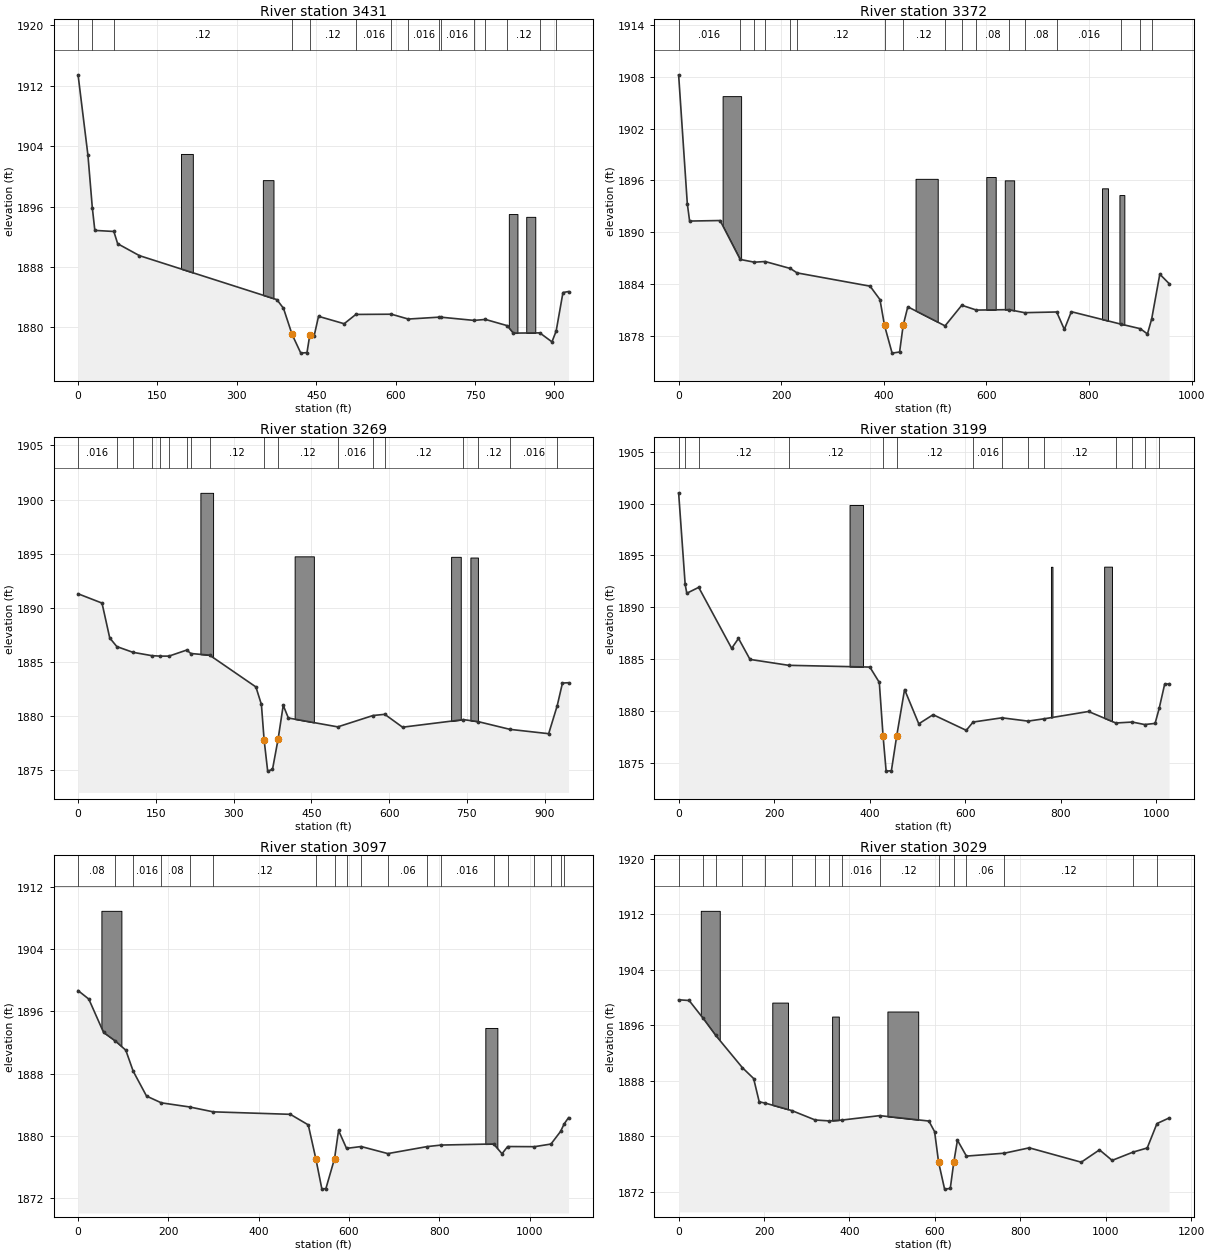
Type RM Length L Ch R = 1 ,3431    ,61.5,59.3,26.8
XS GIS Cut Line= 4
     2173833.449      292301.521     2173653.353      292608.553
     2173543.776      292750.677     2173413.586      293119.549
#Sta/Elev= 30
       0 1913.43    18.7 1902.76    26.9 1895.86    31.7 1892.84    67.6  1892.7
    74.8 1891.08     116  1889.5   375.6 1883.68   388.1 1882.53   404.3 1879.08
   420.8  1876.6   432.5 1876.67   437.8    1879   446.1 1878.91   454.3 1881.47
   502.7 1880.49   524.8 1881.72     592 1881.75   623.9 1881.11     682 1881.36
   685.1 1881.36   748.2 1880.93   769.5 1881.06   810.6 1880.24   822.2 1879.25
   872.3 1879.28   895.3 1878.09   903.2 1879.51   916.1 1884.62   926.6 1884.75
#Mann= 15 ,-1 , 0
       0     .12       0    26.9    .016       0    67.6     .12       0
   404.3     .04       0   437.8     .12       0   524.8    .016       0
     592     .08       0   623.9    .016       0     682     .08       0
   685.1    .016       0   748.2     .12       0   769.5    .016       0
   810.6     .12       0   872.3     .06       0   903.2     .12       0
#Block Obstruct= 4 ,-1
   194.4   216.81902.961   349.1   369.21899.492   813.8   830.11895.003
   846.7   863.81894.637
Bank Sta=404.3,437.8
XS Rating Curve= 0 ,0
Exp/Cntr=0.3,0.1

Type RM Length L Ch R = 1 ,3372    ,103.6,103,101.3
XS GIS Cut Line= 4
     2173711.351      292231.723     2173591.412      292583.405
     2173541.472      292664.565     2173391.719      293130.295
#Sta/Elev= 30
       0 1908.24    16.9 1893.31    21.4 1891.29    80.8 1891.35     120 1886.84
   147.7 1886.52   168.5  1886.6   217.8 1885.79   230.9 1885.28   373.2 1883.74
   392.4 1882.19   401.3 1879.19   416.1 1875.98   430.7 1876.11   437.7 1879.21
   446.7 1881.35   519.3 1879.14   551.9 1881.53   580.5 1880.97   643.6 1881.02
   674.4 1880.67   736.9 1880.75   751.8 1878.73   765.5 1880.78   862.1 1879.34
     900 1878.81   913.8  1878.2   922.1 1879.95   937.9 1885.13     956 1884.04
#Mann= 17 ,-1 , 0
       0    .016       0     120     .12       0   147.7     .06       0
   168.5     .12       0   217.8     .06       0   230.9     .12       0
   401.3     .04       0   437.7     .12       0   519.3    .016       0
   551.9     .12       0   580.5     .08       0   643.6     .12       0
   674.4     .08       0   736.9    .016       0   862.1     .12       0
     900     .06       0   922.1     .12       0
#Block Obstruct= 6 ,-1
    85.7   121.81905.769   461.8     5051896.185   599.7     6181896.397
   635.7     6541896.007   825.2     8371895.083   859.2   868.81894.302
Bank Sta=401.3,437.7
XS Rating Curve= 0 ,0
Exp/Cntr=0.3,0.1

Type RM Length L Ch R = 1 ,3269    ,73.7,70.1,67.4
XS GIS Cut Line= 4
      2173658.51      292235.828     2173505.536      292516.822
     2173454.545      292628.568     2173350.393      293121.121
#Sta/Elev= 30
       0 1891.29    46.2 1890.43    61.1 1887.21    74.8 1886.41   105.9 1885.88
   142.5 1885.57   158.2 1885.53   175.4 1885.53   209.7 1886.09   217.5 1885.77
   253.8 1885.62   343.1 1882.68   353.7 1881.06   358.9  1877.8   365.8  1874.9
   375.1 1875.06   385.9 1877.85   395.8 1880.98   405.7 1879.81     501 1878.99
     569 1880.04   591.7 1880.15     626 1878.96   743.4 1879.66   772.3 1879.47
   833.2 1878.76   907.9 1878.36   924.4 1880.95   934.5 1883.04   946.2 1883.07
#Mann= 18 ,-1 , 0
       0    .016       0    74.8     .12       0   105.9    .016       0
   142.5     .12       0   158.2    .016       0   175.4     .06       0
   209.7     .12       0   217.5    .016       0   253.8     .12       0
   358.9     .04       0   385.9     .12       0     501    .016       0
     569     .08       0   591.7     .12       0   743.4     .08       0
   772.3     .12       0   833.2    .016       0   924.4     .12       0
#Block Obstruct= 4 ,-1
     236   260.5 1900.62   417.8   454.9 1894.75   719.7   738.31894.706
   756.9   771.41894.641
Bank Sta=358.9,385.9
XS Rating Curve= 0 ,0
Exp/Cntr=0.3,0.1

Type RM Length L Ch R = 1 ,3199    ,104.4,101.8,48.4
XS GIS Cut Line= 4
      2173523.98      292112.148     2173424.168      292494.039
     2173405.724      292645.927      2173331.95      293118.951
#Sta/Elev= 30
       0 1901.05    13.7  1892.2    17.1 1891.35      42 1891.92     111 1886.03
   125.3 1886.99   149.4 1884.96   230.2 1884.39   400.2 1884.22     420 1882.74
   427.9 1877.55   434.3 1874.17   445.3 1874.21   456.4 1877.56   472.9 1882.05
   502.6 1878.74   532.6 1879.62     602 1878.11   616.3 1878.91   676.6 1879.32
   731.2    1879   765.7 1879.23   857.9 1879.93     915 1878.82   949.5 1878.91
   975.3 1878.67   997.2 1878.78  1005.7 1880.22  1017.1 1882.54  1026.5 1882.61
#Mann= 14 ,-1 , 0
       0     .12       0    13.7    .016       0      42     .12       0
   230.2     .12       0   427.9     .04       0   456.4     .12       0
   616.3    .016       0   676.6     .08       0   731.2    .016       0
   765.7     .12       0     915    .016       0   949.5     .06       0
   975.3    .016       0  1005.7     .12       0
#Block Obstruct= 3 ,-1
   357.7     3861899.874   779.2   782.41893.907   890.6     9071893.921
Bank Sta=427.9,456.4
XS Rating Curve= 0 ,0
Exp/Cntr=0.3,0.1

Type RM Length L Ch R = 1 ,3097    ,60.3,68.7,57.2
XS GIS Cut Line= 4
     2173336.289      292032.949     2173316.761      292528.756
     2173341.714      292644.842     2173317.846      293115.696
#Sta/Elev= 30
       0 1898.69    23.8 1897.59    56.5 1893.29    82.7 1892.18   105.7 1891.01
   122.1  1888.3   151.7 1885.09   184.5 1884.22   246.9 1883.69   299.4 1883.06
   470.2 1882.74   509.9 1881.38   526.6 1877.04   540.1  1873.1     549 1873.18
   568.1 1877.03     577 1880.66   594.7 1878.35     627 1878.59   686.2 1877.68
     773 1878.58   804.4 1878.78   920.4 1878.92   939.1 1877.66   951.6 1878.59
    1011 1878.57  1047.5 1878.91  1068.7 1880.53  1076.7  1881.5  1086.4 1882.31
#Mann= 19 ,-1 , 0
       0     .08       0    82.7     .12       0   122.1    .016       0
   184.5     .08       0   246.9    .016       0   299.4     .12       0
   526.6     .04       0   568.1     .12       0   594.7     .06       0
     627     .12       0   686.2     .06       0     773     .12       0
   804.4    .016       0   920.4     .12       0   951.6    .016       0
    1011     .06       0  1047.5    .016       0  1068.7     .12       0
  1076.7    .016       0
#Block Obstruct= 2 ,-1
    51.7      961908.965   902.1   928.81893.872
Bank Sta=526.6,568.1
XS Rating Curve= 0 ,0
Exp/Cntr=0.3,0.1

Type RM Length L Ch R = 1 ,3029    ,111.3,117.3,111.8
XS GIS Cut Line= 4
     2173259.944      291982.699     2173264.685      292553.468
     2173286.133      292660.108     2173254.274      293127.987
#Sta/Elev= 30
       0 1899.67    24.6 1899.57    57.4    1897      87 1894.53   149.3 1889.89
   175.6 1888.33   188.7 1884.97   203.1 1884.78     265 1883.71   319.9 1882.35
   352.7 1882.22   382.1 1882.34   470.8 1882.98     586  1882.2   599.4 1880.67
   608.8 1876.25   622.8 1872.39   636.1 1872.49   644.4  1876.3   652.9 1879.44
   673.9 1877.15     763 1877.57   821.1 1878.34   942.8 1876.27   985.5 1878.05
  1015.1 1876.53  1064.4 1877.73  1097.3 1878.32  1120.1 1881.84  1148.5 1882.64
#Mann= 16 ,-1 , 0
       0     .12       0    57.4     .08       0      87     .12       0
   149.3    .016       0   203.1     .08       0     265     .12       0
   319.9    .016       0   352.7     .12       0   382.1    .016       0
   470.8     .12       0   608.8     .04       0   644.4     .12       0
   673.9     .06       0     763     .12       0  1064.4     .06       0
  1120.1     .12       0
#Block Obstruct= 4 ,-1
    51.9    96.3 1912.49   219.3     2561899.269   359.4   375.11897.255
   488.9     5611897.984
Bank Sta=608.8,644.4
XS Rating Curve= 0 ,0
Exp/Cntr=0.3,0.1

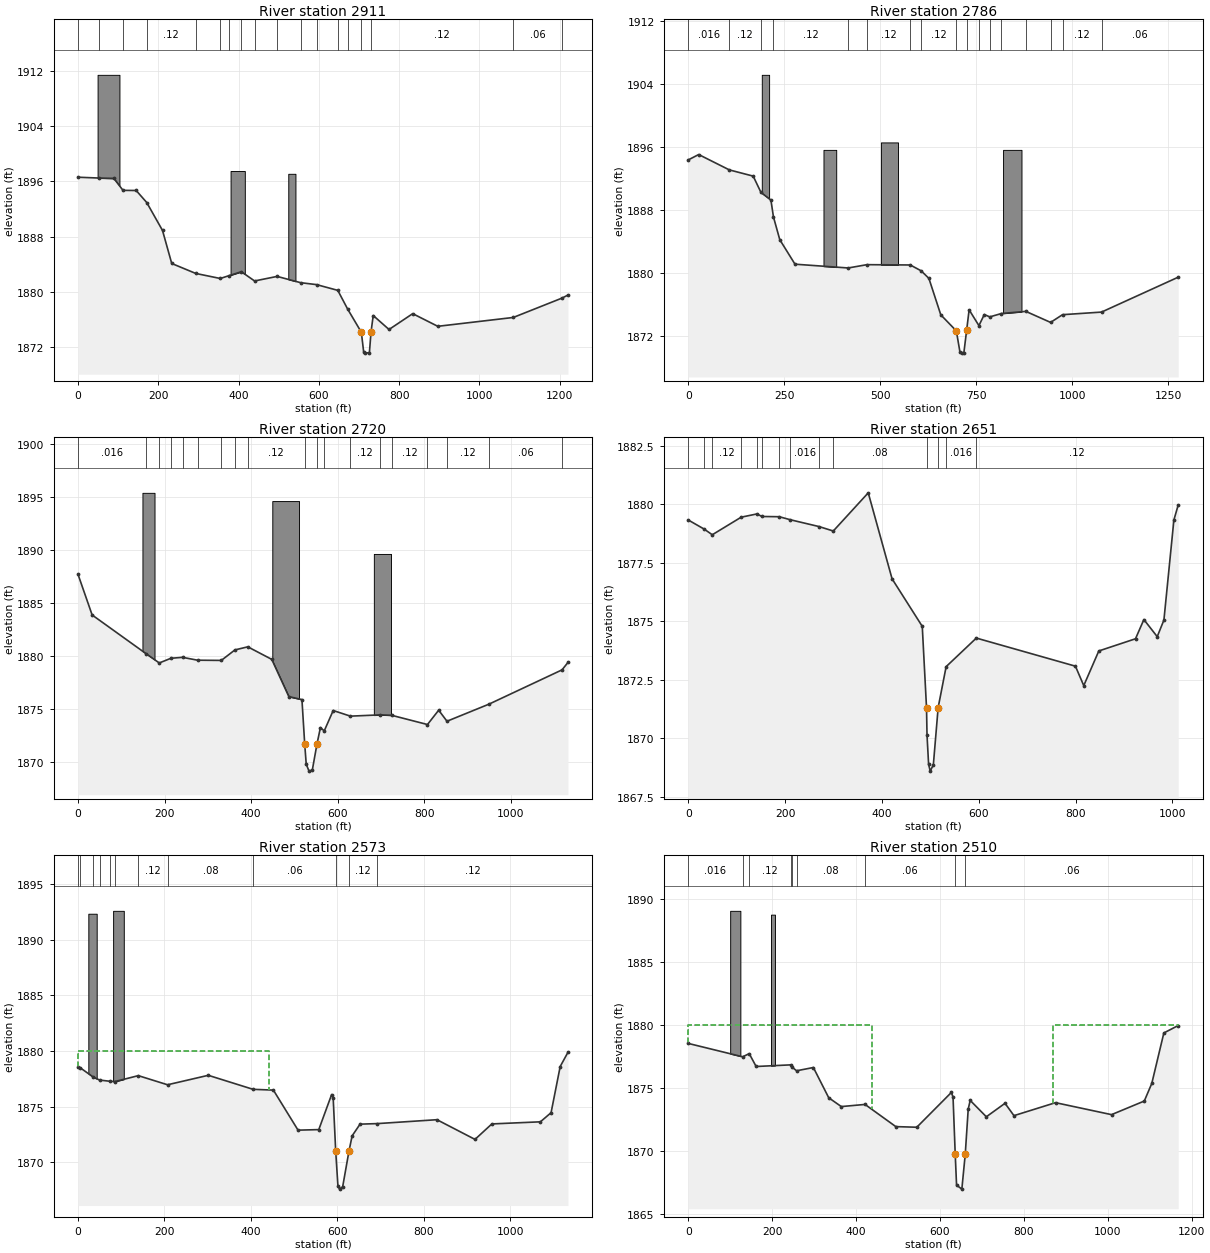
Type RM Length L Ch R = 1 ,2911    ,117.7,124.8,140.8
XS GIS Cut Line= 4
     2173162.806      291924.745     2173160.969      292554.945
     2173170.156      292801.145     2173192.203      293144.723
#Sta/Elev= 30
       0  1896.6    53.1 1896.48    89.2 1896.43   112.1  1894.7   144.9 1894.68
   171.2 1892.94   210.5  1888.9   233.5 1884.12   293.3 1882.68   354.4 1881.95
   377.4 1882.38     407 1882.93   439.9 1881.59   496.1 1882.25     555 1881.34
   594.6 1881.06   647.3 1880.23   671.9 1877.52     706 1874.17   711.7 1871.36
   715.9 1871.15   726.1 1871.23   730.2 1874.24   735.6 1876.59     775 1874.57
     834 1876.86   896.5 1875.03  1084.6 1876.31  1205.5  1879.1  1220.9 1879.55
#Mann= 18 ,-1 , 0
       0    .016       0    53.1     .12       0   112.1    .016       0
   171.2     .12       0   293.3    .016       0   354.4     .12       0
   377.4     .08       0     407     .12       0   439.9    .016       0
   496.1     .08       0     555     .12       0   594.6    .016       0
   647.3     .08       0   671.9     .12       0     706     .04       0
   730.2     .12       0  1084.6     .06       0  1205.5     .12       0
#Block Obstruct= 3 ,-1
    48.7   103.21911.416   380.1   415.61897.501   523.9   541.81897.097
Bank Sta=706,730.2
XS Rating Curve= 0 ,0
Exp/Cntr=0.3,0.1

Type RM Length L Ch R = 1 ,2786    ,71.2,66.6,34.6
BEGIN DESCRIPTION:
Burnt
END DESCRIPTION:
XS GIS Cut Line= 4
     2173126.183      291904.822     2173060.701      292514.995
     2173026.472      292709.953     2173186.005      293146.317
#Sta/Elev= 30
       0 1894.37    27.2 1895.05     107  1893.1   169.1 1892.31   189.4 1890.24
   215.3 1889.27   221.9 1887.13   238.4 1884.24     278 1881.13   416.6 1880.65
   465.5 1881.07   578.3 1881.03   606.6 1880.29   626.8 1879.33   657.8  1874.7
   698.3 1872.66   707.8 1869.95   711.8 1869.84   717.8 1869.84   725.1 1872.73
   731.6 1875.34   757.1 1873.33   771.1 1874.74   785.4 1874.44   815.8 1874.87
   879.3 1875.14   943.8 1873.74   974.9 1874.72  1076.5 1875.05  1276.2 1879.48
#Mann= 17 ,-1 , 0
       0    .016       0     107     .12       0   189.4     .08       0
   221.9     .12       0   416.6    .016       0   465.5     .12       0
   578.3    .016       0   606.6     .12       0   698.3     .04       0
   725.1     .12       0   757.1    .016       0   785.4     .12       0
   815.8     .08       0   879.3     .12       0   943.8    .016       0
   974.9     .12       0  1076.5     .06       0
#Block Obstruct= 4 ,-1
   191.5   210.61905.169   352.2   385.41895.642   501.8   546.31896.589
     820     8681895.642
Bank Sta=698.3,725.1
XS Rating Curve= 0 ,0
Exp/Cntr=0.3,0.1

Type RM Length L Ch R = 1 ,2720    ,68.7,68.9,72.8
XS GIS Cut Line= 4
     2173029.866      292060.197       2172980.2      292534.741
     2172977.801      292667.586     2173179.231      293149.079
#Sta/Elev= 30
       0 1887.68    32.6 1883.86     158 1880.19   187.7 1879.34   214.5 1879.78
   241.4 1879.87   276.1  1879.6     331 1879.58   362.5 1880.57   392.2 1880.86
   447.5 1879.68     487 1876.17   517.3 1875.89   523.7  1871.7   527.2  1869.8
   533.7 1869.15   541.3 1869.26   552.1 1871.72     560 1873.25   568.8 1872.94
   589.5 1874.86   629.2 1874.33     698 1874.45   724.5 1874.41   807.3 1873.54
   833.2 1874.89   852.4 1873.85   949.4 1875.46  1118.2 1878.69  1131.9 1879.39
#Mann= 19 ,-1 , 0
       0    .016       0     158     .08       0   187.7     .12       0
   214.5    .016       0   241.4     .12       0   276.1     .08       0
     331     .12       0   362.5    .016       0   392.2     .12       0
   523.7     .04       0   552.1     .12       0   568.8    .016       0
   629.2     .12       0     698     .08       0   724.5     .12       0
   807.3    .016       0   852.4     .12       0   949.4     .06       0
  1118.2     .12       0
#Block Obstruct= 3 ,-1
   148.8   176.71895.368   448.8   510.61894.591   683.4   723.11889.611
Bank Sta=523.7,552.1
XS Rating Curve= 0 ,0
Exp/Cntr=0.3,0.1

Type RM Length L Ch R = 1 ,2651    ,94.3,77.6,43.3
XS GIS Cut Line= 3
     2172919.839      292081.773     2172911.269      292649.523
     2173048.198      293072.207
#Sta/Elev= 30
       0 1879.32      33 1878.93    49.6 1878.69   109.3 1879.44   142.1 1879.58
     152 1879.47     188 1879.46     211 1879.33   270.1 1879.04   299.6 1878.85
   371.8 1880.48     421 1876.81   483.4 1874.78   492.2  1871.3   493.2 1870.14
   496.5 1868.89   499.8  1868.6   506.3 1868.87   516.2 1871.31   532.7 1873.06
   595.1 1874.28   799.8 1873.08     817 1872.25   848.1 1873.73   923.9 1874.25
   941.2 1875.07   968.8 1874.34   982.6 1875.05  1003.2 1879.32  1012.1 1879.96
#Mann= 14 ,-1 , 0
       0    .016       0      33     .08       0    49.6     .12       0
   109.3    .016       0   142.1     .12       0     152    .016       0
     188     .12       0     211    .016       0   270.1     .08       0
   299.6     .08       0   492.2     .04       0   516.2     .12       0
   532.7    .016       0   595.1     .12       0
Bank Sta=492.2,516.2
XS Rating Curve= 0 ,0
Exp/Cntr=0.3,0.1

Type RM Length L Ch R = 1 ,2573    ,69.9,63.4,65
BEGIN DESCRIPTION:
Not Burnt
END DESCRIPTION:
XS GIS Cut Line= 5
     2172796.884      292003.491     2172735.344      292155.651
      2172824.39      292563.757     2172877.805      292671.993
     2173034.891      293073.973
#Sta/Elev= 30
       0 1878.53     4.2 1878.52    35.6 1877.65    50.2 1877.39    74.9 1877.28
    85.6 1877.26   139.5 1877.79   207.2 1876.97   301.5 1877.82   405.2 1876.56
   452.2 1876.49   509.3 1872.89   557.3 1872.94     587 1876.09   590.6  1875.8
  596.44 1871.01   601.6 1867.88   605.3 1867.59   612.6 1867.81   627.2 1871.01
   634.5 1872.38   652.8 1873.43   693.1 1873.48   830.8 1873.83   918.9 1872.06
   957.9 1873.45  1070.3 1873.64    1095 1874.46  1116.1 1878.61  1134.1 1879.89
#Mann= 12 ,-1 , 0
       0    .016       0     4.2     .06       0    35.6     .12       0
    50.2    .016       0    74.9     .12       0    85.6    .016       0
   139.5     .12       0   207.2     .08       0   405.2     .06       0
  596.44     .04       0   627.2     .12       0   693.1     .12       0
#XS Ineff= 2 , 0
             441    1880
Permanent Ineff=
       F       F
#Block Obstruct= 2 ,-1
    23.8    43.21892.344    81.2   105.91892.604
Bank Sta=596.44,627.2
XS Rating Curve= 0 ,0
Exp/Cntr=0.5,0.3

Type RM Length L Ch R = 1 ,2510    ,24.1,23.5,34.5
BEGIN DESCRIPTION:
Merged DS Survey WAC022BU
END DESCRIPTION:
XS GIS Cut Line= 5
     2172770.947      291984.811     2172693.038      292221.869
     2172755.284      292577.432     2172860.948       292738.16
     2173008.117      293072.152
#Sta/Elev= 30
       0 1878.51   129.7 1877.45   145.3  1877.7   161.8 1876.68   244.7 1876.81
   248.2 1876.61   258.2 1876.34   298.2  1876.6   334.8  1874.2   364.8  1873.5
   421.4 1873.67   494.7 1871.91   544.7 1871.86   627.1 1874.62   631.1 1874.26
   636.3 1869.74   639.5 1867.27   652.1 1866.95   660.2 1869.71   667.3  1873.3
     672 1873.99   710.5 1872.69     755 1873.76   776.3 1872.78   875.4 1873.81
  1008.9 1872.86    1087 1873.94  1104.9 1875.34  1133.6 1879.34  1167.8 1879.93
#Mann= 9 ,-1 , 0
       0    .016       0   129.7     .08       0   145.3     .12       0
   244.7     .06       0   248.2     .12       0   258.2     .08       0
   421.4     .06       0   636.3     .04       0   660.2     .06       0
#XS Ineff= 4 ,-1
       0     438    1880     438  619.15 1872.03  680.24     869  1873.3
     869    1200    1880
Permanent Ineff=
       F       F       F       F
#Block Obstruct= 2 ,-1
    99.9   124.21889.031   197.2   206.61888.729
Bank Sta=636.3,660.2
XS Rating Curve= 0 ,0
Exp/Cntr=0.5,0.3

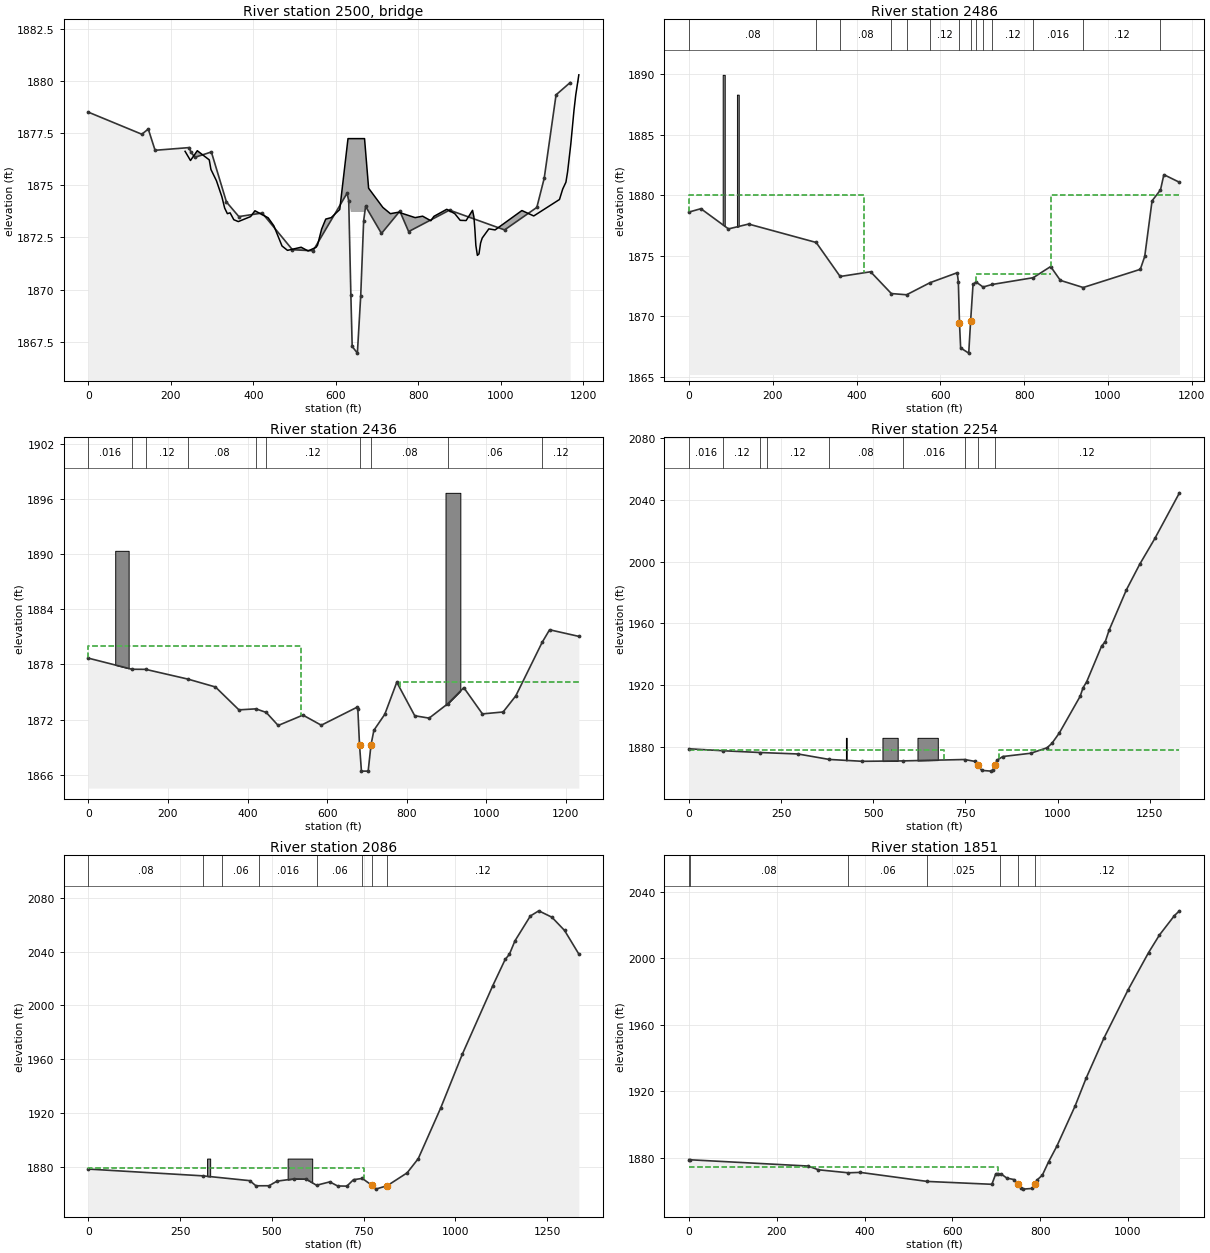
Type RM Length L Ch R = 3 ,2500    ,,,
BEGIN DESCRIPTION:
Merged DS Survey WAC020RP
Hines Avenue
END DESCRIPTION:
Bridge Culvert--1,0,-1,-1, 0
Deck Dist Width WeirC Skew NumUp NumDn MinLoCord MaxHiCord MaxSubmerge Is_Ogee
5,15,2.6,0, 60, 60, , , 0.98, 0, 0,0,,
   234.5   247.6   264.1   293.1   297.2   310.5   323.7   330.4     337   343.6
   352.6   363.5   393.3   403.8   435.9   449.6   469.4   482.7   515.8   532.7
   552.2   555.5   565.4   575.4   588.6  609.36  629.34  669.46  679.31   713.8
   732.1   751.9   792.1   810.2   830.1   837.5   868.7   888.2   901.3   915.6
   931.2   934.5   936.9   939.2   942.9   946.8   950.7   954.6   970.7   985.8
  1050.8  1079.5  1141.9  1149.7  1157.5  1161.5  1169.3  1177.1  1181.3  1188.8
 1876.63 1876.19 1876.66 1876.22 1875.76 1875.22 1874.45 1873.91 1873.64 1873.68
 1873.35 1873.26  1873.5 1873.78 1873.44 1873.06 1872.09 1871.88 1872.03 1871.85
 1872.03 1872.13  1872.9 1873.38 1873.45 1873.84 1877.24 1877.24 1874.86 1873.94
 1873.64 1873.71 1873.45 1873.52  1873.3 1873.51 1873.85 1873.64 1873.32 1873.31
  1873.8 1873.48 1872.88 1872.12 1871.64 1871.71 1872.23 1872.47 1872.91 1872.86
 1873.79 1873.53 1874.32 1874.82 1875.15 1875.64 1876.97 1878.61 1879.33  1880.3
                                                                                
                                                                                
                                                 1873.72 1873.72
                                                                                
                                                                                
                                                                                
     246   259.1   275.6   288.9   295.5   304.6   308.7     322   335.2   341.9
   348.5   355.1   364.1     375   404.8   415.3   437.9   447.4   461.1   480.9
   494.2   527.3   544.2   563.7     567   576.9   586.9   600.1  620.86  640.84
  680.96  690.81   725.3   743.6   763.4   777.5   794.1   803.6   821.7   841.6
     849   880.2   899.7   912.8   927.1   942.7     946   948.4   950.7   954.4
   958.3   962.2   966.1   981.6   997.3  1024.3  1040.2  1062.3  1087.1    1088
 1876.63 1876.19 1876.66 1876.39 1876.42 1876.22 1875.76 1875.22 1874.45 1873.91
 1873.64 1873.68 1873.35 1873.26  1873.5 1873.78 1873.47 1873.44 1873.06 1872.09
 1871.88 1872.03 1871.85 1872.03 1872.13  1872.9 1873.38 1873.45 1873.84 1877.24
 1877.24 1874.86 1873.94 1873.64 1873.71 1873.54 1873.58 1873.45 1873.52  1873.3
 1873.51 1873.85 1873.64 1873.32 1873.31  1873.8 1873.48 1872.88 1872.12 1871.64
 1871.71 1872.23 1872.47  1872.9 1872.86 1873.28 1873.39 1873.79 1873.52    1874
                                                                                
                                                                                
                                                                         1873.72
 1873.72
                                                                                
                                                                                
BR Coef=-1 , 1 , 0 ,, 0 ,,,0.8,0,1.2,0,
WSPro=,,,, 1 ,,,, 0 ,,,, 0 ,,,,-1 ,-1 ,-1 , 0 , 0 , 0 , 0 , 0
BC Design=,, 0 ,, 0 ,,0,,,,
BC HTab HWMax=0
BC HTab TWMax=0
BC HTab MaxFlow=0
BC Use User HTab Curves=0
BC User HTab FreeFlow(D)= 0

Type RM Length L Ch R = 1 ,2486    ,44.4,50.3,53.7
BEGIN DESCRIPTION:
Merged US Survey WAC018BD
END DESCRIPTION:
XS GIS Cut Line= 6
      2172758.57       291979.25     2172686.819      292218.315
     2172729.315      292580.737     2172766.853      292637.305
     2172864.396      292801.051     2172971.916      293078.789
#Sta/Elev= 30
       0 1878.61    28.5 1878.89    94.4 1877.22   142.4 1877.62   303.7  1876.1
   360.9 1873.29   433.6 1873.68   483.1 1871.88   519.5 1871.78   575.6 1872.78
   640.3  1873.6     643 1872.87   645.7 1869.47   648.5 1867.39   667.8 1866.96
   672.3 1869.61   678.1 1872.64   685.3 1872.84     702 1872.42   723.6 1872.63
   821.7 1873.19   863.3 1874.11   886.5 1872.97     941 1872.38  1077.3 1873.88
  1087.9 1874.95  1105.4 1879.54  1125.5 1880.44  1133.6  1881.7  1170.8 1881.07
#Mann= 14 ,-1 , 0
       0     .08       0   303.7     .12       0   360.9     .08       0
   483.1     .12       0   519.5    .016       0   575.6     .12       0
   645.7     .04       0   672.3    .016       0   685.3     .12       0
     702    .016       0   723.6     .12       0   821.7    .016       0
     941     .12       0  1125.5     .06       0
#XS Ineff= 4 ,-1
       0     417    1880     417  639.68 1871.93   685.3     863 1873.49
     863    1200    1880
Permanent Ineff=
       F       F       F       F
#Block Obstruct= 2 ,-1
    80.5    85.41889.946   114.5   118.81888.309
Bank Sta=645.7,672.3
XS Rating Curve= 0 ,0
Exp/Cntr=0.5,0.3

Type RM Length L Ch R = 1 ,2436    ,180.9,181.8,182.2
XS GIS Cut Line= 5
      2172751.89      291971.064     2172678.583      292216.419
     2172693.935      292612.843     2172730.826      292678.161
     2172978.077      293117.976
#Sta/Elev= 30
       0 1878.69   109.8 1877.48     144 1877.47   250.2 1876.41   319.4 1875.55
   378.4 1873.06   421.1 1873.17     447 1872.78     477 1871.36   539.3 1872.49
   585.3 1871.39   675.8 1873.36   677.1 1873.19   681.4 1869.23   686.2 1866.39
   703.1 1866.39   710.3 1869.26   717.5 1870.84   744.9 1872.58     775 1876.07
   820.1 1872.42   856.3 1872.16   903.2 1873.73   943.4 1875.48   990.2 1872.62
  1042.2 1872.83  1074.1 1874.59  1140.1  1880.4  1158.9 1881.78  1232.4 1881.06
#Mann= 10 ,-1 , 0
       0    .016       0   109.8     .08       0     144     .12       0
   250.2     .08       0   421.1    .016       0     447     .12       0
   681.4     .04       0   710.3     .08       0   903.2     .06       0
  1140.1     .12       0
#XS Ineff= 2 , 0
          533.98    1880   781.9         1876.04
Permanent Ineff=
       F       F
#Block Obstruct= 2 ,-1
    67.6   101.31890.376   897.4   934.71896.688
Bank Sta=681.4,710.3
XS Rating Curve= 0 ,0
Exp/Cntr=0.3,0.1

Type RM Length L Ch R = 1 ,2254    ,117.9,168.5,182.3
XS GIS Cut Line= 5
     2172742.581      291964.496     2172662.098      292213.057
     2172541.337      292707.897     2172593.722      292805.185
     2172493.227      293243.515
#Sta/Elev= 30
       0 1878.78    93.3 1877.51   193.3 1876.37     296 1875.42   380.5 1871.89
   470.7 1870.68   579.7 1870.94   747.6 1871.84   776.1 1870.62   783.5 1868.01
   794.7 1864.78   820.1 1864.32   824.9 1865.23   829.8 1868.15   835.7 1871.39
   851.6 1873.78   927.6  1875.9   971.4 1879.43   984.7 1882.28    1005 1889.09
  1061.4 1912.79    1069 1918.19  1079.1 1922.21  1119.5 1945.28  1129.6 1948.21
  1139.7 1955.47  1186.8  1981.7  1222.9 1998.26    1264 2014.96  1330.8 2044.53
#Mann= 9 ,-1 , 0
       0    .016       0    93.3     .12       0   193.3     .06       0
   210.5     .12       0   380.5     .08       0   579.7    .016       0
   747.6     .12       0   783.5     .04       0   829.8     .12       0
#XS Ineff= 2 , 0
          691.22 1878.14   841.2         1878.28
Permanent Ineff=
       F       F
#Block Obstruct= 3 ,-1
   425.8   428.11885.891     525   566.3 1885.89     620   675.1 1885.89
Bank Sta=783.5,829.8
XS Rating Curve= 0 ,0
Exp/Cntr=0.3,0.1

Type RM Length L Ch R = 1 ,2086    ,225.9,234.8,242.9
XS GIS Cut Line= 5
     2172733.118      291964.129      2172641.53      292214.319
     2172445.772      292652.517     2172370.738       292771.12
     2172140.683      293157.556
#Sta/Elev= 30
       0 1878.82   311.4 1873.82     440 1870.24   456.6 1866.44   492.5 1866.48
     514 1869.87   560.7 1871.59   592.9 1871.43   621.8 1866.84   657.8 1869.34
   679.3  1866.3   704.5  1866.2   722.5 1870.97   746.4 1871.89   773.2 1866.69
   782.7 1863.97   814.4  1866.5   868.6 1876.03   898.9 1886.54     960 1924.05
  1018.9 1963.88  1101.3 2014.31  1135.6 2034.08  1147.1 2037.88  1162.4 2047.91
  1204.4 2066.34  1227.3 2070.13  1263.1 2065.38  1297.5 2055.59  1336.4 2038.11
#Mann= 8 ,-1 , 0
       0     .08       0   311.4     .12       0   364.6     .06       0
   463.8    .016       0   621.8     .06       0   746.4     .06       0
   773.2     .04       0   814.4     .12       0
#XS Ineff= 2 , 0
          750.29 1879.84
Permanent Ineff=
       F       F
#Block Obstruct= 2 ,-1
   323.6     3321886.607     543     6101886.607
Bank Sta=773.2,814.4
XS Rating Curve= 0 ,0
Exp/Cntr=0.3,0.1

Type RM Length L Ch R = 1 ,1851    ,178.9,160.9,155.9
XS GIS Cut Line= 5
     2172729.816      291958.162     2172649.865      292188.995
     2172299.683       292496.49      2172197.14      292571.066
     2172008.625      292778.329
#Sta/Elev= 30
       0 1878.89     3.4 1878.82   271.6 1875.06   294.9 1872.81   362.7    1871
   390.2 1871.24   542.9  1865.8     690 1864.08   698.9 1870.36   703.3 1870.53
   711.9 1870.14   724.1  1867.8   740.3 1866.93   748.9 1864.43   756.5 1861.71
   760.6 1861.17   780.9 1861.56   787.9 1864.54     793 1866.68     805  1869.6
     819 1877.52   837.8 1886.91   879.6 1911.21   904.4 1927.77     945 1951.92
  1000.4 1981.16  1046.8 2003.46  1071.8 2014.14  1105.9  2025.8  1117.3 2028.65
#Mann= 7 ,-1 , 0
       0    .016       0     3.4     .08       0   362.7     .06       0
   542.9    .025       0   707.7     .06       0   748.9     .04       0
   787.9     .12       0
#XS Ineff= 2 , 0
          703.31  1874.7
Permanent Ineff=
       F       F
Bank Sta=748.9,787.9
XS Rating Curve= 0 ,0
Exp/Cntr=0.3,0.1