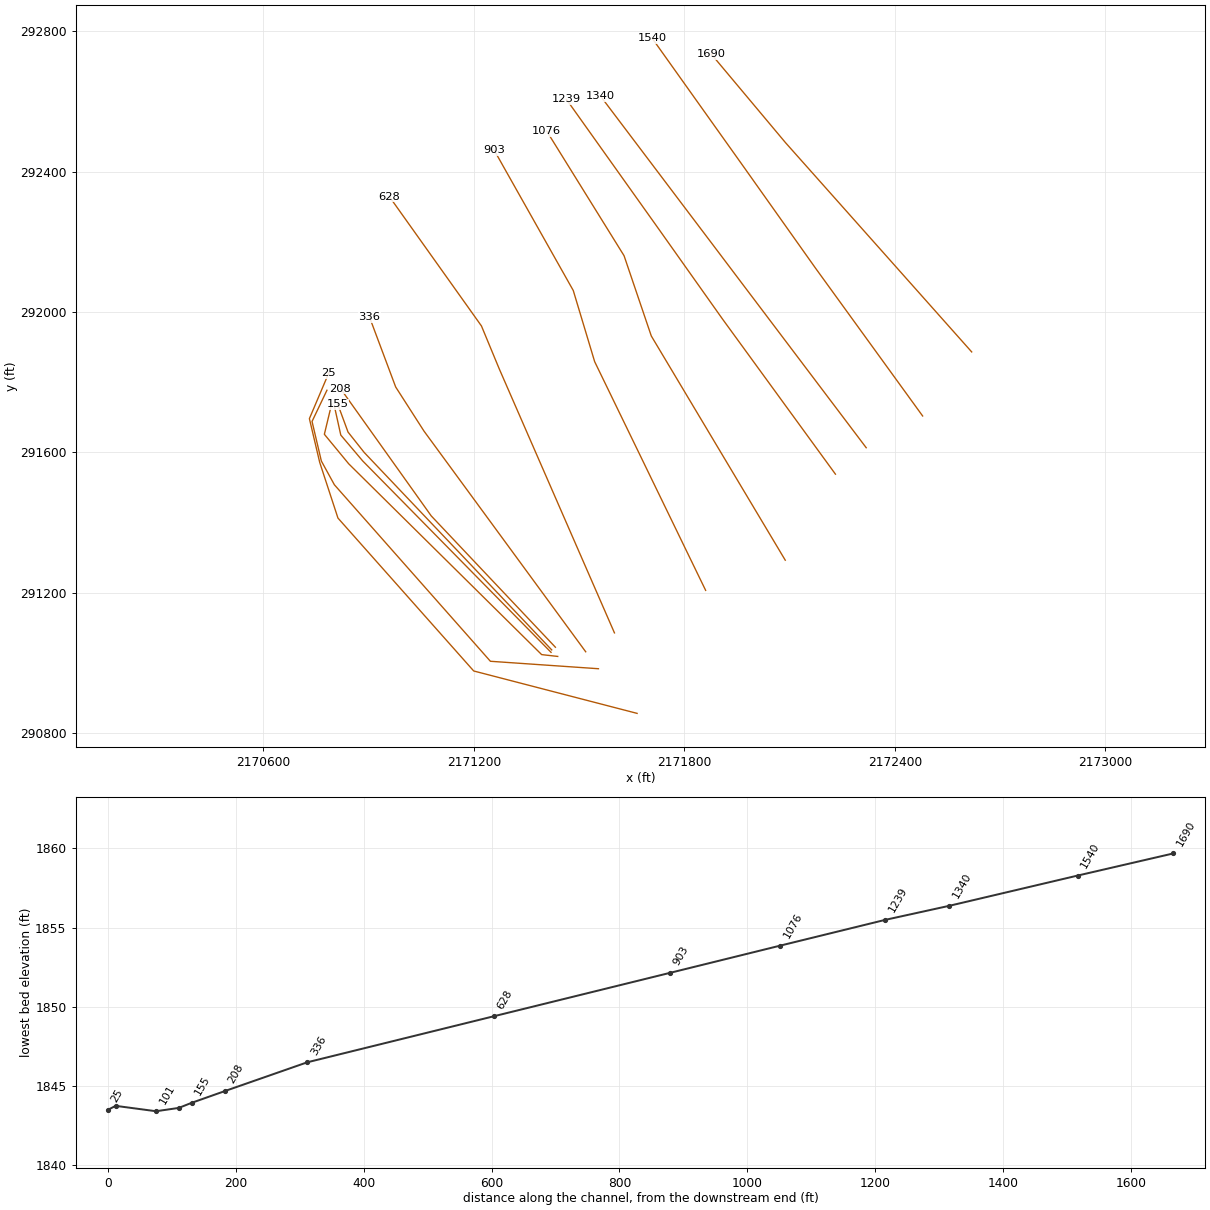
HEC-RAS study WADESCK1.prj: WADESCK1

--- WADESCK1.g01 (geometry) --- (continued)

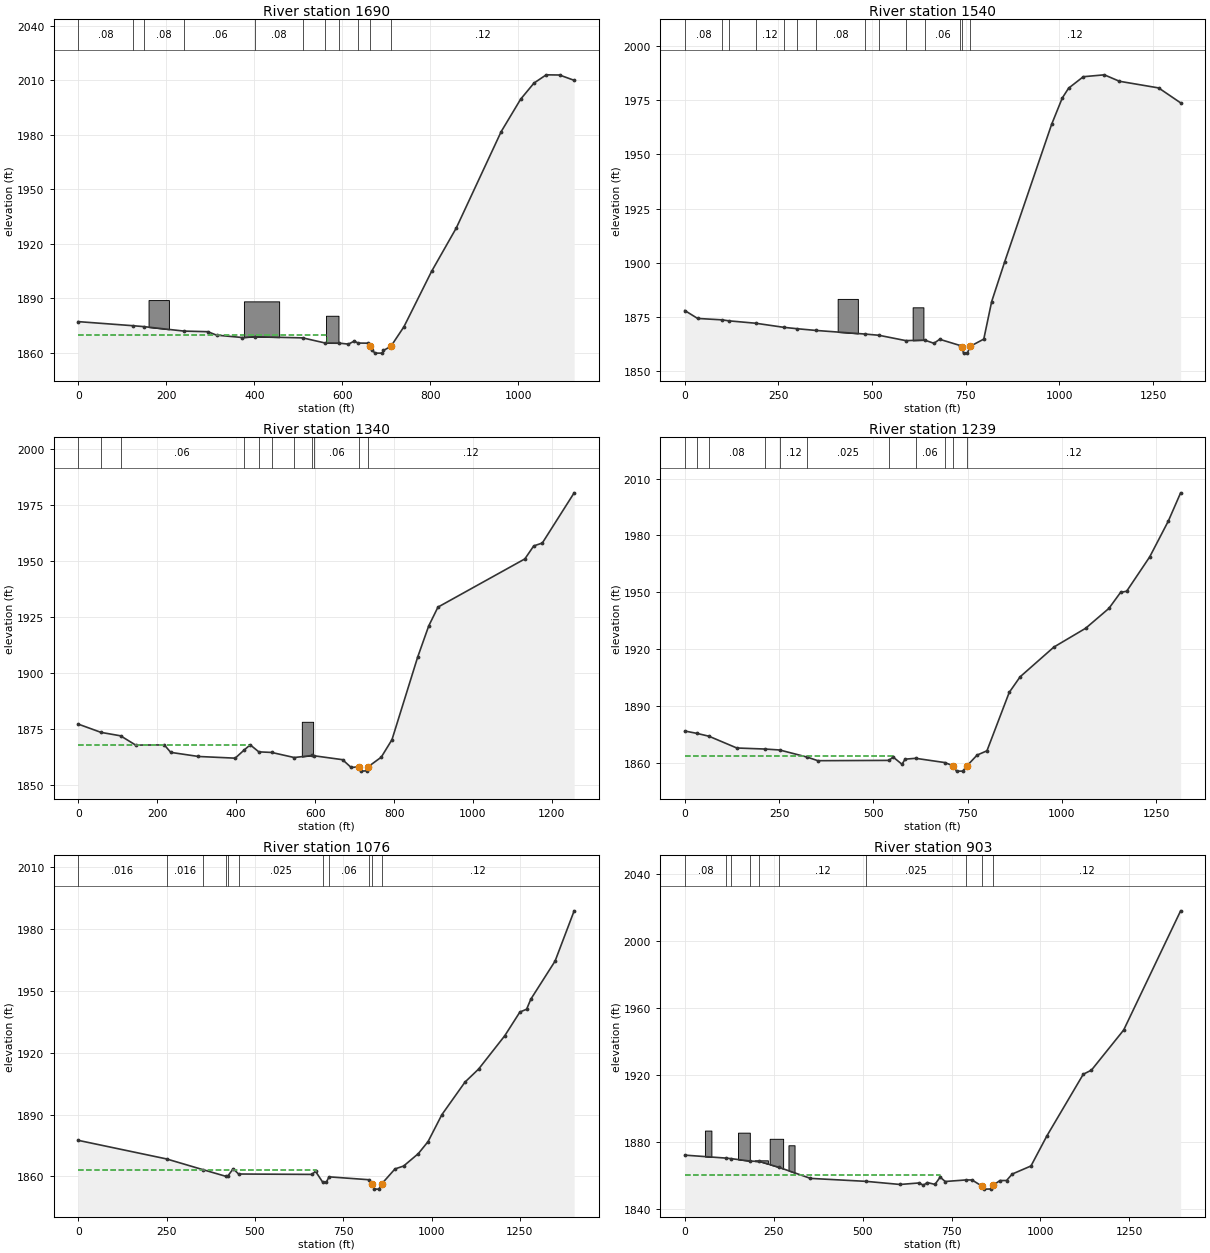
Type RM Length L Ch R = 1 ,1690    ,157.5,149.8,146.5
XS GIS Cut Line= 3
     2172618.787       291886.55     2172088.006      292483.111
     2171877.055      292734.892
#Sta/Elev= 30
       0 1877.04   124.3 1874.79   148.5  1874.3   240.1 1871.83   294.4 1871.49
   314.2 1869.59   372.9 1868.29   400.8 1868.73     510 1868.09   561.3 1865.25
     592 1865.21     614 1864.66   627.2  1866.3     636 1865.24   658.7 1865.17
     663 1863.51   666.7 1861.36     675 1859.69   691.3 1859.69   693.6 1861.15
   710.6 1863.48   740.1 1874.22   802.8 1904.66   859.2 1928.69   961.1  1981.7
  1005.4 1999.59  1035.7 2008.45  1063.5 2012.99  1093.8 2012.89    1127 2009.96
#Mann= 11 ,-1 , 0
       0     .08       0   124.3    .016       0   148.5     .08       0
   240.1     .06       0   400.8     .08       0     510     .06       0
   561.3    .016       0     592     .06       0     636     .12       0
     663     .04       0   710.6     .12       0
#XS Ineff= 2 , 0
           564.4 1869.41
Permanent Ineff=
       F       F
#Block Obstruct= 3 ,-1
   159.6   205.91888.902   376.4   456.4  1888.2   562.9   591.3 1880.27
Bank Sta=663,710.6
XS Rating Curve= 0 ,0
Exp/Cntr=0.3,0.1

Type RM Length L Ch R = 1 ,1540    ,200.5,200.7,201.1
XS GIS Cut Line= 4
     2172478.985      291704.019      2172173.22      292125.973
     2171972.211      292409.513     2171708.371      292780.206
#Sta/Elev= 30
       0 1877.94    34.2 1874.29    99.1 1873.64   118.6 1873.17   189.1 1872.08
   264.3 1870.19   300.3 1869.54   350.3 1868.75   481.1 1867.09     518 1866.53
   590.1 1864.06   640.4  1864.3   665.2 1862.82   680.4 1864.67   735.4 1861.79
   739.2  1861.1   744.1 1858.29   754.5 1858.33   761.7 1861.41   798.2 1864.76
   819.2 1882.05   854.2 1900.52   979.4 1963.86  1007.7 1975.96  1024.7 1980.52
  1063.9 1985.79    1120 1986.66  1160.3 1983.69    1265 1980.62  1323.7 1973.73
#Mann= 14 ,-1 , 0
       0     .08       0    99.1    .016       0   118.6     .08       0
   189.1     .12       0   264.3     .06       0   300.3    .016       0
   350.3     .08       0   481.1     .12       0     518     .06       0
   590.1    .016       0   640.4     .06       0   735.4     .12       0
   739.2     .04       0   761.7     .12       0
#Block Obstruct= 2 ,-1
   408.1     462  1883.3   608.3     6371879.417
Bank Sta=739.2,761.7
XS Rating Curve= 0 ,0
Exp/Cntr=0.3,0.1

Type RM Length L Ch R = 1 ,1340    ,101,100.4,99.7
XS GIS Cut Line= 2
     2172318.164      291613.565     2171560.781      292615.924
#Sta/Elev= 30
       0 1877.32    57.7 1873.64     107 1872.12   145.3 1867.99   217.9 1868.06
   234.1 1864.74   304.4 1862.91   397.4 1862.16   419.2 1865.63   435.5  1868.1
   457.3 1864.97   489.9 1864.71     547 1862.44   592.2 1863.35   597.4 1863.22
   669.5 1861.48   691.3    1858   710.6  1858.3   715.7 1856.38   730.4  1856.5
   734.9  1858.4   767.5  1862.6   794.7  1870.4   859.7 1907.15   887.8  1921.1
   911.2 1929.48  1131.4 1950.97  1153.9 1956.76  1175.6 1958.04  1256.3 1980.42
#Mann= 11 ,-1 , 0
       0     .12       0    57.7    .016       0     107     .06       0
   419.2     .12       0   457.3    .016       0   489.9     .06       0
     547    .016       0   592.2     .08       0   597.4     .06       0
   710.6     .04       0   734.9     .12       0
#XS Ineff= 2 , 0
           431.2 1868.17
Permanent Ineff=
       F       F
#Block Obstruct= 1 ,-1
   566.3   594.91878.369
Bank Sta=710.6,734.9
XS Rating Curve= 0 ,0
Exp/Cntr=0.3,0.1

Type RM Length L Ch R = 1 ,1239    ,185.4,163.4,161.6
XS GIS Cut Line= 4
     2172230.489      291538.225     2171908.997      291979.806
     2171727.798      292235.552     2171463.958      292606.245
#Sta/Elev= 30
       0 1876.68    32.4 1875.42    64.1 1873.92   137.9 1867.71   213.5 1867.15
   251.6 1866.65   324.6 1862.89   352.8    1861   540.8 1861.16   552.6  1862.9
   575.9  1859.1     584 1861.81   612.1 1862.26   689.1 1860.02   710.2 1858.42
   720.5 1855.49   736.9 1855.49   747.9 1858.25     775 1863.97   801.1 1866.22
   860.1 1897.05   889.1 1905.32   978.5 1921.01  1062.8 1930.95  1124.4 1941.44
  1155.4  1949.9  1171.5 1950.51  1232.6 1968.65    1282 1987.59  1314.6 2002.49
#Mann= 11 ,-1 , 0
       0     .08       0    32.4    .016       0    64.1     .08       0
   213.5     .06       0   251.6     .12       0   324.6    .025       0
   540.8    .016       0   612.1     .06       0   689.1     .12       0
   710.2     .04       0   747.9     .12       0
#XS Ineff= 2 , 0
           551.5 1863.45
Permanent Ineff=
       F       F
Bank Sta=710.2,747.9
XS Rating Curve= 0 ,0
Exp/Cntr=0.3,0.1

Type RM Length L Ch R = 1 ,1076    ,173,172.4,172.2
XS GIS Cut Line= 4
     2172087.479      291293.056     2171705.725      291932.034
     2171628.149      292160.677     2171407.671      292515.892
#Sta/Elev= 30
       0 1877.51   249.8 1868.51   352.7 1863.31   419.3    1860   423.1 1860.17
   438.4 1863.74   453.7  1861.2   661.3 1861.01   671.5 1862.52   692.4  1857.1
     702 1857.16   709.8 1859.83   823.9 1858.41   830.8  1856.3   838.3 1853.87
   851.1 1853.87   858.5 1856.34   896.6 1863.67   920.9 1865.06   962.4 1871.05
   990.2 1876.93  1029.3 1889.98  1094.9  1905.8  1133.3 1912.09  1207.3 1928.23
  1250.2 1939.74  1269.2 1941.09  1281.1 1945.97  1349.8 1964.44  1403.8  1988.8
#Mann= 11 ,-1 , 0
       0    .016       0   249.8    .016       0   352.7     .12       0
   419.3     .06       0   423.1     .12       0   453.7    .025       0
   692.4     .08       0   709.8     .06       0   823.9     .12       0
   830.8     .04       0   858.5     .12       0
#XS Ineff= 2 , 0
           673.3 1863.24
Permanent Ineff=
       F       F
Bank Sta=830.8,858.5
XS Rating Curve= 0 ,0
Exp/Cntr=0.3,0.1

Type RM Length L Ch R = 1 ,903     ,273.2,275.3,277.8
XS GIS Cut Line= 4
     2171860.598      291207.097     2171544.386      291858.712
     2171483.385      292061.592     2171258.484      292460.663
#Sta/Elev= 30
       0 1872.43   116.4 1870.66     131 1870.32   184.5 1868.86   209.9 1868.68
   265.9 1865.07   353.4 1858.56   510.2 1856.78   605.4 1854.93   659.7 1855.85
   670.7 1854.42   681.6 1856.09   703.4 1854.98   718.1 1859.31   732.2  1856.7
   790.4 1857.63   807.5 1857.63   834.9 1854.03   842.7 1852.15     860 1852.23
   865.9 1854.33   886.3 1857.28   904.7 1857.29   920.6 1861.14   973.4 1865.97
  1018.1  1883.9  1120.5 1920.72  1143.4 1923.14  1234.1  1947.1  1394.2 2018.21
#Mann= 10 ,-1 , 0
       0     .08       0   116.4     .12       0     131     .08       0
   184.5     .12       0   209.9     .08       0   265.9     .12       0
   510.2    .025       0   790.4     .12       0   834.9     .04       0
   865.9     .12       0
#XS Ineff= 2 , 0
           718.7 1860.82
Permanent Ineff=
       F       F
#Block Obstruct= 5 ,-1
    56.6    74.81887.084   149.7   182.81885.842   197.1   233.61869.339
   238.7   276.51882.181   291.5   308.61878.318
Bank Sta=834.9,865.9
XS Rating Curve= 0 ,0
Exp/Cntr=0.3,0.1

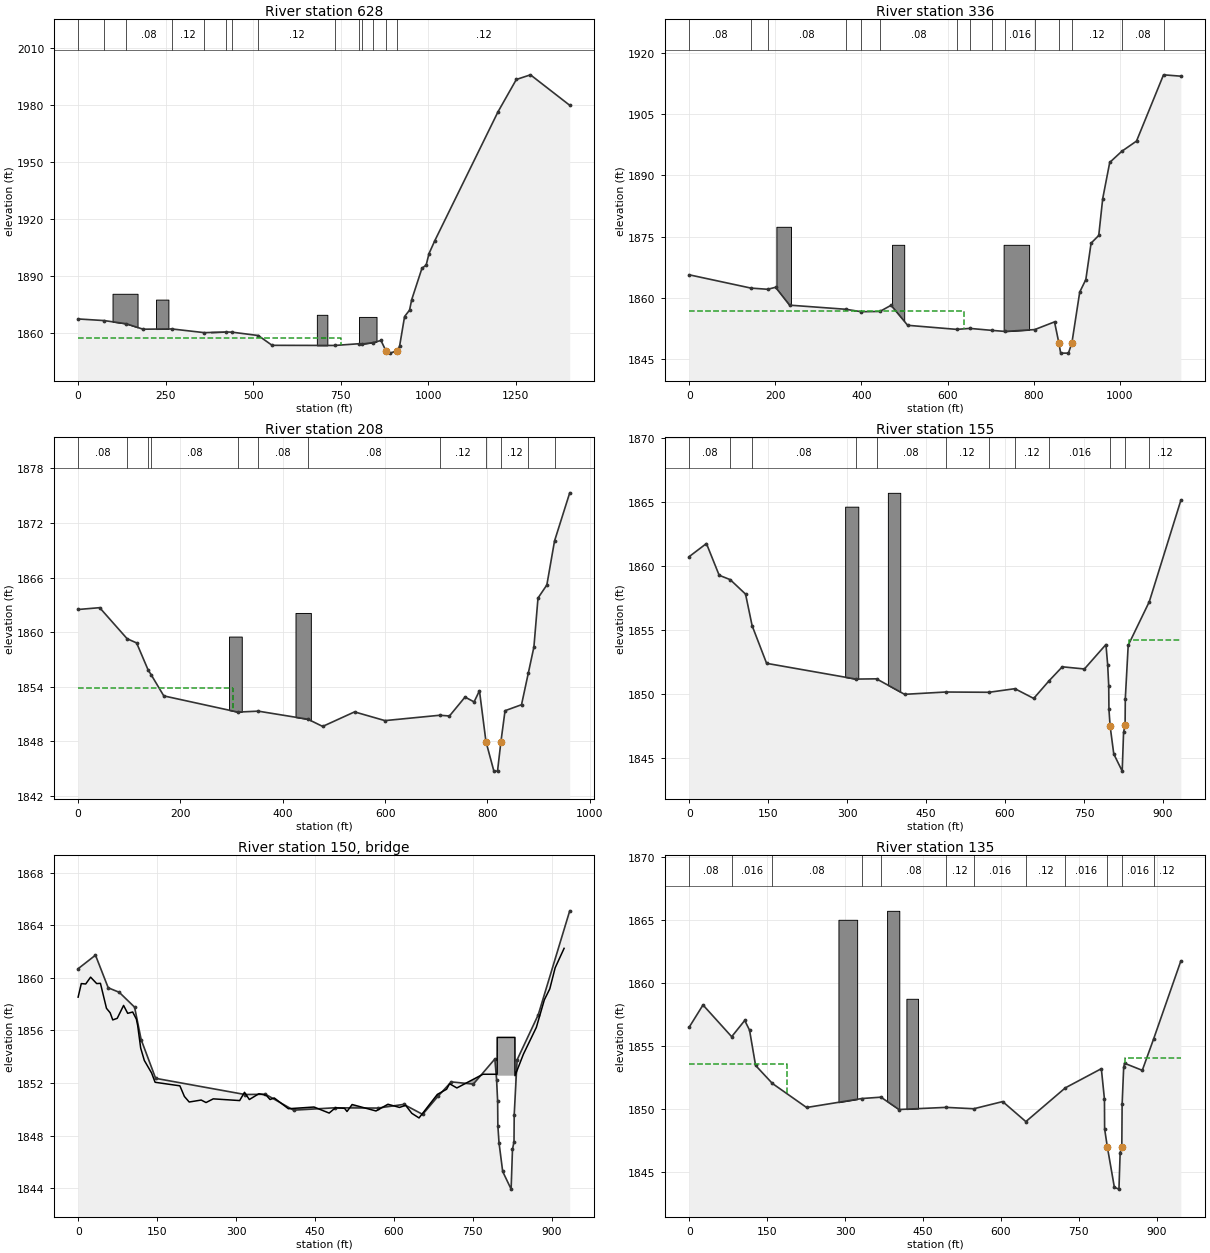
Type RM Length L Ch R = 1 ,628     ,271.1,291.9,294.4
XS GIS Cut Line= 4
     2171600.739      291085.919      2171272.28      291838.624
      2171221.75      291960.518     2170959.866      292328.464
#Sta/Elev= 30
       0 1867.37    74.6 1866.51   137.6 1864.84   185.6 1861.98   267.9 1862.12
     361 1860.16   422.3 1860.53   439.7 1860.43   514.9 1858.66   554.3 1853.51
   733.3 1853.44   801.3 1854.33     812  1854.2     843 1854.95   865.4 1856.06
   879.6  1850.6   890.4 1849.41  912.37 1850.61   918.6 1853.03   932.9 1868.65
   947.1 1872.01   953.2 1877.48   982.5 1893.99   994.6  1895.7  1002.6 1901.68
  1019.3 1908.53  1199.9 1976.25  1252.2 1993.21  1292.6 1995.66  1404.8 1979.65
#Mann= 14 ,-1 , 0
       0     .08       0    74.6    .016       0   137.6     .08       0
   267.9     .12       0     361     .08       0   422.3     .12       0
   439.7    .016       0   514.9     .12       0   733.3    .016       0
   801.3     .12       0     812     .06       0     843     .12       0
   879.6     .04       0  912.37     .12       0
#XS Ineff= 2 , 0
          751.01 1857.41
Permanent Ineff=
       F       F
#Block Obstruct= 5 ,-1
    98.3   169.8  1880.6   222.6     2581877.537   379.6   415.81860.625
   682.2   712.21869.547   802.7   852.71868.444
Bank Sta=879.6,912.37
XS Rating Curve= 0 ,0
Exp/Cntr=0.3,0.1

Type RM Length L Ch R = 1 ,336     ,123.4,128.3,129.4
XS GIS Cut Line= 4
     2171518.815       291032.07     2171057.926      291661.017
     2170977.337      291786.558     2170902.775       291985.61
#Sta/Elev= 30
       0 1865.66   143.4 1862.41   182.3 1862.12   200.4 1862.61   232.9 1858.24
   363.5 1857.23   399.7 1856.63   442.8  1856.7   468.6  1858.2   507.2 1853.31
   621.2 1852.31   651.5 1852.55   703.4 1852.06   733.2 1851.81   802.2 1852.26
   848.2 1854.14   858.1  1849.1   862.5  1846.5   880.5  1846.5   888.5 1848.97
   906.7 1861.43   920.9  1864.5   933.1  1873.4   950.9 1875.29   960.1  1884.3
   976.4 1893.16  1004.4 1895.88  1038.6 1898.38  1101.3 1914.59  1141.5 1914.26
#Mann= 15 ,-1 , 0
       0     .08       0   143.4    .016       0   182.3     .08       0
   363.5     .12       0   399.7    .016       0   442.8     .08       0
   621.2     .08       0   651.5    .016       0   703.4     .12       0
   733.2    .016       0   802.2     .08       0   858.1     .04       0
   888.5     .12       0  1004.4     .08       0  1101.3     .12       0
#XS Ineff= 2 , 0
           637.3 1856.78
Permanent Ineff=
       F       F
#Block Obstruct= 3 ,-1
   202.4   236.31877.409   470.9   499.2    1873     730   789.2    1873
Bank Sta=858.1,888.5
XS Rating Curve= 0 ,0
Exp/Cntr=0.3,0.1

Type RM Length L Ch R = 1 ,208     ,43.9,52.5,53.6
BEGIN DESCRIPTION:
Removed BO's on the left overbank and increased the manning's n to account for the obstruction
END DESCRIPTION:
XS GIS Cut Line= 3
      2171432.47      291045.014     2171078.616      291419.282
     2170820.031      291782.209
#Sta/Elev= 30
       0 1862.48    42.1 1862.68    95.8 1859.26   114.3  1858.8   136.9 1855.81
   142.5 1855.32   167.4 1852.97   311.9 1851.19   352.1 1851.29   449.2  1850.4
   477.9 1849.61   540.2 1851.21   599.6 1850.25   706.7 1850.84   725.7 1850.76
   756.1 1852.84   773.8 1852.31   784.3 1853.54     797 1847.94   812.5 1844.69
   819.6 1844.69   826.2 1847.91   834.3 1851.34   866.5    1852   879.8 1855.49
   890.7 1858.35   898.7 1863.74     916 1865.18     931 1870.02   960.7 1875.32
#Mann= 12 ,-1 , 0
       0     .08       0    95.8    .016       0   136.9     .08       0
   142.5     .08       0   311.9    .016       0   352.1     .08       0
   449.2     .08       0   706.7     .12       0     797    .045       0
   826.2     .12       0   879.8    .016       0     931     .12       0
#XS Ineff= 2 , 0
           302.5 1853.83
Permanent Ineff=
       F       F
#Block Obstruct= 2 ,-1
   294.8   319.8  1859.5   424.8   454.8  1862.1
Bank Sta=797,826.2
XS Rating Curve= 0 ,0
Exp/Cntr=0.5,0.3

Type RM Length L Ch R = 1 ,155     ,19.4,20,20.7
BEGIN DESCRIPTION:
Merged DS Survey WAC012BU
Removed BO's on the left overbank and increased the manning's n to account for the obstruction
END DESCRIPTION:
XS GIS Cut Line= 4
     2171421.969      291037.374     2170887.516      291600.141
     2170841.541      291658.128     2170812.548      291736.824
#Sta/Elev= 30
       0  1860.7    32.7 1861.72    56.9 1859.24    77.8  1858.9     107 1857.77
   119.5  1855.3     147 1852.36   316.8 1851.13   355.8 1851.15   409.1 1849.94
   487.1 1850.12   569.7  1850.1   618.7 1850.38   654.5 1849.62   683.5 1850.99
   708.8 1852.09   750.8 1851.92   791.7 1853.83     795 1852.25     797 1850.61
   797.4 1848.77   799.6 1847.47   806.6 1845.28   822.6 1843.94   825.2 1846.96
   828.1 1847.55   828.5  1849.6     834 1853.77   874.1 1857.18     934 1865.09
#Mann= 12 ,-1 , 0
       0     .08       0    77.8    .016       0   119.5     .08       0
   316.8    .016       0   355.8     .08       0   487.1     .12       0
   569.7     .08       0   618.7     .12       0   683.5    .016       0
   799.6     .04       0   828.1    .016       0   874.1     .12       0
#XS Ineff= 2 , 0
             791 1849.64   834.8         1854.15
Permanent Ineff=
       F       F
#Block Obstruct= 2 ,-1
   296.2   321.2  1864.6   377.4   400.91865.681
Bank Sta=799.6,828.1
XS Rating Curve= 0 ,0
Exp/Cntr=0.5,0.3

Type RM Length L Ch R = 3 ,150     ,,,
BEGIN DESCRIPTION:
Merged DS Survey WAC010RP
Mill Hill Road
END DESCRIPTION:
Bridge Culvert--1,0,-1,-1, 0
Deck Dist Width WeirC Skew NumUp NumDn MinLoCord MaxHiCord MaxSubmerge Is_Ogee
3,15,2.6,0, 60, 60, , , 0.98, 0, 0,0,,
     -.3     5.7    14.1    23.4      35    42.1    53.6    60.6    65.5      74
    86.1    93.9   103.4   110.4   112.9   118.6   125.5   139.4     146   193.1
   201.7   210.8   233.6   242.8   256.5   306.7   315.9   325.1   343.3     357
   364.5   372.4   399.3     448   476.8   488.6   506.1   510.7   520.4   565.8
   588.5   610.5   622.1   633.9   647.6   682.4     700   705.6   719.5  769.07
     796  796.15  829.86     830  846.02  870.55   885.8   896.1   906.3   923.3
 1858.53 1859.56 1859.53 1860.05 1859.56 1859.58 1857.68 1857.34  1856.8 1856.92
  1857.9  1857.3  1857.4 1856.86 1856.37 1854.66 1853.72 1852.76 1852.06 1851.79
 1850.98 1850.56 1850.71 1850.52  1850.8 1850.67  1851.3 1850.75 1851.19 1851.08
 1850.75 1850.87 1850.05 1850.18 1849.72 1850.12 1850.08 1849.84 1850.37 1849.88
 1850.39 1850.15 1850.31  1849.7 1849.35 1851.14 1851.53 1851.95 1851.63 1852.67
 1852.67 1855.47 1855.47 1852.56  1854.2 1856.23 1858.33 1859.16 1860.76 1862.24
                                                                                
                                                                                
                                                                                
                                                                                
                                                                                
         1852.56 1852.56
     1.7     7.7    16.1    25.4      37    44.1    55.6    62.6    67.5      76
    88.1    95.9   105.4   112.4   114.9   120.6   127.5     148   195.1   203.7
   212.8   235.6   244.8   258.5   308.7   317.9   327.1   345.3     359   366.5
   374.4   401.3     450   478.8   490.6   508.1   512.7   522.4   567.8   590.5
   612.5   624.1   635.9   649.6   684.4     702   707.6   721.5  771.07  798.05
  798.15  831.86     832  848.02  872.55   887.8   898.1   908.3   925.1   943.6
 1858.53 1859.56 1859.53 1860.05 1859.56 1859.58 1857.68 1857.34  1856.8 1856.92
  1857.9  1857.3  1857.4 1856.86 1856.37 1854.66 1853.72 1852.06 1851.79 1850.98
 1850.56 1850.71 1850.52  1850.8 1850.67  1851.3 1850.75 1851.19 1851.08 1850.75
 1850.87 1850.05 1850.18 1849.72 1850.12 1850.08 1849.84 1850.37 1849.88 1850.39
 1850.15 1850.31  1849.7 1849.35 1851.14 1851.53 1851.95 1851.63 1852.67 1852.56
 1855.47 1855.47 1852.56  1854.2 1856.23 1858.33 1859.16 1860.76 1862.23 1861.34
                                                                                
                                                                                
                                                                                
                                                                                
                                                                                
 1852.56 1852.56
BR Coef=-1 , 1 , 0 ,, 0 ,,,0.8,0,1.2,0,
WSPro=,,,, 1 ,,,, 0 ,,,, 0 ,,,,-1 ,-1 ,-1 , 0 , 0 , 0 , 0 , 0
BC Design=,, 0 ,, 0 ,,0,,,,
BC HTab HWMax=0
BC HTab TWMax=0
BC HTab MaxFlow=0
BC Use User HTab Curves=0
BC User HTab FreeFlow(D)= 0

Type RM Length L Ch R = 1 ,135     ,34,35.5,35
BEGIN DESCRIPTION:
Merged US Survey WAC008BD
END DESCRIPTION:
XS GIS Cut Line= 4
     2171420.101      291030.462       2170883.2      291576.022
      2170820.85      291649.629     2170802.665      291731.896
#Sta/Elev= 30
       0 1856.48    26.5 1858.24    81.7 1855.72   106.8 1857.01   116.1 1856.24
   127.7 1853.44     160 1852.01   225.9  1850.1   331.9 1850.81     369 1850.92
   403.6 1849.94   494.3 1850.11   547.6    1850   603.3 1850.57   647.9 1848.98
   723.9 1851.66   793.2 1853.18   799.2 1850.76   799.5  1848.4   804.7 1846.98
   818.3 1843.76   827.1 1843.62   829.4 1846.52   832.6    1847   833.2 1850.34
   836.2 1853.29   837.9 1853.61     872 1853.05   893.8 1855.54   946.2 1861.73
#Mann= 12 ,-1 , 0
       0     .08       0    81.7    .016       0     160     .08       0
   331.9     .08       0     369     .08       0   494.3     .12       0
   547.6    .016       0   647.9     .12       0   723.9    .016       0
   804.7     .04       0   832.6    .016       0   893.8     .12       0
#XS Ineff= 2 , 0
           188.6 1853.57   838.1            1854
Permanent Ineff=
       F       F
#Block Obstruct= 3 ,-1
   287.2   323.2    1865   380.8   404.31865.712     418   440.4 1858.73
Bank Sta=804.7,832.6
XS Rating Curve= 0 ,0
Exp/Cntr=0.5,0.3

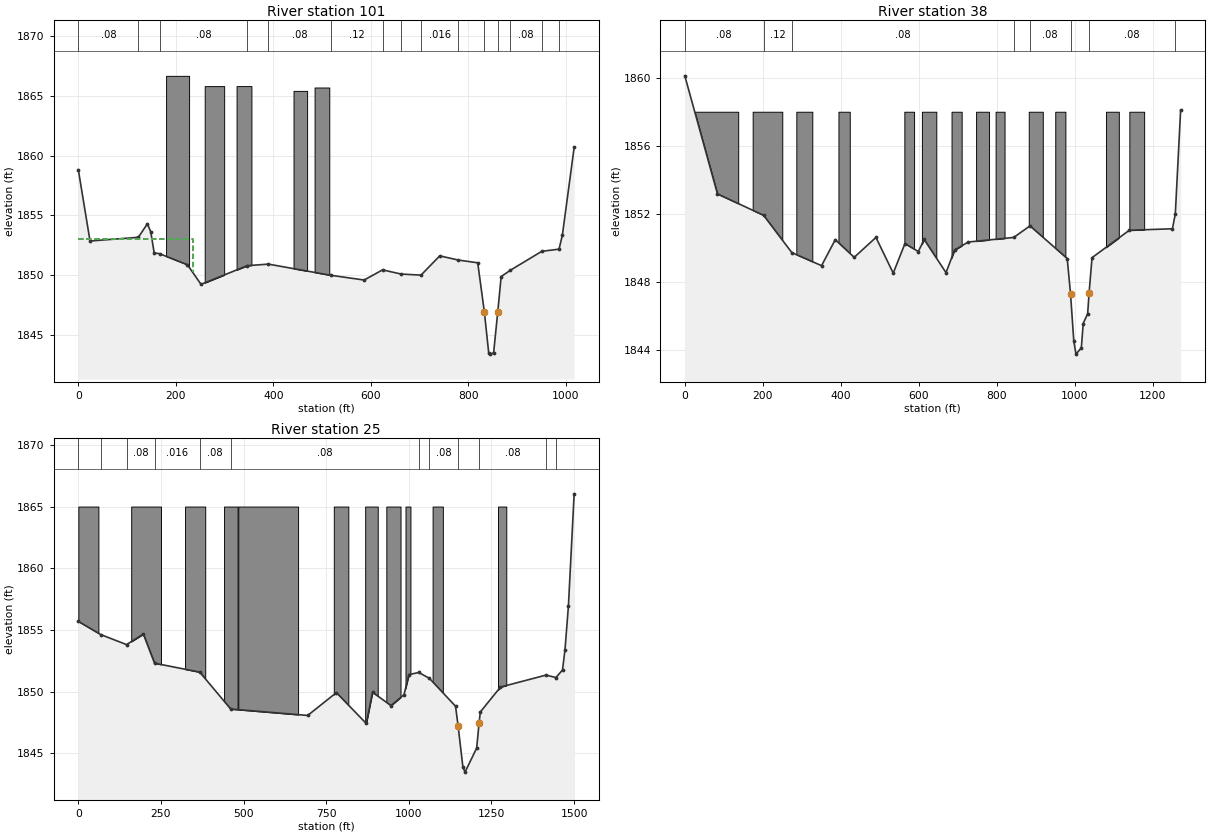
Type RM Length L Ch R = 1 ,101     ,74.2,63.2,56.1
XS GIS Cut Line= 5
     2171439.152      291018.801     2171393.256      291023.997
     2170843.366      291567.825     2170774.088      291651.824
     2170794.871      291738.421
#Sta/Elev= 30
       0 1858.81      24 1852.86   123.2 1853.17   141.7  1854.3   148.7 1853.62
   155.6 1851.87   166.7  1851.8   223.8 1850.88   251.8 1849.24   346.6  1850.8
     390 1850.93   517.6    1850   586.6  1849.6   624.3 1850.45   662.4  1850.1
   703.2 1850.01   741.7 1851.62   779.7 1851.27   819.6 1851.04   833.1 1846.97
   842.1 1843.54   844.8 1843.41   852.2 1843.51   860.6 1846.89   867.7 1849.89
   886.7 1850.42   951.1    1852   986.5 1852.18   993.3 1853.35  1017.5 1860.68
#Mann= 15 ,-1 , 0
       0     .08       0   123.2    .016       0   166.7     .08       0
   346.6    .016       0     390     .08       0   517.6     .12       0
   624.3    .016       0   662.4     .12       0   703.2    .016       0
   779.7     .12       0   833.1     .04       0   860.6     .12       0
   886.7     .08       0   951.1    .016       0   986.5     .12       0
#XS Ineff= 2 , 0
           234.3 1853.03
Permanent Ineff=
       F       F
#Block Obstruct= 5 ,-1
   180.1   227.31866.661   259.3   299.3  1865.8   324.7   355.21865.803
   441.6   469.51865.404   484.8     5151865.686
Bank Sta=833.1,860.6
XS Rating Curve= 0 ,0
Exp/Cntr=0.3,0.1

Type RM Length L Ch R = 1 ,38      ,24.4,12.5,6.8
XS GIS Cut Line= 6
2171555.09966396290983.7524269812171247.22346901291004.985268012
2170802.66085993291507.9381899322170765.50338813291575.617870719
2170738.96233684291688.417338695 2170781.4280189291777.329860513
#Sta/Elev= 30
       0 1860.11    83.7 1853.17   202.1 1851.91   274.4 1849.72   350.7 1848.95
   385.9 1850.48   434.4 1849.44   490.2 1850.61   534.5 1848.51   564.6 1850.25
   598.9 1849.78   613.8 1850.49   669.9 1848.54   691.8 1849.87   726.9 1850.34
   843.5 1850.61   885.3 1851.29   980.7 1849.37   989.2 1847.29   997.5 1844.53
  1003.1 1843.75  1016.9 1844.12  1021.7 1845.55  1033.1 1846.13  1036.8 1847.36
  1044.3 1849.42  1139.8 1851.03  1250.5 1851.12  1257.9    18521271.495 1858.09
#Mann= 8 ,-1 , 0
       0     .08       0   202.1     .12       0   274.4     .08       0
   843.5     .12       0   885.3     .08       0   989.2     .04       0
  1036.8     .08       0  1257.9     .12       0
#Block Obstruct= 13 ,-1
       0     137    1858     174     250    1858     286     327    1858
     394     423    1858     563     588    1858     608     645    1858
     684     710    1858     747     780    1858     797     820    1858
     882     918    1858     950     976    1858    1080    1113    1858
    1140    1178    1858
Bank Sta=989.2,1036.8
XS Rating Curve= 0 ,0
Exp/Cntr(USF)=0,0
Exp/Cntr=0.3,0.1

Type RM Length L Ch R = 1 ,25      ,,,
XS GIS Cut Line= 6
2171665.29218828290856.5222592912171199.67913719290977.337307534
2170812.79948832291413.0859646792170760.79173224291571.738114076
2170731.40068894291696.4273886972170786.62022484291826.460489374
#Sta/Elev= 30
       0  1855.7    67.9 1854.63   145.8 1853.82   196.7 1854.67   230.6 1852.31
   367.4 1851.59   461.1  1848.6   694.1 1848.08   780.9 1849.93   871.3 1847.43
   890.2 1849.96   946.1 1848.88   985.6 1849.77  1000.4 1851.39  1030.1 1851.56
  1062.2 1851.09  1141.4 1848.83  1149.2 1847.23  1163.7  1843.9  1170.1 1843.49
  1205.4 1845.44  1212.5 1847.43  1216.4 1848.36  1277.4 1850.38  1415.3 1851.35
  1445.1 1851.15  1465.1 1851.76  1472.7 1853.42    1483 1856.941500.369 1866.03
#Mann= 12 ,-1 , 0
       0     .08       0    67.9    .016       0   145.8     .08       0
   230.6    .016       0   367.4     .08       0   461.1     .08       0
  1030.1    .016       0  1062.2     .08       0  1149.2     .04       0
  1212.5     .08       0  1415.3     .12       0  1445.1     .08       0
#Block Obstruct= 11 ,-1
       0    60.7    1865     160     250    1865     323     384    1865
     441     482    1865     484     665    1865     773     817    1865
     868     906    1865     932     975    1865     990    1005    1865
    1072    1103    1865    1270    1295    1865
Bank Sta=1149.2,1212.5
XS Rating Curve= 0 ,0
Exp/Cntr(USF)=0,0
Exp/Cntr=0.3,0.1
LCMann Table=0

Chan Stop Cuts=-1
Use User Specified Reach Order=0
Composite Channel Slope=5